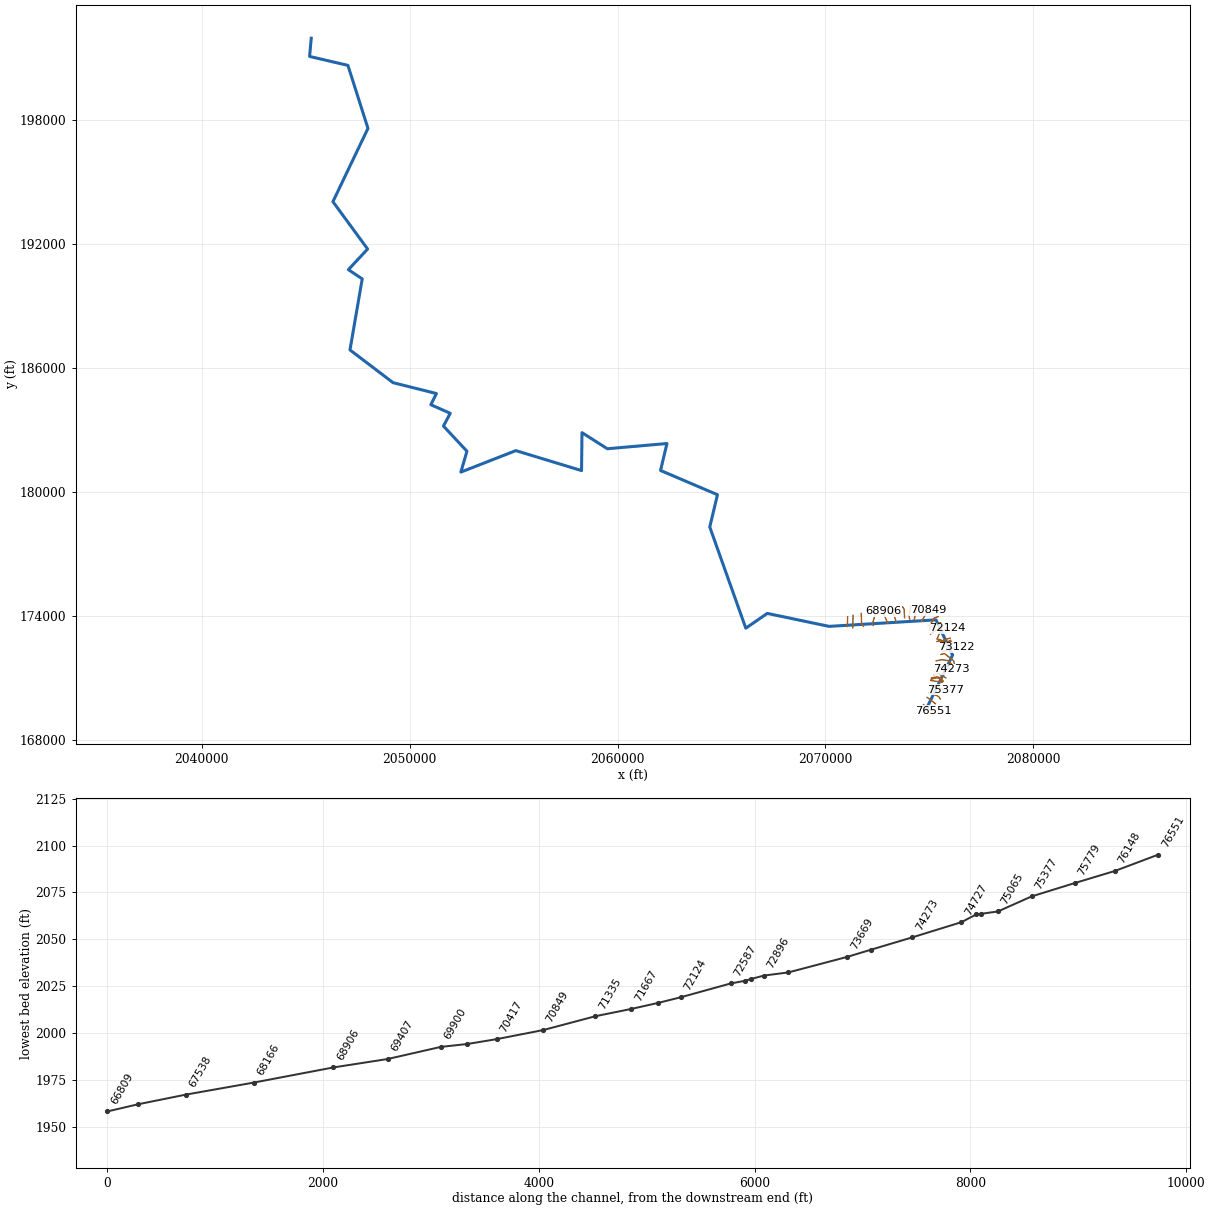
--- HNSCK.prj (project) ---

Proj Title=HNSCK
Current Plan=p01
Default Exp/Contr=0,0
English Units
Geom File=g01
Flow File=f01
Plan File=p01
Background Map Layer=Inundation Boundary (01pct Value_0)
BEGIN DESCRIPTION:
Stream Name: Hans Creek
Flood Zone: Approximate
Monroe County, West Virginia
HEC-RAS Version: 5.0.7
Vertical Datum: NAVD88
Projection: NAD 1983 StatePlane West Virginia S FIPS 4702 (US Feet)
LiDAR: 2016, 1-meter
Land Use: 2016 NLCD
Hydrologic Method:
SIR2010-5033 regression equations
END DESCRIPTION:
DSS Export Rating Curves= 0
DSS Export Rating Curve Sorted= 0
DSS Export Volume Flow Curves= 0
DXF OffsetX= 0
DXF OffsetY= 0
DXF ScaleX= 0
DXF ScaleY= 0

--- HNSCK.p01 (plan) ---

Plan Title=Floodplain
Program Version=5.07
Short Identifier=Floodplain
Geom File=g01
Flow File=f01
Subcritical Flow
K Sum by GR= 0
Std Step Tol= 0.01
Critical Tol= 0.01
Num of Std Step Trials= 20
Max Error Tol= 0.3
Flow Tol Ratio= 0.001
Split Flow NTrial= 30
Split Flow Tol= 0.02
Split Flow Ratio= 0.02
Log Output Level= 0
Friction Slope Method= 1
Unsteady Friction Slope Method= 2
Unsteady Bridges Friction Slope Method= 1
Parabolic Critical Depth
Global Vel Dist= 0 , 0 , 0
Global Log Level= 0
CheckData=True
Encroach Param=-1 ,0,0, 0
Mapping Interval=1HOUR
Computation Time Step Use Courant=        0
Computation Time Step Use Time Series=    0
Computation Time Step Count To Double=0
Computation Time Step Max Doubling=0
Computation Time Step Max Halving=0
Computation Time Step Residence Courant=0
Run HTab= 0
Run UNet= 0
Run Sediment= 0
Run PostProcess= 0
Run WQNet= 0
Run RASMapper=-1
UNET Theta= 0
UNET Theta Warmup= 0
UNET ZTol= 0
UNET ZSATol= 0
UNET MxIter= 0
UNET Max Iter WO Improvement= 0
UNET MaxInSteps= 0
UNET DtIC= 0
UNET DtMin= 0
UNET MaxCRTS= 0
UNET WFStab= 0
UNET SFStab= 0
UNET WFX= 1
UNET SFX= 1
UNET 1D Methodology=Finite Difference
UNET DSS MLevel= 1
UNET Pardiso=0
UNET DZMax Abort= 0
UNET Use Existing IB Tables= 0
UNET Froude Reduction=False
UNET Froude Limit= 0
UNET Froude Power= 0
UNET D1 Cores= 0
UNET D2 Coriolis=0
UNET D2 Cores= 0
UNET D2 Theta= 1
UNET D2 Theta Warmup= 1
UNET D2 Z Tol= 0.01
UNET D2 Volume Tol= 0.01
UNET D2 Max Iterations= 20
UNET D2 Equation= 0
UNET D2 RampUpFraction=0.1
UNET D2 TimeSlices= 1
UNET D2 BCVolumeCheck=0
UNET D1D2 MaxIter= 0
UNET D1D2 ZTol=0.01
UNET D1D2 QTol=0.1
UNET D1D2 MinQTol=1
Write IC File= 0
Write IC File at Fixed DateTime=0
Write IC File at Sim End=0
Echo Input=False
Echo Parameters=False
Echo Output=False
Write Detailed= 0
HDF Write Warmup=0
HDF Write Time Slices=0
HDF Flush=0
HDF Face Node Velocities=0
HDF Compression= 1
HDF Chunk Size= 1
HDF Spatial Parts= 1
HDF Use Max Rows=0
HDF Fixed Rows= 1
Calibration Method= 0
Calibration Iterations= 20
Calibration Max Change=0.05
Calibration Tolerance=0.2
Calibration Maximum=1.5
Calibration Minimum=0.5
Calibration Optimization Method= 1
WQ AD Non Conservative
WQ ULTIMATE=-1
WQ Max Comp Step=1HOUR
WQ Output Interval=15MIN
WQ Output Selected Increments= 0
WQ Output face flow=0
WQ Output face velocity=0
WQ Output face area=0
WQ Output face dispersion=0
WQ Output cell volume=0
WQ Output cell surface area=0
WQ Output cell continuity=0
WQ Output cumulative cell continuity=0
WQ Output face conc=0
WQ Output face dconc_dx=0
WQ Output face courant=0
WQ Output face peclet=0
WQ Output face adv mass=0
WQ Output face disp mass=0
WQ Output cell mass=0
WQ Output cell source sink temp=0
WQ Output nsm pathways=0
WQ Output nsm derived pathways=0
WQ Output MaxMinRange=-1
WQ Daily Max Min Mean=-1
WQ Daily Range=0
WQ Daily Time=0
WQ Create Restart=0
WQ Fixed Restart=0
WQ System Summary=0
WQ Write To DSS=0
WQ Use Fixed Temperature=0
Sorting and Armoring Iterations= 10
XS Update Threshold= 0.02
Bed Roughness Predictor= 0
Hydraulics Update Threshold= 0.02
Energy Slope Method= 1
Volume Change Method= 1
Sediment Retention Method= 0
XS Weighting Method= 0
Number of US Weighted Cross Sections= 1
Number of DS Weighted Cross Sections= 1
Upstream XS Weight=0
Main XS Weight=1
Downstream XS Weight=0
Number of DS XS's Weighted with US Boundary= 1
Upstream Boundary Weight= 1
Weight of XSs Associated with US Boundary= 0
Number of US XS's Weighted with DS Boundary= 1
Downstream Boundary Weight= 0.5
Weight of XSs Associated with DS Boundary= 0.5
Percentile Method= 0
Sediment Output Level= 3
Mass or Volume Output= 0
Output Increment Type= 1
Profile and TS Output Increment= 1
XS Output Flag= 0
XS Output Increment= 10
Write Gradation File= 0
Read Gradation Hotstart= 0
Write HDF5 File= 1
Write Binary Output= 1
Write DSS Sediment File= 0
SV Curve= 0
Specific Gage Flag= 0

--- HNSCK.f01 (steady flow) ---

Flow Title=Flow
Program Version=5.07
Number of Profiles= 6
Profile Names=01pct,10pct,04pct,02pct,0_2pct,01plus
River Rch & RM=HNSCK,Main            ,76551
     659     350     464     559     918     975
River Rch & RM=HNSCK,Main            ,73122
     841     451     596     714    1170    1240
River Rch & RM=HNSCK,Main            ,72896
     910     490     646     774    1260    1350
River Rch & RM=HNSCK,Main            ,69407
    1000     541     712     852    1380    1480
River Rch & RM=HNSCK,Main            ,64595
    1110     601     789     944    1530    1640
River Rch & RM=HNSCK,Main            ,61140
    1420     777    1020    1210    1950    2100
River Rch & RM=HNSCK,Main            ,60679
    1520     835    1090    1300    2090    2250
River Rch & RM=HNSCK,Main            ,59174
    1630     899    1170    1400    2240    2420
River Rch & RM=HNSCK,Main            ,52094
    2000    1110    1440    1710    2720    2950
River Rch & RM=HNSCK,Main            ,51063
    2020    1120    1450    1730    2750    2980
River Rch & RM=HNSCK,Main            ,50220
    2260    1260    1630    1930    3070    3340
River Rch & RM=HNSCK,Main            ,49145
    2380    1330    1720    2040    3230    3510
River Rch & RM=HNSCK,Main            ,45647
    2590    1450    1880    2220    3520    3830
River Rch & RM=HNSCK,Main            ,32617
    3370    1910    2450    2900    4550    4990
River Rch & RM=HNSCK,Main            ,32141
    3490    1980    2550    3010    4720    5170
River Rch & RM=HNSCK,Main            ,29210
    3850    2190    2810    3320    5190    5700
River Rch & RM=HNSCK,Main            ,20864
    4130    2350    3020    3550    5550    6100
River Rch & RM=HNSCK,Main            ,15240
    4520    2590    3310    3890    6070    6680
Boundary for River Rch & Prof#=HNSCK,Main            , 1
Up Type= 0
Dn Type= 3
Dn Slope=0.001
Boundary for River Rch & Prof#=HNSCK,Main            , 2
Up Type= 0
Dn Type= 3
Dn Slope=0.001
Boundary for River Rch & Prof#=HNSCK,Main            , 3
Up Type= 0
Dn Type= 3
Dn Slope=0.001
Boundary for River Rch & Prof#=HNSCK,Main            , 4
Up Type= 0
Dn Type= 3
Dn Slope=0.001
Boundary for River Rch & Prof#=HNSCK,Main            , 5
Up Type= 0
Dn Type= 3
Dn Slope=0.001
Boundary for River Rch & Prof#=HNSCK,Main            , 6
Up Type= 0
Dn Type= 3
Dn Slope=0.001
DSS Import GetInterval= 0
DSS Import GetPeak= 0
DSS Import FillOption= 0

--- HNSCK.g01 (geometry) ---

Geom Title=Geometry
Program Version=5.07

River Reach=HNSCK           ,Main
Reach XY= 30
     2074850.954 169507.473000022076118.61700001172122.377000004
2075318.61700001173823.0709999952070175.33000001173507.273000002
2067201.71900004      174133.6622066169.77400002173419.077999994
2064435.37100002178309.0780000092064805.94600004179868.796000004
     2062067.278      181042.3312062376.43599999182344.196999997
2059508.85800004182091.1589999942058288.18700001182869.794000015
2058266.97400001 181036.20100002      2055106.59182000.871000007
2052460.82600003180962.601999998     2052753.169181970.312000006
     2051623.153183188.297000021     2051949.542 183803.05400002
2051015.87200001184219.9449999932051285.69600004184758.826000005
2049201.21100003      185283.2132047126.36500004186867.442000002
2047715.16700003190299.5600000022047049.36800003190747.355000019
2047975.75700003191741.1050000192046306.00900003194031.730000019
2047991.77300003      197573.3972047027.23100004200617.569000006
2045182.61300004201050.5119999952045262.31621087201931.329140246

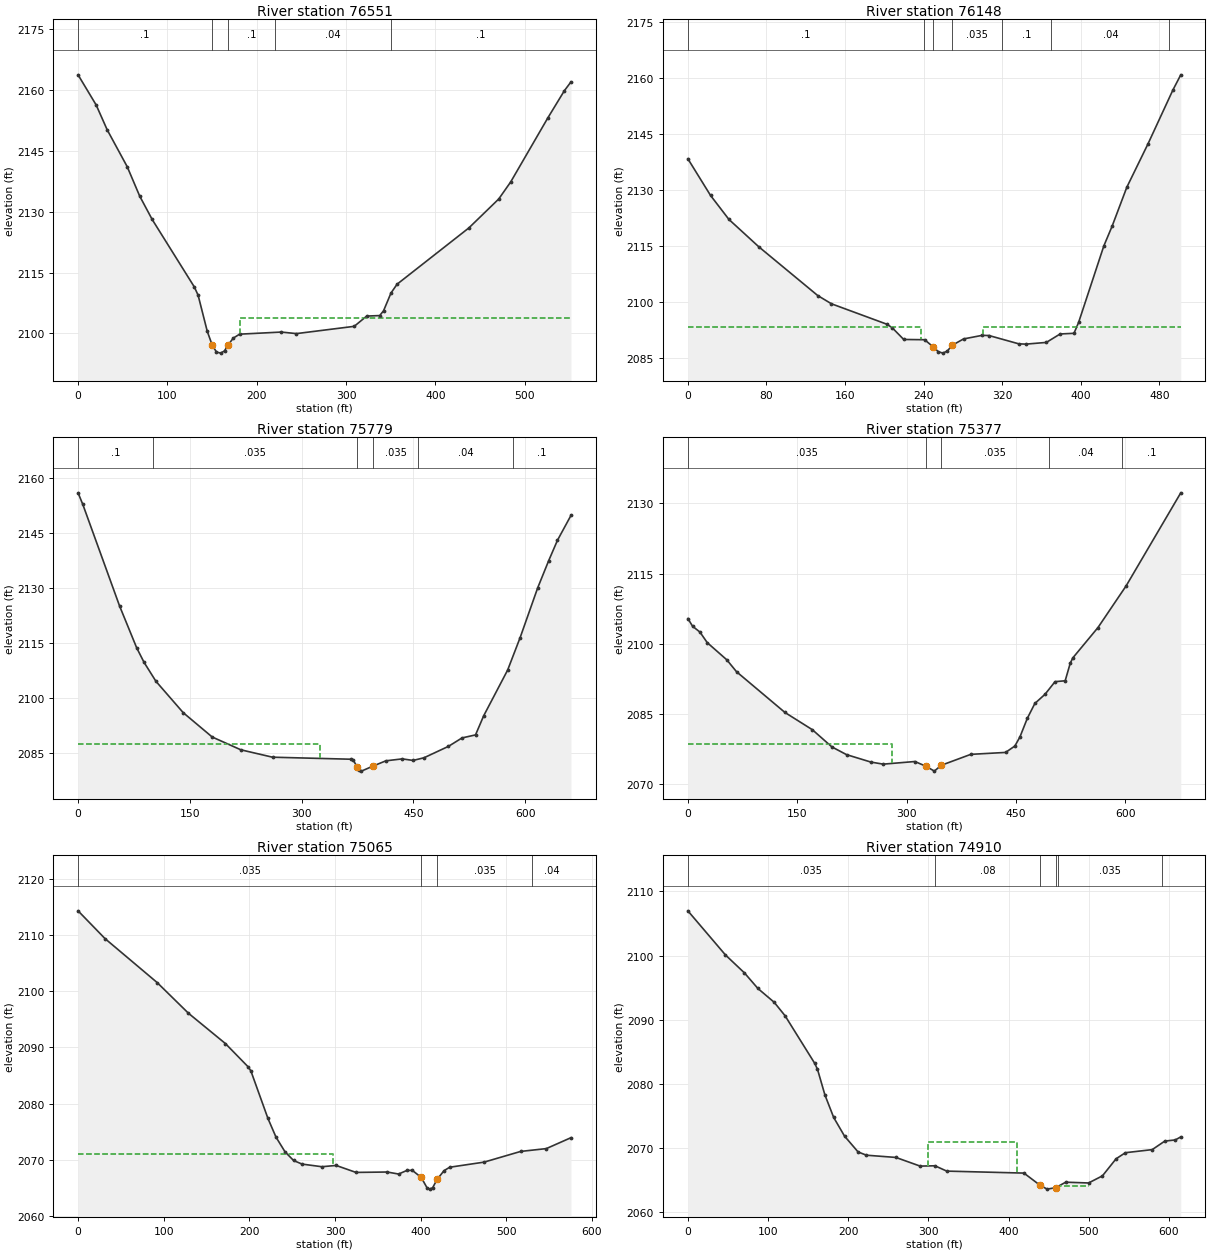
Type RM Length L Ch R = 1 ,76551   ,402.3,403,403.6
XS GIS Cut Line= 3
     2074715.619      169727.308       2075036.8      169464.722
     2075171.349       169438.68
#Sta/Elev= 30
       0 2163.71    20.3 2156.27    32.6 2150.17      55 2141.09      69 2133.84
      83 2128.07   130.1 2111.48   134.4 2109.43   144.7 2100.49   150.32097.077
     155 2095.42   159.7 2095.15     164 2095.71   167.92097.165   173.9 2098.87
   180.9 2099.82   227.5 2100.34   244.5 2099.96   309.2 2101.75   323.2 2104.28
   337.7  2104.4     342 2105.56   350.4 2109.97   357.2 2112.13   437.6    2126
     471 2133.12   484.4 2137.32   525.9 2153.07   544.5  2159.8   551.9 2161.97
#Mann= 5 ,-1 , 0
       0      .1       0   150.3    .045       0   167.9      .1       0
     220     .04       0     350      .1       0
#XS Ineff= 2 , 0
                          180.88         2103.81
Permanent Ineff=
       F       F
Bank Sta=150.3,167.9
XS Rating Curve= 0 ,0
Exp/Cntr=0.3,0.1

Type RM Length L Ch R = 1 ,76148   ,367.3,369.3,366.4
XS GIS Cut Line= 2
     2074893.571      170076.701     2075292.876      169772.881
#Sta/Elev= 30
       0 2138.48    23.1 2128.65    41.8 2122.23    72.3 2114.88   132.2 2101.84
   146.2 2099.63   202.7 2094.15   208.1 2093.19   219.7 2090.08     241 2090.01
   249.32088.182   254.9 2086.82   259.5 2086.42   264.2    2087   268.9  2088.5
   280.6 2090.22   299.3 2091.17   306.4 2091.14   336.8 2088.91     344 2088.83
   364.9 2089.29   378.9 2091.55     393 2091.73   397.7 2094.63   423.4 2115.14
   431.9 2120.47   446.8 2130.86   468.2 2142.39   493.7  2156.9   501.7 2160.96
#Mann= 7 ,-1 , 0
       0      .1       0     240    .035       0   249.3    .045       0
   268.9    .035       0     320      .1       0     370     .04       0
     490      .1       0
#XS Ineff= 2 , 0
          237.18 2093.33  300.04         2093.52
Permanent Ineff=
       F       F
Bank Sta=249.3,268.9
XS Rating Curve= 0 ,0
Exp/Cntr=0.3,0.1

Type RM Length L Ch R = 1 ,75779   ,397.2,401.9,406
XS GIS Cut Line= 4
     2074960.845      170285.034     2075117.095      170276.354
     2075455.637      170111.423     2075520.741      170000.746
#Sta/Elev= 30
       0 2155.94     6.4 2152.76    55.7 2125.08    78.7 2113.64    88.6 2109.68
   104.5 2104.53   141.1 2095.97     180 2089.33   218.4 2085.84     261 2083.82
   365.7 2083.27   369.3 2083.01   374.32081.271   376.6 2080.42   380.3 2080.02
   395.52081.371   413.1 2082.83     435 2083.36   449.6 2082.94   464.2 2083.66
   497.1 2086.78   515.3 2089.08   533.4  2089.9   544.4 2095.14   576.5 2107.59
   593.3 2116.46   616.8    2130   631.6 2137.44   643.4 2143.01   661.5 2149.78
#Mann= 6 ,-1 , 0
       0      .1       0     100    .035       0   374.3    .045       0
   395.5    .035       0  456.49     .04       0  583.07      .1       0
#XS Ineff= 2 , 0
          324.47 2087.36
Permanent Ineff=
       F       F
Bank Sta=374.3,395.5
XS Rating Curve= 0 ,0
Exp/Cntr=0.3,0.1

Type RM Length L Ch R = 1 ,75377   ,310.3,312.6,311.5
XS GIS Cut Line= 3
     2075095.394      170604.045     2075551.123      170508.558
     2075750.776      170441.284
#Sta/Elev= 30
       0 2105.41     6.5 2103.77    16.6 2102.52    26.6 2100.27    53.4 2096.61
    66.8 2094.06   133.2 2085.37   170.8 2081.69   197.6 2078.02   217.7 2076.37
   251.2 2074.78     268 2074.34   311.5  2074.9   326.92073.876   338.2 2072.85
   347.62074.091   388.2 2076.43   435.9 2076.84   448.7 2078.21   455.7 2080.17
   465.7  2084.1   476.1 2087.29     490 2089.24   503.8 2091.94   517.7 2092.13
   524.6 2095.85   528.1    2097   562.7 2103.49   601.4  2112.4   676.3 2132.24
#Mann= 5 ,-1 , 0
       0    .035       0   326.9    .045       0   347.6    .035       0
  495.63     .04       0  595.63      .1       0
#XS Ineff= 2 , 0
          279.41 2078.63
Permanent Ineff=
       F       F
Bank Sta=326.9,347.6
XS Rating Curve= 0 ,0
Exp/Cntr=0.3,0.1

Type RM Length L Ch R = 1 ,75065   ,166,154.4,145.2
XS GIS Cut Line= 2
2075059.53877983170892.3850732852075628.98377983170809.052073285
#Sta/Elev= 30
       0 2114.27    31.5 2109.33    92.3 2101.53   128.9 2096.07     172 2090.69
   198.5 2086.56   201.8 2085.81   221.7 2077.38   231.1 2074.06   241.6 2071.46
   251.6 2069.91   261.5 2069.27   284.7  2068.8   301.3 2069.03   324.5 2067.79
     361 2067.86   374.2  2067.5   383.9 2068.14   390.2 2068.16   400.72066.895
   407.4 2065.06   410.7 2064.82     414 2065.07   419.32066.571   427.3  2068.1
   433.9 2068.71   474.1 2069.62   516.8 2071.52   546.7 2072.02   575.5 2073.96
#Mann= 4 ,-1 , 0
       0    .035       0   400.7    .045       0   419.3    .035       0
     530     .04       0
#XS Ineff= 2 , 0
          297.65 2071.04
Permanent Ineff=
       F       F
Bank Sta=400.7,419.3
XS Rating Curve= 0 ,0
Exp/Cntr=0.5,0.3

Type RM Length L Ch R = 1 ,74910   ,47.8,47.6,47.4
XS GIS Cut Line= 4
     2075082.373      170954.7392075352.94602374171019.784101704
2075494.71442064170997.4358810362075620.39243346 170850.90071301
#Sta/Elev= 30
       0 2106.97    46.9 2100.09    70.6 2097.29    87.4 2094.86   107.7 2092.71
   121.2 2090.62   158.3 2083.18   161.7 2082.26     171 2078.25   181.9 2074.75
   195.4 2071.85   212.3 2069.38   222.7 2068.87   259.5 2068.52   289.7 2067.17
   308.2 2067.22   322.9 2066.39   419.2 2066.08   439.3 2064.18   448.1 2063.58
   458.72063.803   471.3 2064.66   499.8 2064.54   517.1 2065.65   534.1 2068.31
   545.8 2069.26   579.2 2069.74   594.9 2071.07   607.9 2071.25   614.8 2071.72
#Mann= 6 ,-1 , 0
       0    .035       0  308.28     .08       0   439.3    .045       0
   458.7     .08       0   461.8    .035       0   591.8     .04       0
#XS Ineff= 3 ,-1
     300     410    2071     410     438    2064     460     500    2064
Permanent Ineff=
       F       F       F
Bank Sta=439.3,458.7
XS Rating Curve= 0 ,0
Exp/Cntr=0.5,0.3

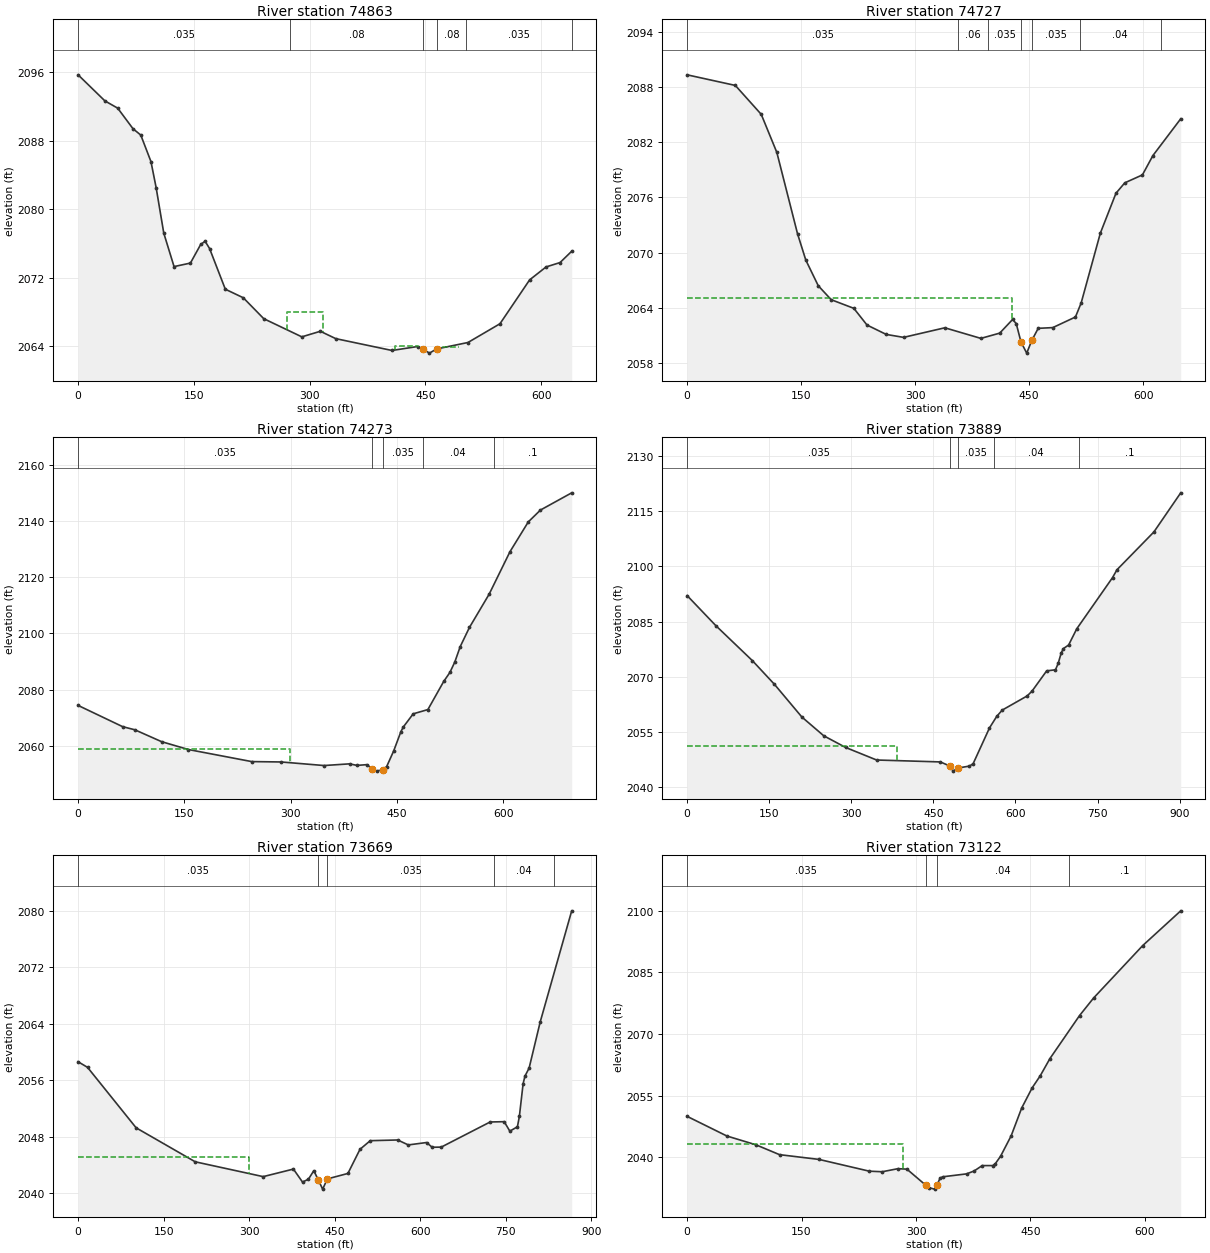
Type RM Length L Ch R = 1 ,74863   ,129.4,135.3,139.3
XS GIS Cut Line= 4
     2075110.151      171024.183     2075361.887      171063.246
2075527.48073779171033.0890983742075665.83542936 170866.80364747
#Sta/Elev= 30
       0 2095.69    34.7 2092.65    51.3  2091.8    71.2 2089.39    81.2 2088.66
    94.4 2085.56   101.1 2082.52     111 2077.21   124.3 2073.31   145.5 2073.72
   158.8 2075.89   164.5 2076.27   170.3 2075.42   190.7 2070.67     214 2069.67
   240.5 2067.23   289.8 2065.11   313.8 2065.76   333.8  2064.9   406.6 2063.52
   439.7 2063.98   446.7 2063.68   455.1 2063.21   464.42063.696     505 2064.45
   546.5 2066.64   584.9 2071.76   606.2 2073.27   624.3 2073.78   639.4  2075.1
#Mann= 6 ,-1 , 0
       0    .035       0  274.75     .08       0   446.7    .045       0
   464.4     .08       0  503.07    .035       0  639.38     .04       0
#XS Ineff= 3 ,-1
     270     317    2068  410.94  440.942064.074  472.97  492.972063.963
Permanent Ineff=
       F       F       F
Bank Sta=446.7,464.4
XS Rating Curve= 0 ,0
Exp/Cntr=0.5,0.3

Type RM Length L Ch R = 1 ,74727   ,450.5,454.1,455.5
XS GIS Cut Line= 4
2075211.28927524 171174.193082622075419.62227524 171232.78708262
2075703.91127524 171072.196082622075793.98570655 171015.69919278
#Sta/Elev= 30
       0 2089.31    63.4 2088.16    97.5 2085.02     118 2080.89   145.2 2072.07
   156.1 2069.21   172.5 2066.42   189.5 2064.91   219.3 2063.97   236.6 2062.16
   261.9 2061.14   284.7 2060.82     339 2061.86   386.4 2060.71   411.2 2061.28
   428.1 2062.76   432.9 2062.32   439.2 2060.31   446.7 2059.11   453.52060.505
   461.8  2061.8     481 2061.88   510.8 2063.03   518.3 2064.55   543.6 2072.14
   564.1 2076.46   575.7 2077.59   598.9 2078.45   612.7 2080.55   649.3 2084.54
#Mann= 7 ,-1 , 0
       0    .035       0  356.42     .06       0  396.42    .035       0
   439.2    .045       0   453.5    .035       0  516.42     .04       0
  622.93     .06       0
#XS Ineff= 2 , 0
          427.78 2065.07
Permanent Ineff=
       F       F
Bank Sta=439.2,453.5
XS Rating Curve= 0 ,0
Exp/Cntr=0.3,0.1

Type RM Length L Ch R = 1 ,74273   ,381,384.6,384.4
XS GIS Cut Line= 3
     2075415.706      171485.772     2075660.604      171562.264
     2076078.684      171424.555
#Sta/Elev= 30
       0  2074.4    62.9 2066.84    80.1 2065.73   117.9  2061.5   155.7 2058.71
   245.1 2054.42   286.5 2054.29   347.2 2053.02   383.2 2053.62   393.6 2053.07
   407.4 2053.33   414.7 2051.96   421.2 2051.03   429.72051.546   435.5 2052.63
   445.4 2058.19   455.7 2065.12   459.2 2066.79     473 2071.41   493.7 2072.92
   516.1 2082.95   524.8 2086.13   531.7 2089.83   539.4 2095.34   552.4 2102.15
   580.1 2113.92   609.6 2129.07   635.4 2139.65   652.6 2143.88   696.7    2150
#Mann= 5 ,-1 , 0
       0    .035       0   414.7    .045       0   429.7    .035       0
  486.57     .04       0  586.57      .1       0
#XS Ineff= 2 , 0
          299.31 2058.91
Permanent Ineff=
       F       F
Bank Sta=414.7,429.7
XS Rating Curve= 0 ,0
Exp/Cntr=0.3,0.1

Type RM Length L Ch R = 1 ,73889   ,224.9,219.4,212.9
XS GIS Cut Line= 4
     2075332.373      171843.411     2075617.095      171898.966
     2075908.762      171850.355     2076122.635      171617.362
#Sta/Elev= 30
       0 2092.09    52.5 2083.92   119.4  2074.4   159.5    2068   209.6 2059.12
   249.7 2054.01   289.8 2050.83   346.3 2047.43   462.8 2046.91     480  2045.8
   486.1 2044.41     4952045.251     516 2045.78   522.7 2046.43   552.6 2056.15
   565.9  2059.3   575.9 2060.99   621.5 2064.84   630.4 2066.15   657.1 2071.65
   673.2 2071.93   678.1 2073.66   683.8 2076.56   687.8 2077.71   697.2 2078.66
     712 2083.05   777.4 2096.96   785.6 2099.11   853.1 2109.38   902.1    2120
#Mann= 5 ,-1 , 0
       0    .035       0     480    .045       0     495    .035       0
  560.09     .04       0  715.78      .1       0
#XS Ineff= 2 , 0
          383.05 2051.18
Permanent Ineff=
       F       F
Bank Sta=480,495
XS Rating Curve= 0 ,0
Exp/Cntr=0.3,0.1

Type RM Length L Ch R = 1 ,73669   ,533.5,547.3,556.2
XS GIS Cut Line= 4
      2075561.54      172148.966     2075724.698      172195.388
     2076176.179      171840.458     2076196.313      171720.311
#Sta/Elev= 30
       0 2058.63    16.6 2057.83   101.8 2049.27   205.4 2044.46   324.6 2042.36
   377.6 2043.43   393.6 2041.59   403.9 2041.99   413.4  2043.2   420.92041.953
   428.9 2040.59   437.22042.039   473.2 2042.81   494.4 2046.23   512.4 2047.45
   560.5 2047.55   579.1 2046.85   611.2 2047.19   620.9 2046.52   636.9 2046.54
   722.7  2050.1   747.3 2050.14   757.2  2048.8   770.5 2049.42   773.9 2050.88
   780.5 2055.53   783.8 2056.61     791 2057.73   810.5 2064.28   865.7    2080
#Mann= 5 ,-1 , 0
       0    .035       0   420.9    .045       0   437.2    .035       0
  729.63     .04       0  833.92      .1       0
#XS Ineff= 2 , 0
             300 2045.13
Permanent Ineff=
       F       F
Bank Sta=420.9,437.2
XS Rating Curve= 0 ,0
Exp/Cntr=0.3,0.1

Type RM Length L Ch R = 1 ,73122   ,224,226.3,227.8
XS GIS Cut Line= 2
     2075665.706      172291.328     2076280.983       172491.47
#Sta/Elev= 30
       0 2049.98    52.1  2045.2    90.3 2043.05   121.1 2040.66   172.9  2039.5
   238.7 2036.64   255.7  2036.5   276.4 2037.25   288.1 2037.13   312.52033.271
   316.8 2032.62   324.3 2032.27   327.52033.287   331.6 2034.95     335 2035.27
   366.2 2035.98     376 2036.67   386.8    2038   400.6    2038     404 2038.47
   410.9 2040.29   424.7 2045.23   438.5    2052   452.3 2056.94   462.7 2059.81
   475.6 2064.06   514.4 2074.52   532.8 2078.79   597.2 2091.55     647    2100
#Mann= 4 ,-1 , 0
       0    .035       0   312.5    .045       0   327.5     .04       0
     500      .1       0
#XS Ineff= 2 , 0
          282.83 2043.16
Permanent Ineff=
       F       F
Bank Sta=312.5,327.5
XS Rating Curve= 0 ,0
Exp/Cntr=0.3,0.1

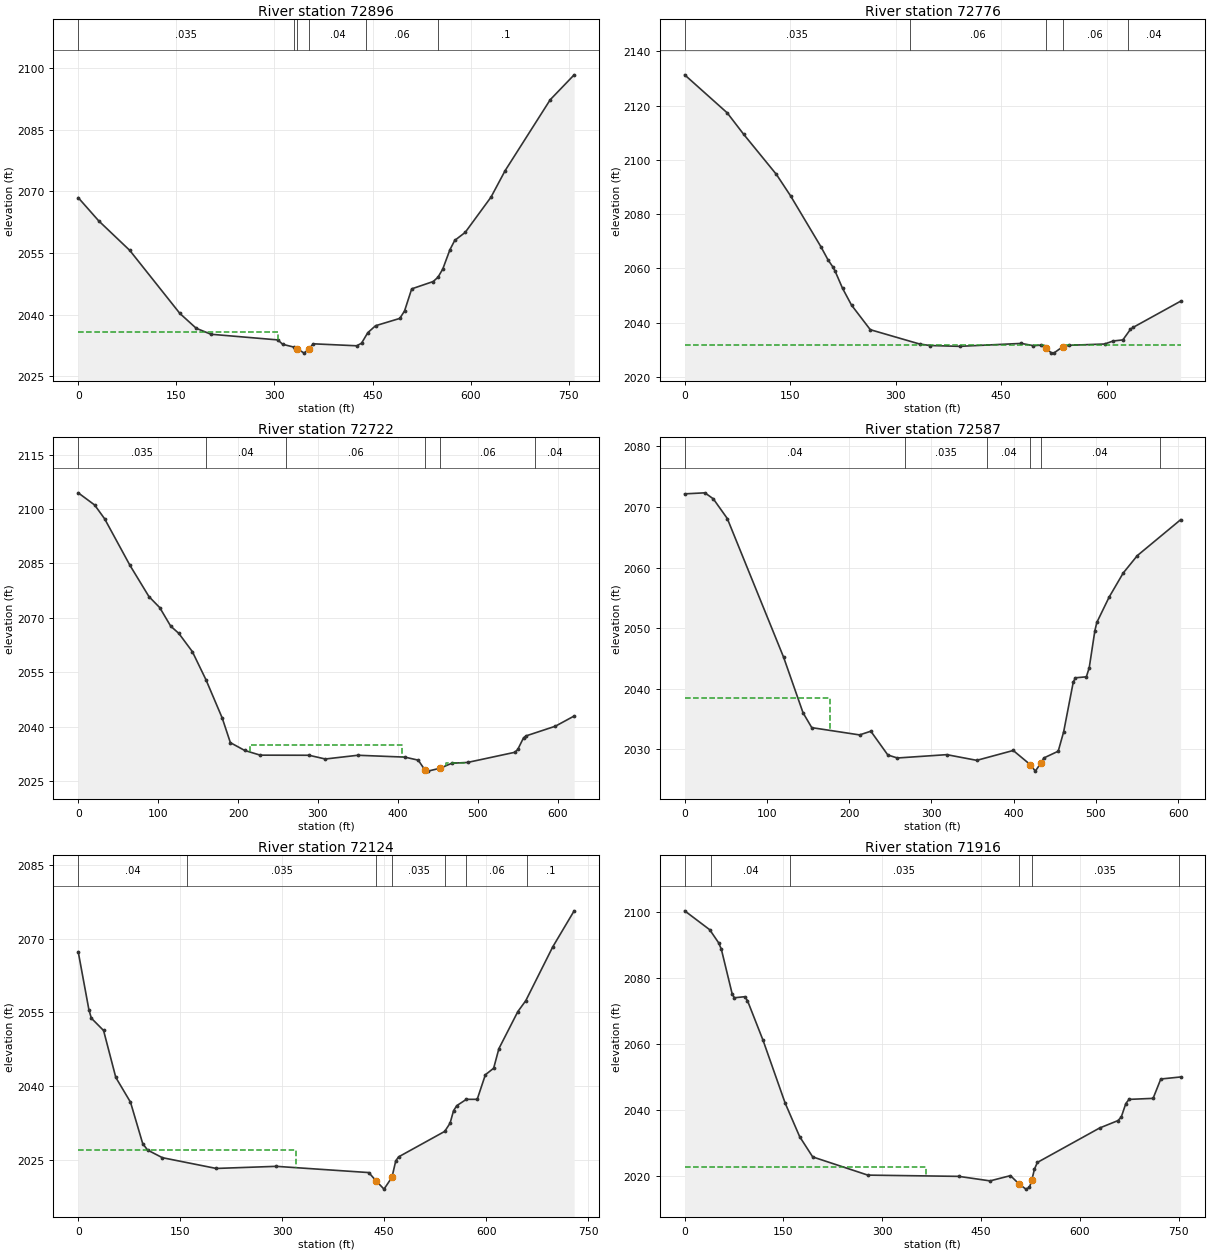
Type RM Length L Ch R = 1 ,72896   ,118.8,119.4,120.1
XS GIS Cut Line= 3
     2075578.901      172444.105     2076110.151      172704.522
     2076276.817      172707.994
#Sta/Elev= 30
       0 2068.49    31.3 2062.84    78.8 2055.64   155.5 2040.26   180.4 2036.66
     203  2035.2   305.3 2033.82   312.6 2032.75     330 2032.06   334.72031.689
   345.5  2030.6     353 2031.65   359.4 2032.87   425.9 2032.39   433.2 2033.02
   442.8 2035.59   454.7 2037.28   491.7 2039.06     499 2040.89   509.9 2046.26
   542.8 2048.05   550.1  2049.1   557.4 2051.09   568.4 2055.82   575.7 2058.07
   591.7 2060.02   631.1  2068.6   652.8 2075.08   721.7 2092.35   758.3 2098.42
#Mann= 6 ,-1 , 0
       0    .035       0     330     .04       0   334.7    .045       0
     353     .04       0     440     .06       0     550      .1       0
#XS Ineff= 2 , 0
          305.35 2035.78
Permanent Ineff=
       F       F
Bank Sta=334.7,353
XS Rating Curve= 0 ,0
Exp/Cntr=0.5,0.3

Type RM Length L Ch R = 1 ,72776   ,54.5,54.6,54.6
XS GIS Cut Line= 3
     2075367.095      172770.4942075829.33364317172685.956681967
2076042.24834972172785.895787978
#Sta/Elev= 30
       0 2131.37    60.5 2117.34    83.8 2109.47   130.5 2094.62   150.5 2086.76
   193.9 2067.89   203.9 2063.09   210.5  2060.6   213.9 2058.97   224.4 2052.67
   237.2 2046.46   263.9 2037.39   333.9 2032.12   348.5 2031.56   390.8 2031.25
   478.6 2032.33   495.9  2031.5     507  2031.7   510.7 2031.49   513.22030.814
   521.5 2028.75   525.5 2028.89   537.22031.047   546.9 2031.64     597 2032.11
   609.3 2033.23     623 2033.63   633.8 2037.54   637.5 2038.23   705.1  2047.9
#Mann= 5 ,-1 , 0
       0    .035       0     320     .06       0   513.2    .045       0
   537.2     .06       0  629.91     .04       0
#XS Ineff= 2 , 0
          509.51 2031.84  540.09         2031.84
Permanent Ineff=
       F       F
Bank Sta=513.2,537.2
XS Rating Curve= 0 ,0
Exp/Cntr=0.5,0.3

Type RM Length L Ch R = 1 ,72722   ,135.8,134.4,131.2
XS GIS Cut Line= 3
     2075429.595      172836.4662075807.89848416172735.940515844
2076015.38097868172833.163515844
#Sta/Elev= 30
       0 2104.45    20.5 2101.11      33 2097.32    64.8 2084.46    88.5 2075.88
   102.1 2072.82   115.7 2067.75   125.9 2065.74   142.8 2060.73     160 2052.91
   180.2 2042.44   190.4 2035.65   208.3 2033.51   227.7 2032.21   288.8 2032.18
   309.2 2031.15   349.9 2032.18   408.7 2031.67   425.5 2030.83   433.92028.118
   437.7 2027.81   453.1 2028.63   467.5 2029.98   487.2  2030.2   546.4    2033
     550 2033.77   557.3    2037   560.9 2037.55   597.1 2040.18   620.6 2042.99
#Mann= 6 ,-1 , 0
       0    .035       0     160     .04       0     260     .06       0
   433.9    .045       0   453.1     .06       0  571.43     .04       0
#XS Ineff= 3 ,-1
     215     405    2035     405     425    2030     460     485    2030
Permanent Ineff=
       F       F       F
Bank Sta=433.9,453.1
XS Rating Curve= 0 ,0
Exp/Cntr=0.5,0.3

Type RM Length L Ch R = 1 ,72587   ,455.1,463.1,463.2
XS GIS Cut Line= 3
     2075422.651      172885.0782075631.37782499172824.032439681
2075998.23876339172942.249254083
#Sta/Elev= 30
       0 2072.16    24.6 2072.33    34.8 2071.34    51.8 2068.09   120.3 2045.17
   143.9 2036.01   154.5 2033.56   212.6 2032.36   226.3 2032.97     247 2029.04
   258.6 2028.55   318.6  2029.1   355.1 2028.16   399.4 2029.79     4202027.465
   426.3 2026.38   432.9 2027.69   436.6 2028.55   454.1 2029.67   460.7 2032.86
   472.4 2041.09     475 2041.79   488.3 2041.95   491.8 2043.45   498.6 2049.51
     501 2050.92   515.9 2055.09   533.1 2059.09   550.3 2061.97   602.9 2067.89
#Mann= 6 ,-1 , 0
       0     .04       0  267.47    .035       0  367.47     .04       0
     420    .045       0   432.9     .04       0  577.47      .1       0
#XS Ineff= 2 , 0
          177.05  2038.5
Permanent Ineff=
       F       F
Bank Sta=420,432.9
XS Rating Curve= 0 ,0
Exp/Cntr=0.3,0.1

Type RM Length L Ch R = 1 ,72124   ,206.8,207.9,207
XS GIS Cut Line= 3
     2075367.095      172898.966      2075499.04      173190.633
     2075835.845      173423.272
#Sta/Elev= 30
       0 2067.32    15.7 2055.54    19.3  2053.8    37.3 2051.29    55.3 2041.73
    76.9  2036.7    94.9 2028.25   102.1 2026.95   123.8  2025.4     203 2023.21
   291.3 2023.64   427.4 2022.37   438.12020.698   449.8    2019   461.52021.412
   467.1 2024.76   471.3 2025.57   539.1 2030.75     547 2032.43   552.1 2034.96
   556.8 2035.99     571 2037.28   586.9 2037.28   598.9 2042.28   611.1 2043.61
   618.8  2047.6   646.7 2055.15   658.3 2057.35     698 2068.31   729.5 2075.65
#Mann= 7 ,-1 , 0
       0     .04       0     160    .035       0   438.1    .045       0
   461.5    .035       0  540.12     .04       0  570.12     .06       0
  660.12      .1       0
#XS Ineff= 2 , 0
          319.85 2027.02
Permanent Ineff=
       F       F
Bank Sta=438.1,461.5
XS Rating Curve= 0 ,0
Exp/Cntr=0.3,0.1

Type RM Length L Ch R = 1 ,71916   ,249.4,249.5,247.4
XS GIS Cut Line= 2
      2075055.62      173138.038     2075679.364      173560.121
#Sta/Elev= 30
       0 2100.43      38  2094.7    51.7 2090.69    55.7 2088.76    72.2 2075.18
    75.5 2074.06    91.1 2074.38    95.3 2073.23   119.1 2061.11   152.5 2042.15
   174.6 2031.94   194.4 2025.79   278.1 2020.27   416.2 2019.89   463.7 2018.52
   494.7 2020.11   507.12017.715   518.1 2016.02   523.5 2016.55   527.22018.787
   531.1 2022.08   535.6 2024.12   630.1 2034.56   657.8 2036.79   662.9 2037.85
   669.9 2041.98   674.7 2043.24   711.3 2043.55     723 2049.42   753.1 2050.04
#Mann= 6 ,-1 , 0
       0    .035       0      40     .04       0     160    .035       0
   507.1    .045       0   527.2    .035       0     750     .06       0
#XS Ineff= 2 , 0
          365.87 2022.72
Permanent Ineff=
       F       F
Bank Sta=507.1,527.2
XS Rating Curve= 0 ,0
Exp/Cntr=0.3,0.1

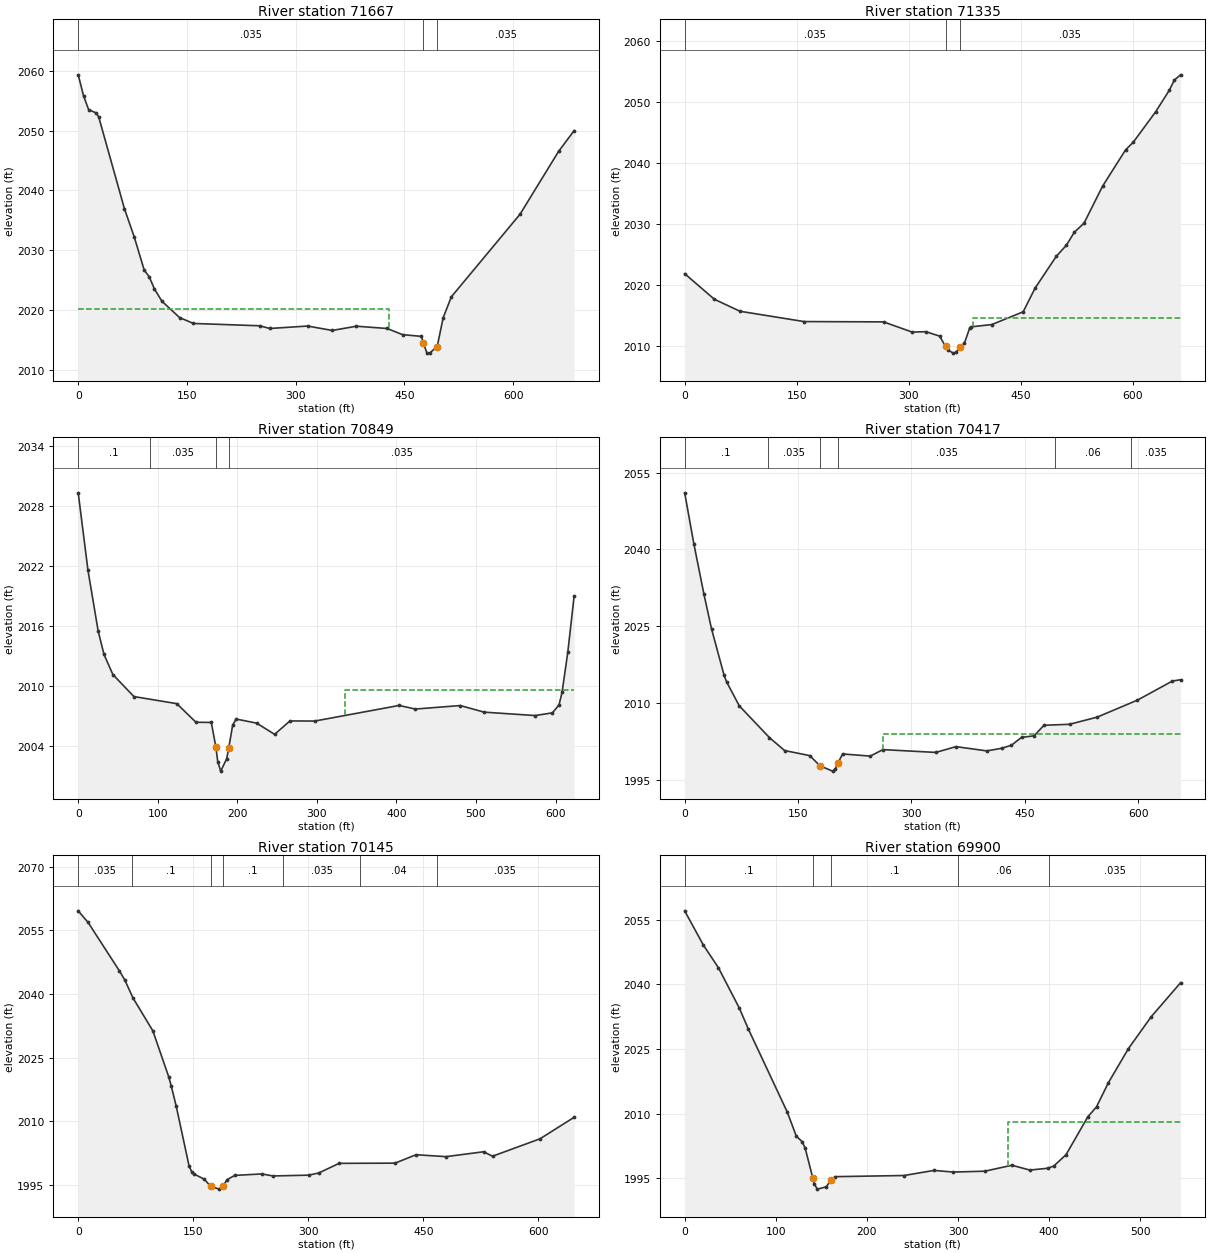
Type RM Length L Ch R = 1 ,71667   ,322.2,332.2,338.5
XS GIS Cut Line= 4
     2074997.724      173342.663     2075040.553      173462.321
     2075395.012      173655.845     2075546.279      173679.397
#Sta/Elev= 30
       0 2059.32     7.4  2055.8    14.4 2053.49    24.8 2052.95    28.3 2052.27
    63.7 2036.95    77.1 2032.28      91 2026.69      98 2025.54     105 2023.55
   115.4 2021.47   139.9 2018.73     159 2017.75   250.6 2017.36   264.1 2016.91
   316.4 2017.32   350.3 2016.58   383.7 2017.29     426 2016.91   447.3 2015.88
   473.4 2015.59   476.22014.413   480.9 2012.82   484.6 2012.79   495.1 2013.88
   503.3 2018.68   514.6  2022.2   609.4 2036.02   662.5 2046.51     684    2050
#Mann= 3 ,-1 , 0
       0    .035       0   476.2    .045       0   495.1    .035       0
#XS Ineff= 2 , 0
          428.79 2020.16
Permanent Ineff=
       F       F
Bank Sta=476.2,495.1
XS Rating Curve= 0 ,0
Exp/Cntr=0.3,0.1

Type RM Length L Ch R = 1 ,71335   ,484.2,485.4,483.9
XS GIS Cut Line= 4
      2074963.16      173541.183     2075147.852      173739.897
     2075238.522      173919.673     2075421.493      173975.211
#Sta/Elev= 30
       0 2021.93    39.7 2017.74      74 2015.77   159.9 2014.08   266.2 2014.03
   304.5 2012.36   322.9 2012.42   341.3  2011.7   349.22010.017   352.3 2009.42
   359.7 2008.91   363.3 2009.04   368.4 2009.86   374.4 2010.52   381.7 2013.08
   383.6 2013.22   411.1 2013.59   453.1 2015.68   469.1 2019.56   497.5 2024.78
     511 2026.59   521.7 2028.73   534.6  2030.2   559.4 2036.26   590.3 2042.23
   600.6 2043.48   630.5 2048.46   648.6 2051.95   655.6 2053.67   663.9 2054.51
#Mann= 3 ,-1 , 0
       0    .035       0   349.2    .045       0   368.4    .035       0
#XS Ineff= 2 , 0
                          386.41          2014.7
Permanent Ineff=
       F       F
Bank Sta=349.2,368.4
XS Rating Curve= 0 ,0
Exp/Cntr=0.3,0.1

Type RM Length L Ch R = 1 ,70849   ,427.3,432,436.6
XS GIS Cut Line= 2
     2074629.827      173751.252     2074935.382      174294.655
#Sta/Elev= 30
       0 2029.34    12.3 2021.57    25.1 2015.51    32.4 2013.17    43.6 2011.16
      70 2008.96   123.9 2008.25     148 2006.39   167.3 2006.37   173.12003.885
   175.4 2002.45   179.1  2001.5   186.6 2002.73   189.32003.857   194.2 2006.12
   198.6 2006.71   224.3  2006.3   246.9 2005.18   266.1 2006.52   297.4 2006.51
   403.4 2008.07   423.8 2007.71   480.2 2008.06   510.3  2007.4   574.3 2007.06
   596.1 2007.33   604.4 2008.13   608.2 2009.38   615.4 2013.39   623.4 2019.03
#Mann= 4 ,-1 , 0
       0      .1       0      90    .035       0   173.1    .045       0
   189.3    .035       0
#XS Ineff= 2 , 0
                          335.15         2009.62
Permanent Ineff=
       F       F
Bank Sta=173.1,189.3
XS Rating Curve= 0 ,0
Exp/Cntr=0.3,0.1

Type RM Length L Ch R = 1 ,70417   ,271.2,271.8,273.1
XS GIS Cut Line= 3
      2074275.66      173836.322     2074383.299      174428.336
     2074411.077      174475.211
#Sta/Elev= 30
       0 2051.08    12.2 2041.06    25.5 2031.24    35.5 2024.48    52.2 2015.36
    55.6 2014.06    72.2 2009.42   112.2 2003.19   132.2 2000.67   165.6 1999.67
   178.8  1997.7   195.6 1996.64   198.9 1996.96   202.81998.217   208.9    2000
   245.6 1999.58   262.3 2000.85   332.3  2000.3     359 2001.43   399.7  2000.6
   419.2  2001.1   432.4 2001.71   445.7 2003.24   462.4 2003.55   475.3 2005.61
   509.2  2005.8   545.7  2007.2   599.1 2010.53   645.3 2014.26   656.2 2014.52
#Mann= 6 ,-1 , 0
       0      .1       0     110    .035       0   178.8    .045       0
   202.8    .035       0     490     .06       0     590    .035       0
#XS Ineff= 2 , 0
                          262.65         2003.84
Permanent Ineff=
       F       F
Bank Sta=178.8,202.8
XS Rating Curve= 0 ,0
Exp/Cntr=0.3,0.1

Type RM Length L Ch R = 1 ,70145   ,241.4,245.3,247.7
XS GIS Cut Line= 3
     2074055.174      173858.891     2074029.132      173952.641
     2074108.993      174496.044
#Sta/Elev= 30
       0  2059.6    12.9 2056.86    53.7 2045.46    60.7 2043.32    71.4 2039.08
    97.3 2031.34   117.9 2020.55   121.2 2018.41   127.8 2013.56   144.4 1999.61
   147.7 1998.21     151 1997.61   164.3 1996.41   172.51994.735   183.9 1994.06
   188.61994.783   194.1 1996.29   204.1 1997.29   239.4 1997.64   253.8 1997.16
   300.3 1997.35   313.5 1997.86   340.1 2000.13     413 2000.18   440.4 2002.16
   479.5 2001.71   528.5 2002.86   540.1 2001.81     602 2005.91   646.5 2010.98
#Mann= 7 ,-1 , 0
       0    .035       0      70      .1       0   172.5    .045       0
   188.6      .1       0   267.3    .035       0   367.3     .04       0
   467.3    .035       0
Bank Sta=172.5,188.6
XS Rating Curve= 0 ,0
Exp/Cntr=0.3,0.1

Type RM Length L Ch R = 1 ,69900   ,488.5,493.3,495.9
XS GIS Cut Line= 3
     2073808.646      173919.655     2073784.341      174334.586
     2073716.632      174443.961
#Sta/Elev= 30
       0 2057.05    20.6 2049.07      37 2043.87      60 2034.48    69.9 2029.63
   112.6 2010.38   122.5  2004.8     129  2003.5   132.3 2001.98   140.7    1995
   142.2 1993.78   145.5 1992.51   155.3 1993.04   160.81994.645   165.2  1995.4
   240.8 1995.67   273.6 1996.85   294.6 1996.47   329.5 1996.67   359.1 1998.05
   378.8 1996.93   398.5 1997.35   405.1 1997.88   418.5 2000.48   442.4 2009.26
     452  2011.6     465 2017.18     487 2025.09   511.9 2032.46   544.3 2040.39
#Mann= 5 ,-1 , 0
       0      .1       0   140.7    .045       0   160.8      .1       0
     300     .06       0     400    .035       0
#XS Ineff= 2 , 0
                          354.78            2008
Permanent Ineff=
       F       F
Bank Sta=140.7,160.8
XS Rating Curve= 0 ,0
Exp/Cntr=0.3,0.1

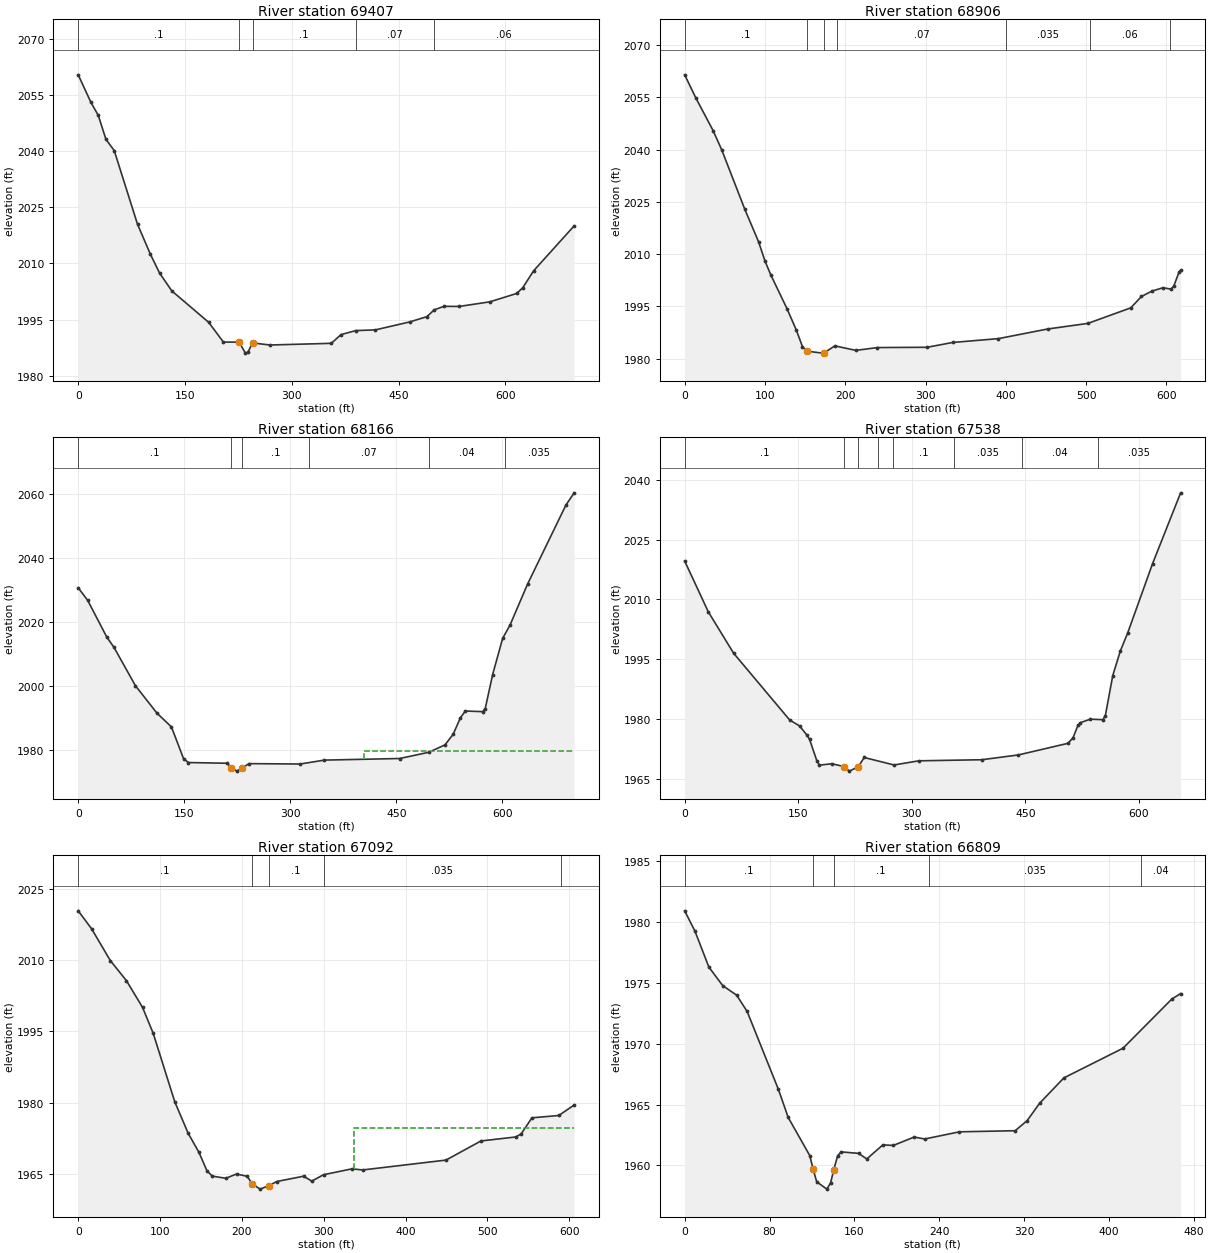
Type RM Length L Ch R = 1 ,69407   ,497.1,501,497.5
XS GIS Cut Line= 3
     2073394.684      173749.234     2073219.336      174299.581
     2073308.646      174377.988
#Sta/Elev= 30
       0 2060.41    17.9 2053.03    28.2 2049.56    38.9 2043.19    50.6 2040.16
    83.3 2020.47   101.5 2012.41   114.3 2007.42   131.5 2002.66   183.2 1994.28
   203.9 1988.99     2261988.971   234.8 1986.04   238.3 1986.25   244.81988.767
   269.3 1988.21   355.4 1988.66   369.1 1990.99   389.8 1992.06   417.3 1992.25
   465.6 1994.38   489.7 1995.79     500 1997.61   513.8 1998.55     535 1998.51
   578.1 1999.75   615.9 2001.99   624.3 2003.52   639.6 2008.05   696.5 2020.05
#Mann= 5 ,-1 , 0
       0      .1       0     226    .045       0   244.8      .1       0
     390     .07       0     500     .06       0
Bank Sta=226,244.8
XS Rating Curve= 0 ,0
Exp/Cntr=0.3,0.1

Type RM Length L Ch R = 1 ,68906   ,745,740,727
XS GIS Cut Line= 3
     2073003.337      173655.229     2072818.673      174070.389
     2072789.302      174230.956
#Sta/Elev= 30
       0 2061.51    13.8 2054.91    35.4 2045.49    46.2 2039.92    74.9 2022.87
      92 2013.56     100 2008.01   107.5 2003.91   127.4 1994.34   138.8  1988.3
   146.7 1983.42   152.21982.118   171.8 1981.56   173.21981.562     187 1983.65
   213.1 1982.35   240.1 1983.16   301.9 1983.24   333.7 1984.62   390.8 1985.73
   451.9 1988.49   502.1  1990.1   555.5 1994.56   568.8 1997.83   581.7 1999.37
   595.5 2000.34   605.5 1999.96   608.9 2000.73   615.5 2004.75   617.6 2005.39
#Mann= 7 ,-1 , 0
       0      .1       0   152.2    .045       0   173.2      .1       0
     190     .07       0     400    .035       0  504.38     .06       0
  604.38    .035       0
Bank Sta=152.2,173.2
XS Rating Curve= 0 ,0
Exp/Cntr=0.3,0.1

Type RM Length L Ch R = 1 ,68166   ,621.9,628,626.4
XS GIS Cut Line= 4
     2072294.757      173549.863     2072266.979      173662.711
     2072393.716      174070.697     2072336.424      174218.266
#Sta/Elev= 30
       0 2030.68    13.4 2026.77    40.5 2015.27    50.6  2012.1      81 2000.11
   111.4 1991.57   131.9 1987.26   149.1 1977.32     156 1976.14     211 1975.92
   216.7 1974.41   224.7 1973.46   231.71974.455   241.9  1975.8     314 1975.68
   348.4  1976.9   454.9  1977.4   496.1 1979.35   518.9 1981.65   530.5 1984.96
   540.8 1990.12   547.7 1992.22   572.4 1992.03   575.9    1993   586.4 2003.62
   600.5 2014.88   611.1 2019.12   635.7  2031.8     690 2056.49   701.7 2060.33
#Mann= 6 ,-1 , 0
       0      .1       0   216.7    .045       0   231.7      .1       0
  326.22     .07       0  496.22     .04       0  603.43    .035       0
#XS Ineff= 2 , 0
                          404.91         1979.73
Permanent Ineff=
       F       F
Bank Sta=216.7,231.7
XS Rating Curve= 0 ,0
Exp/Cntr=0.3,0.1

Type RM Length L Ch R = 1 ,67538   ,443.8,446,444
XS GIS Cut Line= 3
     2071827.743      173508.197     2071740.938      173612.363
     2071721.841      174131.461
#Sta/Elev= 30
       0 2019.62    31.1 2006.94    64.6 1996.56   138.6 1979.86   151.8 1978.34
   161.6 1976.03   164.9 1975.01   174.7 1969.56     178 1968.54   194.3  1968.9
   210.71968.189   217.4 1967.05   229.31968.137   237.1 1970.46   276.5 1968.59
   309.3 1969.63   392.3  1969.9   440.7  1971.1   506.3 1974.01   512.9  1975.4
   519.5 1978.54   522.7 1979.19   535.9 1980.05   552.3 1979.92   555.6 1980.95
   565.4 1990.96   575.3 1997.07   585.1 2001.62   617.9 2018.94     655 2036.68
#Mann= 8 ,-1 , 0
       0      .1       0   210.7    .045       0   229.3      .1       0
  255.59    .035       0  275.59      .1       0  355.59    .035       0
  445.59     .04       0  545.59    .035       0
Bank Sta=210.7,229.3
XS Rating Curve= 0 ,0
Exp/Cntr=0.3,0.1

Type RM Length L Ch R = 1 ,67092   ,281.7,282.7,280.4
XS GIS Cut Line= 2
     2071319.063      173431.808     2071329.479      174037.711
#Sta/Elev= 30
       0 2020.33    16.3 2016.57    39.2 2009.89    58.9 2005.66    78.6 2000.05
    91.7 1994.56     118  1980.2   134.4 1973.58   147.5  1969.6   157.4 1965.68
   163.9 1964.59   180.4 1964.14   193.5 1965.04   206.6 1964.54   212.61962.973
   222.3 1961.86   232.61962.568   242.7 1963.46   275.5 1964.58   285.3 1963.54
   299.8 1964.89   334.5 1966.12   347.7 1965.89   449.4 1967.96   492.1 1971.98
   534.7 1972.82   541.3 1973.48   554.4 1976.84   587.2 1977.33     606 1979.53
#Mann= 5 ,-1 , 0
       0      .1       0   212.6    .045       0   232.6      .1       0
     300    .035       0     590     .04       0
#XS Ineff= 2 , 0
                          336.74         1974.75
Permanent Ineff=
       F       F
Bank Sta=212.6,232.6
XS Rating Curve= 0 ,0
Exp/Cntr=0.3,0.1

Type RM Length L Ch R = 1 ,66809   ,307,304.6,301.4
XS GIS Cut Line= 2
2071056.55108588173497.4736718122071068.64099549173964.950176581
#Sta/Elev= 30
       0 1980.92     9.7 1979.25    22.8  1976.3    35.9 1974.77      49 1973.99
    58.9 1972.65    88.4 1966.24    97.6 1963.94     118  1960.8   121.1 1959.68
   124.5 1958.65   134.1 1958.05   137.6 1958.57   140.5 1959.62   144.2 1960.79
   147.5 1961.11   163.9 1960.99   171.7 1960.53   186.9 1961.69   196.7 1961.64
   216.4 1962.33   226.3 1962.17   259.1 1962.76   311.6 1962.85   322.9 1963.68
   334.6  1965.1   357.5 1967.19   413.3 1969.63   459.3 1973.67   467.6 1974.12
#Mann= 5 ,-1 , 0
       0      .1       0   121.1    .045       0   140.5      .1       0
     230    .035       0     430     .04       0
Bank Sta=121.1,140.5
XS Rating Curve= 0 ,0
Exp/Cntr(USF)=0,0
Exp/Cntr=0.3,0.1