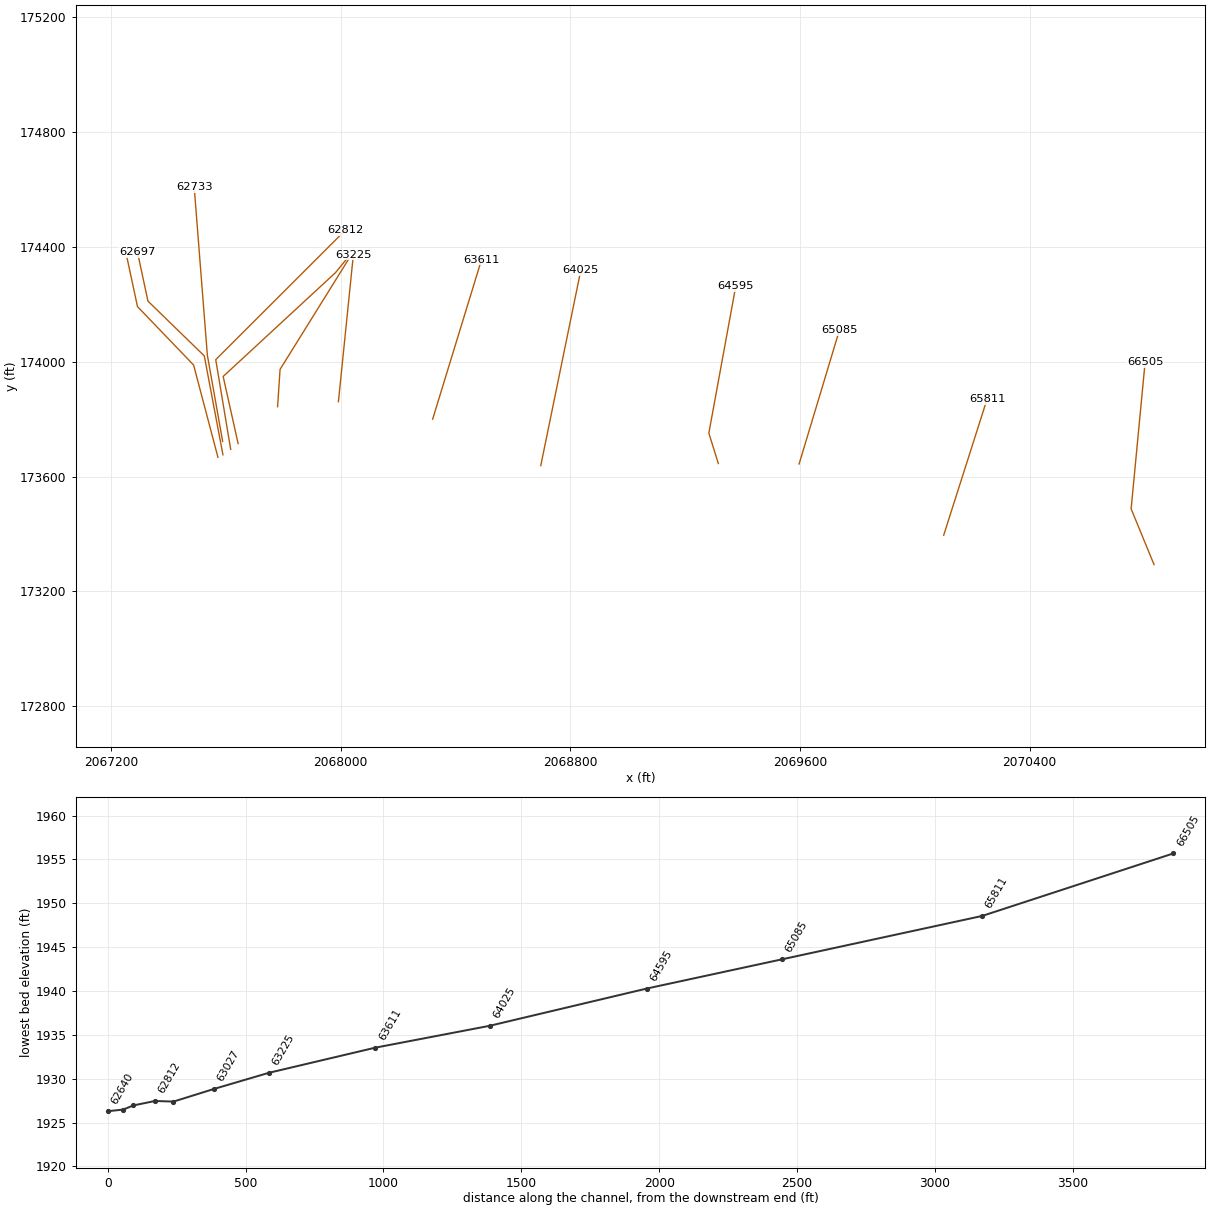
HEC-RAS study HNSCK.prj: HNSCK

--- HNSCK.g01 (geometry) --- (continued)

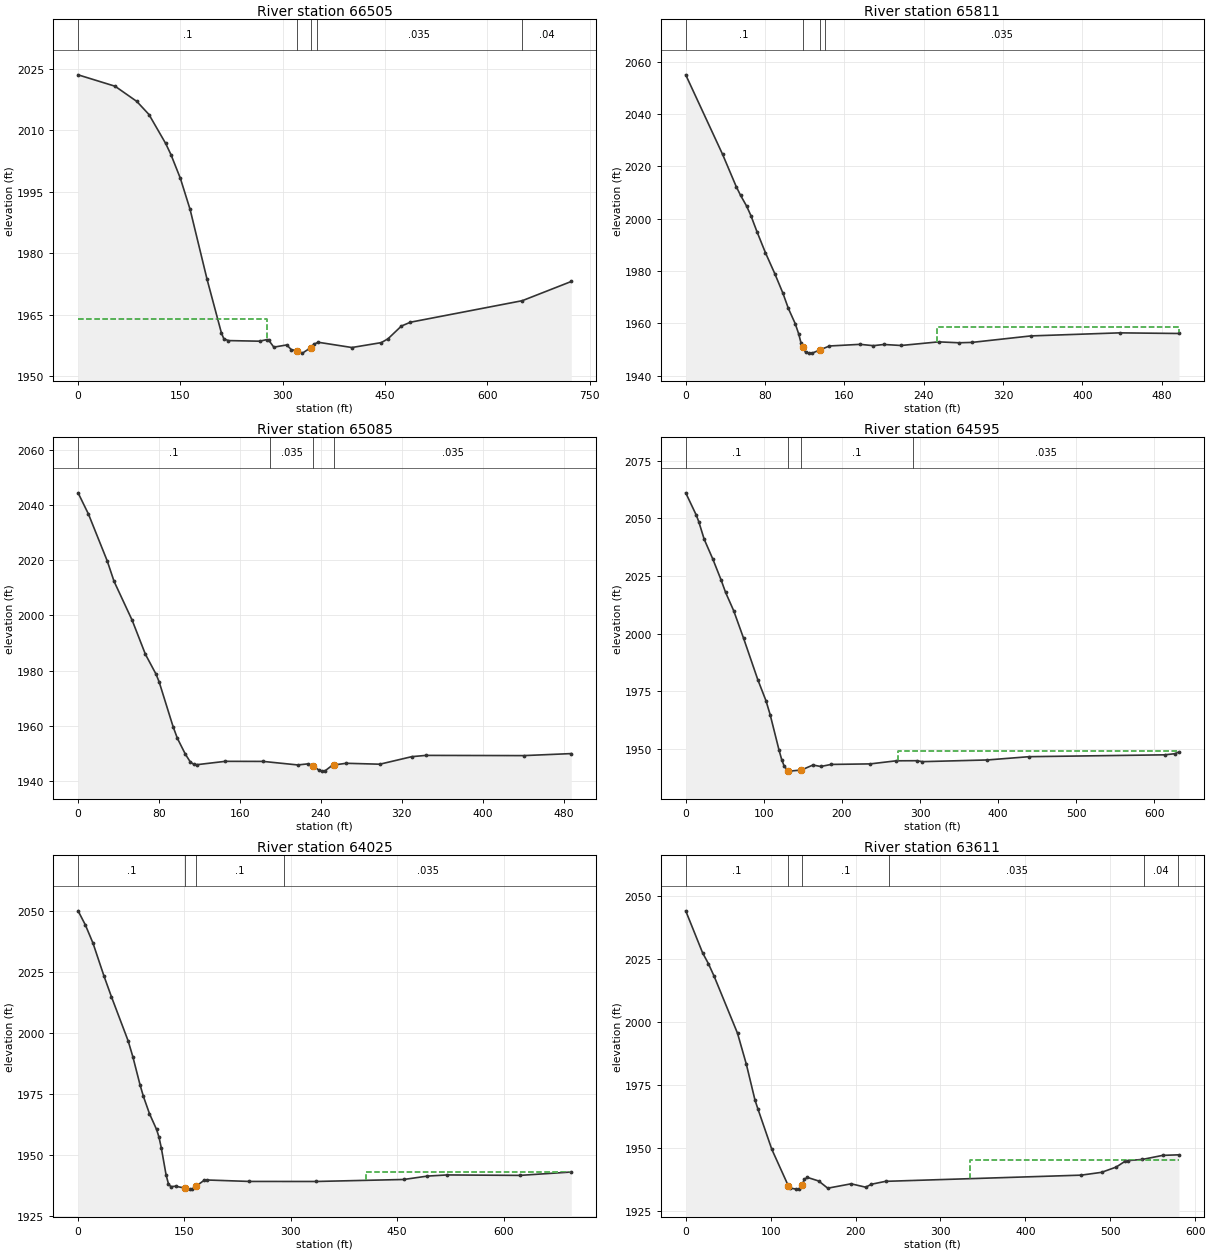
Type RM Length L Ch R = 1 ,66505   ,690.8,693.4,687.3
XS GIS Cut Line= 3
     2070832.952      173292.919     2070753.091      173487.363
     2070801.702       173997.78
#Sta/Elev= 30
       0 2023.58    54.2  2020.8    86.1 2017.09   103.9  2013.9   128.4 2006.83
   136.2 2004.09     150 1998.29   164.2 1990.73   189.1 1973.66   210.2 1960.54
   213.6 1959.21   220.2 1958.75   266.3  1958.6   276.2 1958.98   279.5 1958.82
   286.9 1957.15   305.9 1957.69   312.4 1956.55   320.91956.272   328.9 1955.69
   340.81957.002   345.4 1957.85     352 1958.34   401.3 1957.06   444.3 1958.25
   454.2 1959.18   473.9  1962.3   487.1 1963.23     651 1968.48   722.9 1973.17
#Mann= 5 ,-1 , 0
       0      .1       0   320.9    .045       0   340.8      .1       0
  350.21    .035       0  650.21     .04       0
#XS Ineff= 2 , 0
          276.83  1963.9
Permanent Ineff=
       F       F
Bank Sta=320.9,340.8
XS Rating Curve= 0 ,0
Exp/Cntr=0.3,0.1

Type RM Length L Ch R = 1 ,65811   ,715.3,726.2,722.2
XS GIS Cut Line= 2
     2070100.313       173395.35     2070251.354      173869.308
#Sta/Elev= 30
       0 2054.96    37.2 2024.54    50.9 2012.26    55.3 2008.89    61.4 2004.78
    65.7 2001.17    71.8 1995.04    80.4 1986.94    89.8 1978.97      98 1971.49
   103.5 1965.66   110.4 1959.85   113.9 1955.95   116.2 1952.58   117.81950.857
   120.8 1948.94   124.2 1948.56   127.6 1948.57     1351949.735   144.9 1951.29
   175.8 1951.92   189.3 1951.41   199.8 1951.87   217.2 1951.48     255 1952.87
   275.5 1952.52   288.6 1952.66     348 1955.14   437.5 1956.31   497.4 1956.07
#Mann= 4 ,-1 , 0
       0      .1       0   117.8    .045       0     135      .1       0
     140    .035       0
#XS Ineff= 2 , 0
                          253.21          1958.6
Permanent Ineff=
       F       F
Bank Sta=117.8,135
XS Rating Curve= 0 ,0
Exp/Cntr=0.3,0.1

Type RM Length L Ch R = 1 ,65085   ,480.7,489.9,484.4
XS GIS Cut Line= 2
     2069596.841      173643.613     2069737.466      174110.627
#Sta/Elev= 30
       0  2044.4    10.3 2036.67    28.8 2019.76    35.6 2012.32    53.5 1998.23
    66.6 1985.91    77.2 1978.65    80.2 1975.87    93.9 1959.77    98.2 1955.48
   106.1 1949.74     111 1946.92   114.4 1946.07   117.9 1945.96   145.6 1947.16
     183 1947.13   217.2 1945.85   227.5 1946.25   232.41945.625   237.8 1944.05
   241.2 1943.61   244.6 1943.82     251 1945.63   253.31945.867   265.2 1946.45
   298.4 1946.12     330 1948.85     344 1949.31   440.6 1949.23   487.7 1949.96
#Mann= 4 ,-1 , 0
       0      .1       0     190    .035       0   232.4    .045       0
   253.3    .035       0
Bank Sta=232.4,253.3
XS Rating Curve= 0 ,0
Exp/Cntr=0.3,0.1

Type RM Length L Ch R = 1 ,64595   ,570.2,570,567.5
XS GIS Cut Line= 3
     2069315.591       173645.35     2069282.604      173751.252
     2069376.354      174263.405
#Sta/Elev= 30
       0 2061.05    13.3 2051.53    16.7 2048.55    23.6 2040.94    34.7 2032.31
    45.2 2023.33    51.1  2017.8    61.4 2009.91      74 1998.03    92.3 1979.97
   102.8 1970.81   108.1  1964.8   119.6 1949.26   122.9  1945.3   126.2 1942.35
   130.61940.549   132.9 1940.28   148.21940.766   162.9 1942.93   172.9 1942.29
   186.3 1943.19   236.3 1943.42   269.6 1944.76   296.3  1944.8     303 1944.39
   386.4 1945.13   439.7 1946.55   613.2 1947.35   626.5 1947.84   631.6  1948.6
#Mann= 4 ,-1 , 0
       0      .1       0   130.6    .045       0   148.2      .1       0
  290.92    .035       0
#XS Ineff= 2 , 0
                          271.82         1949.19
Permanent Ineff=
       F       F
Bank Sta=130.6,148.2
XS Rating Curve= 0 ,0
Exp/Cntr=0.3,0.1

Type RM Length L Ch R = 1 ,64025   ,406.8,414.1,414.7
XS GIS Cut Line= 2
     2068697.344      173638.127     2068836.859       174319.47
#Sta/Elev= 30
       0    2050    10.3 2044.21    21.1 2036.71    36.5 2023.32    47.1 2014.76
    70.6 1996.75    77.3 1990.17    87.3 1978.82    92.1 1974.01   100.7 1966.92
   110.7 1960.45   114.1 1957.31   117.4 1952.86   124.1 1941.85   127.5 1938.13
   130.8 1937.05   137.5 1937.22   150.9 1936.43   157.6 1936.03     161 1936.06
   165.91937.129   177.7 1939.63   181.1 1939.78   241.4 1939.18   335.1 1939.16
   459.1 1939.98   492.7 1941.37   520.2 1941.84   623.3 1941.66   695.5 1943.04
#Mann= 4 ,-1 , 0
       0      .1       0   150.9    .045       0   165.9      .1       0
     290    .035       0
#XS Ineff= 2 , 0
                          405.91         1943.13
Permanent Ineff=
       F       F
Bank Sta=150.9,165.9
XS Rating Curve= 0 ,0
Exp/Cntr=0.3,0.1

Type RM Length L Ch R = 1 ,63611   ,374.8,386.3,380.4
XS GIS Cut Line= 2
     2068320.799      173799.863     2068490.938      174355.419
#Sta/Elev= 30
       0    2044    19.8 2027.39    26.7 2023.05    33.5 2018.01      61 1995.41
    71.3 1983.25    81.6 1968.88      85 1965.41   101.4 1949.35   120.8 1934.89
   122.7 1933.96   130.3 1933.54     133 1933.55   136.5 1935.11   139.9 1937.39
   143.3  1938.2   156.6 1936.77   167.3 1933.91   194.8 1935.65     212 1934.31
   218.8 1935.48   235.4 1936.63   465.9 1939.09   489.9 1940.21     507 1942.29
   517.3 1944.54   520.8 1944.87   537.9 1945.32   561.9 1946.94     581 1947.16
#Mann= 6 ,-1 , 0
       0      .1       0   120.8    .045       0   136.5      .1       0
     240    .035       0     540     .04       0     580     .06       0
#XS Ineff= 2 , 0
                          334.37         1945.15
Permanent Ineff=
       F       F
Bank Sta=120.8,136.5
XS Rating Curve= 0 ,0
Exp/Cntr=0.3,0.1

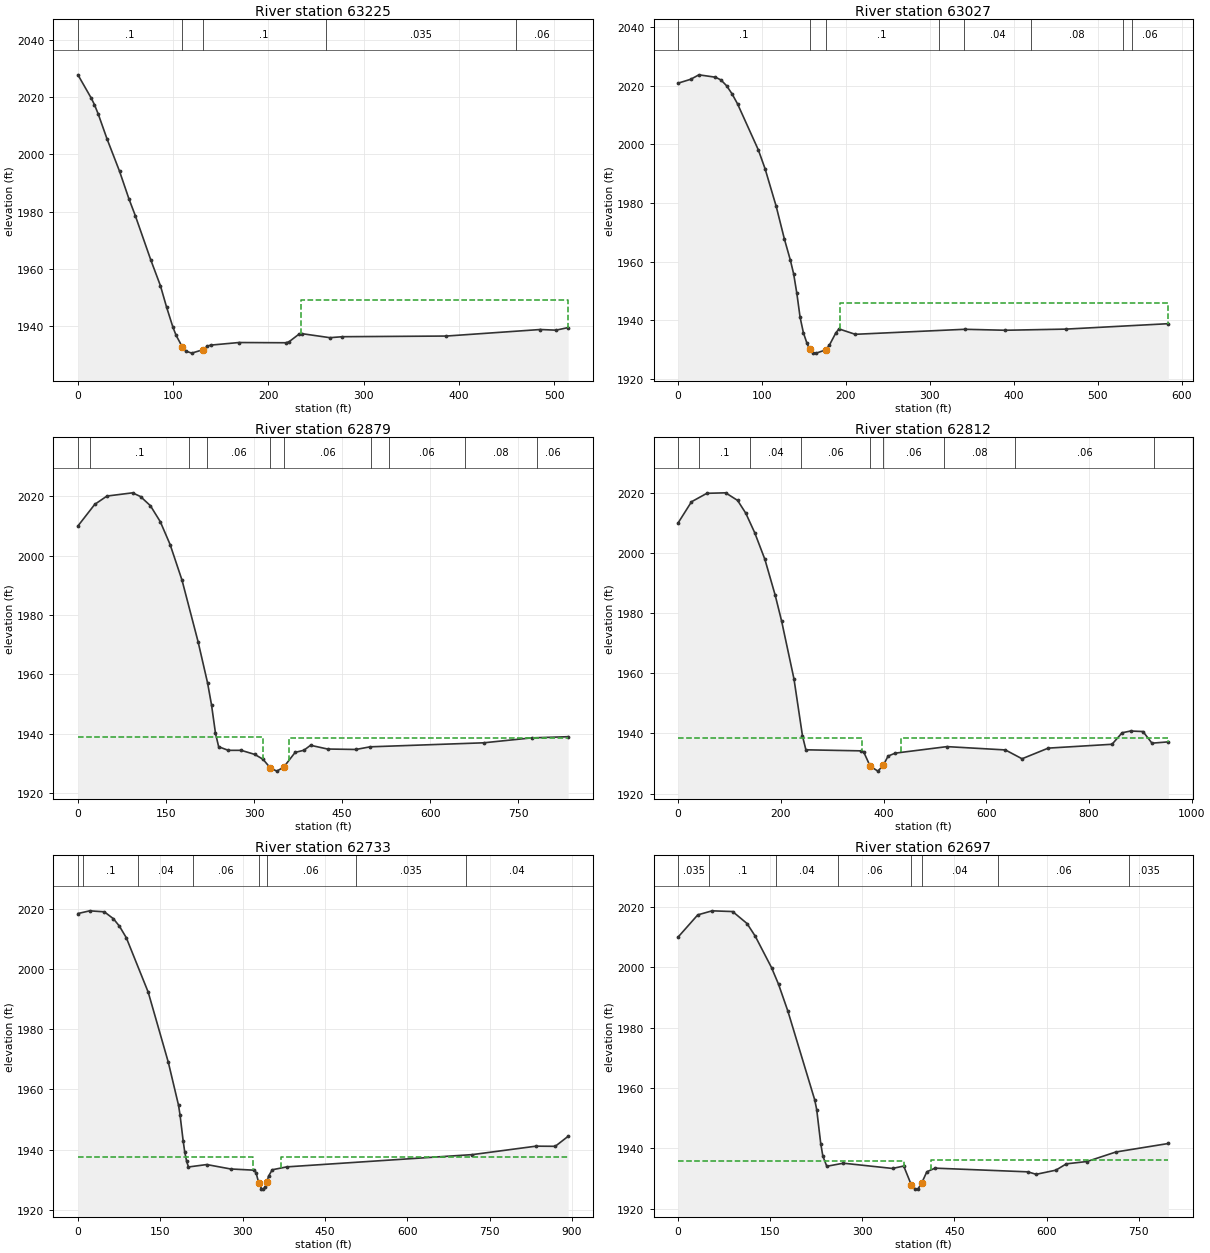
Type RM Length L Ch R = 1 ,63225   ,205.3,197.9,192
XS GIS Cut Line= 2
     2067992.674      173860.627     2068044.757       174372.78
#Sta/Elev= 30
       0 2027.78      14 2019.64    17.3  2017.4    21.3 2014.12    30.5 2005.47
    43.7 1994.13    53.6 1984.47    60.2 1978.69    76.7 1963.01    86.6 1954.23
    93.1 1946.72    99.8 1939.67   103.1 1936.88   109.61932.836     113 1931.42
   119.5 1930.67   131.21931.856     136  1933.1   139.3 1933.46     169 1934.37
   218.5 1934.29   221.8 1934.66   231.7 1937.18     235 1937.47   264.6 1936.06
   277.8  1936.4   386.9 1936.63   485.6 1938.91   502.1 1938.68   514.8 1939.59
#Mann= 5 ,-1 , 0
       0      .1       0   109.6    .045       0   131.2      .1       0
     260    .035       0     460     .06       0
#XS Ineff= 2 , 0
                          234.03         1949.29
Permanent Ineff=
       F       F
Bank Sta=109.6,131.2
XS Rating Curve= 0 ,0
Exp/Cntr=0.3,0.1

Type RM Length L Ch R = 1 ,63027   ,152.9,147.7,143.2
XS GIS Cut Line= 3
     2067780.868      173843.266     2067789.549      173973.475
     2068029.132      174358.891
#Sta/Elev= 30
       0 2020.91    14.9 2022.22    24.8 2023.75    44.5 2022.94    51.1 2021.99
    57.7 2020.05    64.3 2017.25    70.8 2013.86    95.6 1998.16   103.7 1991.67
   116.9  1978.9   126.7 1967.71   133.8 1960.53   137.7 1955.86   141.5 1949.23
   145.4 1941.04   149.3 1935.82   153.4 1932.33   156.61930.243   160.8 1928.95
   164.7 1928.84   175.81929.945   180.2 1931.51   187.9  1935.7   191.7  1937.1
   211.1 1935.26   341.6 1936.97   390.1 1936.64   462.2 1937.03   584.3 1938.88
#Mann= 8 ,-1 , 0
       0      .1       0   156.6    .045       0   175.8      .1       0
   310.5     .06       0   340.5     .04       0   420.5     .08       0
   530.5    .035       0   540.5     .06       0
#XS Ineff= 2 , 0
                          193.33            1946
Permanent Ineff=
       F       F
Bank Sta=156.6,175.8
XS Rating Curve= 0 ,0
Exp/Cntr=0.5,0.3

Type RM Length L Ch R = 1 ,62879   ,66,66.9,65.6
XS GIS Cut Line= 4
     2067643.454      173714.785     2067591.369      173948.721
     2067982.257       174310.28     2068022.188      174358.891
#Sta/Elev= 30
       0    2010    28.6 2017.27    49.4 2020.08    93.1 2021.17   106.6 2019.91
   123.4 2016.84   140.2 2011.48     157 2003.75   177.3 1991.73   204.6 1971.04
   220.8 1957.13   227.6 1949.64   234.3 1940.15   239.7 1935.61   256.1  1934.4
   278.1  1934.4   301.4 1933.01   315.3 1931.37   327.91928.431   338.8 1927.39
   350.51928.739     370 1933.71   384.9 1934.42   396.2  1936.1   425.2 1934.84
   473.5 1934.69   497.7 1935.58   690.9 1936.93     773  1938.6     835 1938.99
#Mann= 10 ,-1 , 0
       0    .035       0      20      .1       0     190     .04       0
     220     .06       0   327.9    .045       0   350.5     .06       0
  499.66     .08       0  529.66     .06       0  659.66     .08       0
  782.13     .06       0
#XS Ineff= 2 , 0
          315.34 1939.04  358.68          1938.6
Permanent Ineff=
       F       F
Bank Sta=327.9,350.5
XS Rating Curve= 0 ,0
Exp/Cntr=0.5,0.3

Type RM Length L Ch R = 1 ,62812   ,66.4,78.9,95.7
XS GIS Cut Line= 3
     2067617.575      173694.7312067565.47874208174007.313204917
2068016.51333935174458.105915306
#Sta/Elev= 30
       0    2010      26 2017.03      56 2019.85    92.5 2020.01   115.8 2017.49
   131.7 2013.25   149.1 2006.77     169 1997.86     189 1985.98   201.4 1977.46
   225.6 1958.13   242.2 1939.14   248.8 1934.55   356.5  1934.2   361.2 1933.89
     374  1929.1     389 1927.46   399.5 1929.39   408.8 1932.45   422.7 1933.44
   523.6 1935.61   637.2 1934.51   669.7 1931.57   720.7 1935.11   844.9 1936.39
   864.5 1940.21     881  1940.8   905.2 1940.63   922.7 1936.76   954.6 1937.19
#Mann= 9 ,-1 , 0
       0    .035       0      40      .1       0     140     .04       0
     240     .06       0     374    .045       0   399.5     .06       0
  516.89     .08       0  656.89     .06       0  926.89     .08       0
#XS Ineff= 2 , 0
           358.8 1938.54  433.79         1938.41
Permanent Ineff=
       F       F
Bank Sta=374,399.5
XS Rating Curve= 0 ,0
Exp/Cntr=0.5,0.3

Type RM Length L Ch R = 1 ,62733   ,26.7,36.4,45.5
XS GIS Cut Line= 3
     2067589.536      173722.2342067536.23073497174023.597787978
2067490.48957596174608.762399461
#Sta/Elev= 30
       0 2018.35    21.4 2019.25    48.1 2018.92    64.7 2016.62    75.6 2014.16
    88.1 2010.34   128.1 1992.23   164.7 1968.99   183.2 1954.81     186 1951.56
   191.7 1942.92   194.5 1939.36     198 1936.15   201.4  1934.3   234.7  1935.1
     278 1933.64   321.1 1933.23   324.4 1932.42   329.2 1929.14   334.3 1927.12
   337.6 1926.95   340.9 1927.58   344.1 1929.33   347.4  1931.3     354 1933.37
   380.3 1934.33   718.6  1938.4   834.5  1941.2   869.5 1941.15     893 1944.48
#Mann= 8 ,-1 , 0
       0    .035       0      10      .1       0     110     .04       0
     210     .06       0   329.2    .045       0   344.1     .06       0
  506.04    .035       0  706.04     .04       0
#XS Ineff= 2 , 0
          318.62 1937.59  369.83         1937.53
Permanent Ineff=
       F       F
Bank Sta=329.2,344.1
XS Rating Curve= 0 ,0
Exp/Cntr=0.5,0.3

Type RM Length L Ch R = 1 ,62697   ,56.5,56.5,56.5
XS GIS Cut Line= 4
       2067590.6      173675.774      2067525.66       174020.35
     2067329.479      174211.322     2067293.021      174381.461
#Sta/Elev= 30
       0    2010      32 2017.35    55.4 2018.69    88.8 2018.45   112.2 2014.49
   125.5 2010.33   152.2 1999.85   163.5 1994.38   178.9 1985.37   222.5 1956.03
   225.7 1952.84   232.3 1941.53   235.7 1937.44   242.1 1934.05   269.1 1935.07
   349.2 1933.33   367.4 1934.13     3801927.784   386.3 1926.48   390.9 1926.64
   396.4 1928.39   405.1 1932.23   418.4 1933.43   569.5 1932.21   583.2 1931.39
   615.3 1932.77   632.3 1934.86   665.9 1935.63   712.9 1938.78   798.4  1941.6
#Mann= 8 ,-1 , 0
       0    .035       0      50      .1       0     160     .04       0
     260     .06       0     380    .045       0   396.4     .04       0
  520.64     .06       0  734.43    .035       0
#XS Ineff= 2 , 0
          368.21 1935.91  411.59         1935.98
Permanent Ineff=
       F       F
Bank Sta=380,396.4
XS Rating Curve= 0 ,0
Exp/Cntr=0.5,0.3

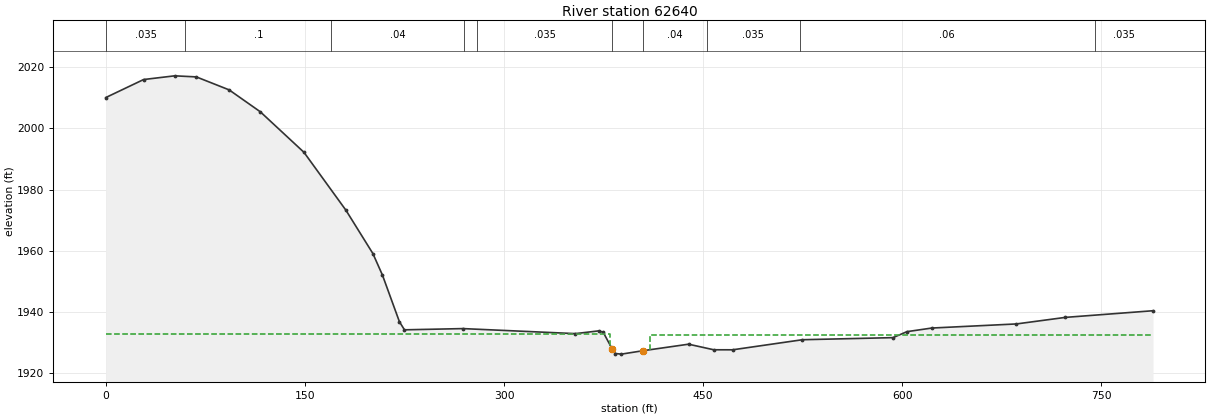
Type RM Length L Ch R = 1 ,62640   ,344.3,344.3,344.3
XS GIS Cut Line= 4
     2067573.236      173666.8922067488.38324858173988.587168455
     2067293.021      174192.225     2067256.563      174362.363
#Sta/Elev= 30
       0    2010    28.5 2015.88    51.9 2017.09    68.2 2016.74    92.9 2012.51
   116.4 2005.36   149.3 1992.13   180.9 1973.24   201.2 1959.11   208.4 1952.09
   221.2 1936.86     225 1934.22   269.1 1934.62   353.7 1932.98   371.4 1933.88
   374.7 1933.43   381.41928.029   383.8 1926.49   388.4 1926.29   404.41927.383
     439 1929.53     458 1927.71   472.2  1927.7   524.8 1930.99     593 1931.67
   603.5 1933.62   622.2  1934.8     686 1936.14   722.9 1938.28   788.9 1940.45
#Mann= 10 ,-1 , 0
       0    .035       0      60      .1       0     170     .04       0
     270     .06       0     280    .035       0   381.4    .045       0
   404.4     .04       0   452.7    .035       0   522.7     .06       0
  744.89    .035       0
#XS Ineff= 2 , 0
          380.17 1932.76  410.06         1932.63
Permanent Ineff=
       F       F
Bank Sta=381.4,404.4
XS Rating Curve= 0 ,0
Exp/Cntr=0.5,0.3