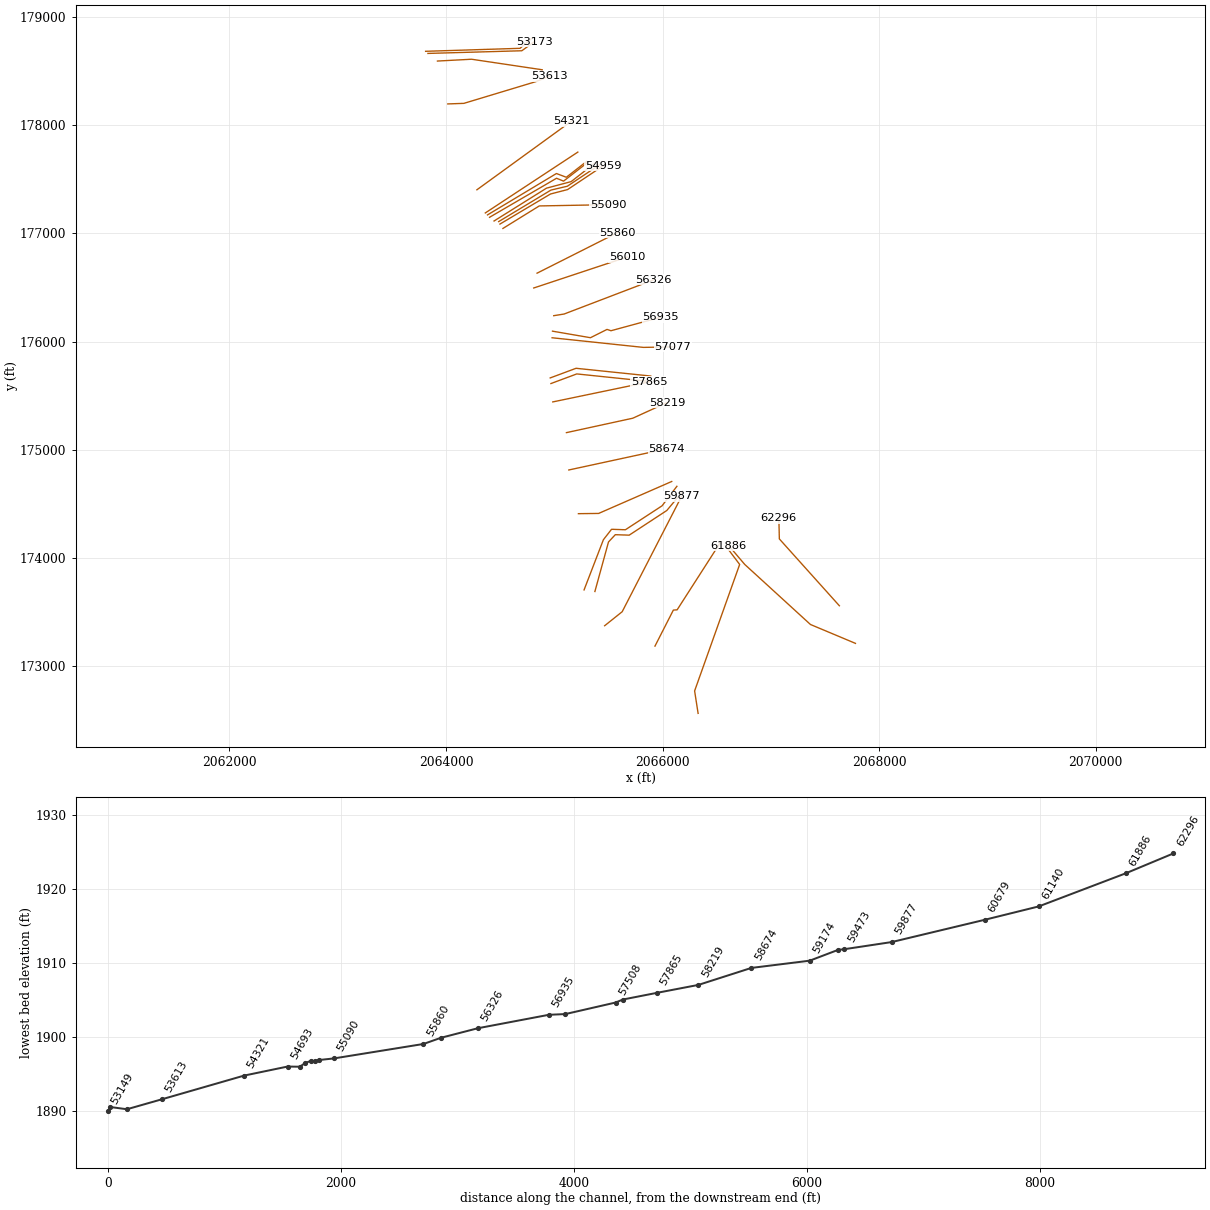
HEC-RAS study HNSCK.prj: HNSCK

--- HNSCK.g01 (geometry) --- (continued)

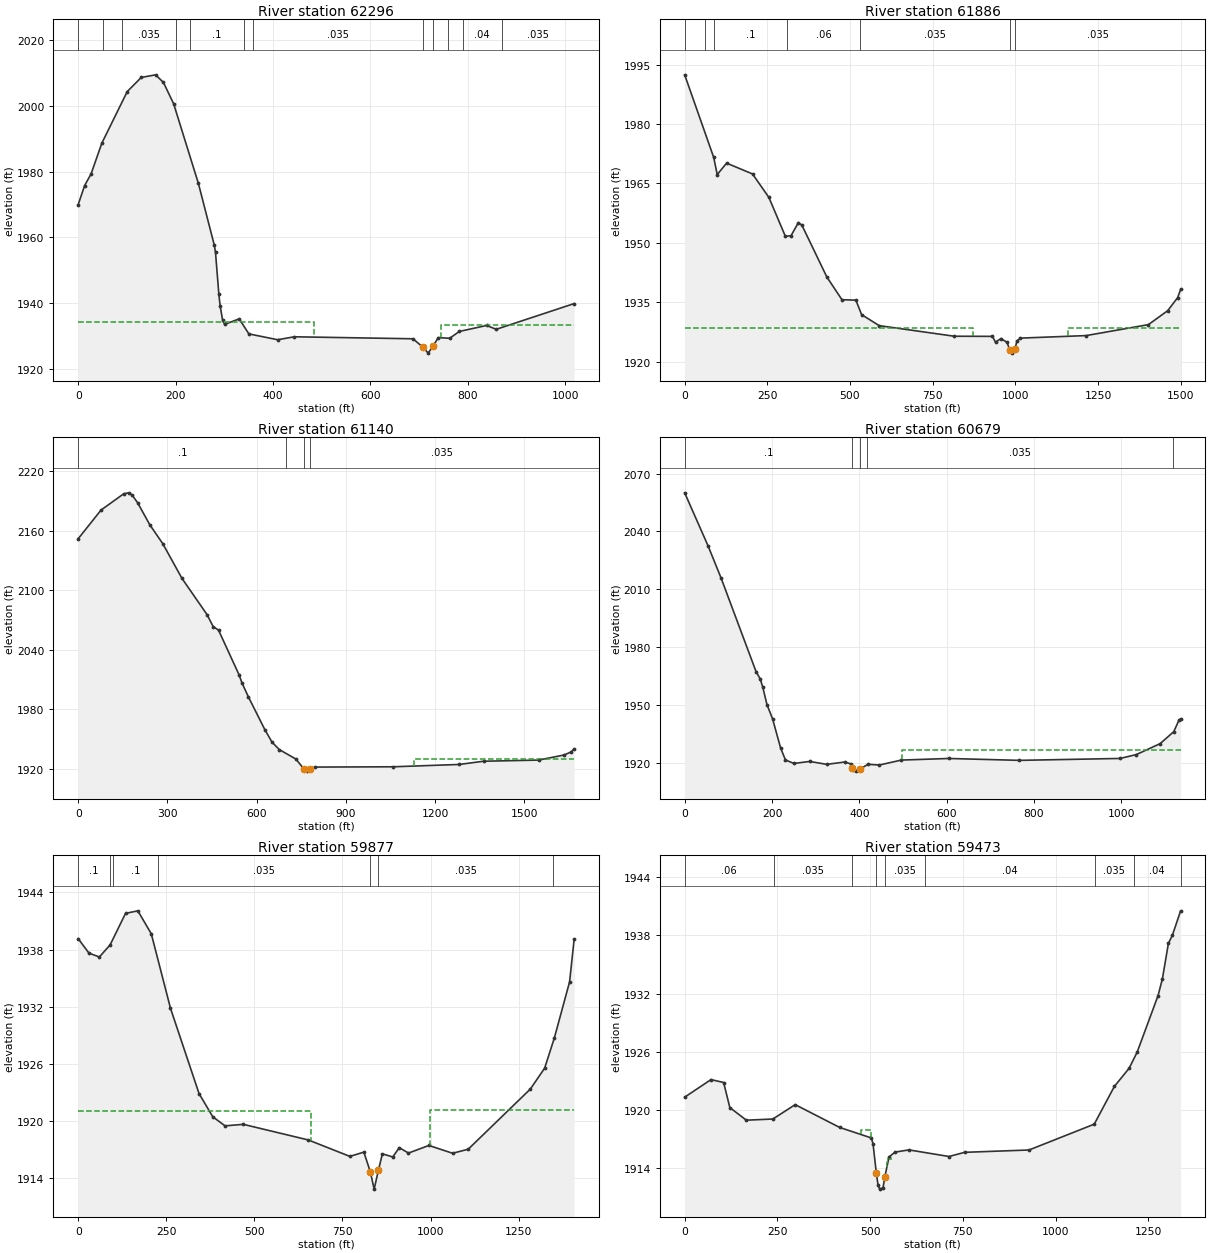
Type RM Length L Ch R = 1 ,62296   ,404.5,410,409.3
XS GIS Cut Line= 3
     2067632.499      173559.615     2067078.235      174177.207
     2067073.895      174366.009
#Sta/Elev= 30
       0    1970    13.2 1975.77    26.4  1979.3    48.5 1988.65   100.7 2004.34
   129.5 2008.63     159 2009.43   175.1  2007.1     196 2000.63   246.9  1976.4
   279.6 1957.61     282 1955.43   288.9 1942.73   291.6 1939.14   296.5 1934.96
   300.6 1933.58   330.8 1935.25   350.5 1930.68   409.7  1928.9   443.9  1929.8
   687.7 1929.19   708.51926.579   718.9 1924.83   729.31927.097   739.7 1929.54
   763.2 1929.35   782.8 1931.42   838.9 1933.24   858.6 1932.07  1018.7 1939.89
#Mann= 12 ,-1 , 0
       0    .035       0      50      .1       0      90    .035       0
     200     .06       0     230      .1       0     340     .06       0
     360    .035       0   708.5    .045       0   729.3    .035       0
     760     .06       0     790     .04       0  869.84    .035       0
#XS Ineff= 2 , 0
          484.98 1934.37  744.29         1933.41
Permanent Ineff=
       F       F
Bank Sta=708.5,729.3
XS Rating Curve= 0 ,0
Exp/Cntr=0.3,0.1

Type RM Length L Ch R = 1 ,61886   ,756.4,746.1,723.4
XS GIS Cut Line= 4
2067781.13071746173212.026875568     2067365.599      173386.442
     2066758.682      173941.371     2066611.655      174114.273
#Sta/Elev= 30
       0 1992.41    87.8 1971.55    98.4 1967.22   126.8 1970.11   205.2 1967.38
   254.7 1961.45   304.7  1951.6   321.7  1951.8     344  1955.1   354.6 1954.43
   430.1 1941.34   475.7 1935.62   517.7 1935.51   535.2 1931.85   588.5 1929.07
   815.2  1926.4   930.9 1926.36   940.2 1924.88   956.4 1925.81     975 1924.85
   982.91923.017   988.9 1922.13   998.7 1923.11  1005.2 1925.23  1015.3 1925.92
  1214.2 1926.56  1402.6 1929.33  1460.8 1932.84    1491 1936.14    1500 1938.22
#Mann= 7 ,-1 , 0
       0      .1       0      60     .06       0      90      .1       0
     310     .06       0  530.65    .035       0   982.9    .045       0
   998.7    .035       0
#XS Ineff= 2 , 0
           873.3 1928.35 1160.76         1928.37
Permanent Ineff=
       F       F
Bank Sta=982.9,998.7
XS Rating Curve= 0 ,0
Exp/Cntr=0.3,0.1

Type RM Length L Ch R = 1 ,61140   ,474.5,460.5,440.7
XS GIS Cut Line= 4
      2066328.04      172565.153     2066295.779       172772.61
     2066711.807      173941.371     2066581.108      174114.402
#Sta/Elev= 30
       0 2152.12    76.7 2180.99   153.1 2197.45   169.7 2198.39   180.7 2196.38
   199.6 2188.44   240.6 2166.21   284.3 2147.11   348.8  2112.1   433.3 2075.48
   453.8 2063.42   471.8 2059.88   540.4 2015.06   550.8  2006.5   571.9 1992.72
   627.4 1959.51   651.8  1946.8   676.2 1939.34   731.9 1929.84   759.9 1919.43
   768.3 1917.65   779.51919.529   794.6 1921.73  1059.3 1922.03  1280.8 1924.38
    1363 1927.63  1547.7 1928.79  1633.8 1933.94  1657.6  1937.1  1667.4    1940
#Mann= 4 ,-1 , 0
       0      .1       0  699.95    .035       0   759.9    .045       0
   779.5    .035       0
#XS Ineff= 2 , 0
                         1129.45         1929.42
Permanent Ineff=
       F       F
Bank Sta=759.9,779.5
XS Rating Curve= 0 ,0
Exp/Cntr=0.3,0.1

Type RM Length L Ch R = 1 ,60679   ,785.8,802.2,815.4
XS GIS Cut Line= 4
     2065929.757      173186.808     2066099.503      173519.655
     2066134.225      173521.825      2066527.02      174133.804
#Sta/Elev= 30
       0    2060    53.9 2032.35    83.6 2015.73   163.4 1967.41   172.9 1963.64
   178.7 1959.47   188.4 1950.31   201.2 1942.98   219.6  1927.9   230.7 1921.65
   250.1 1919.82   286.2 1920.87     325 1919.36   366.9 1920.57   379.9 1919.64
   383.61917.538   386.4 1916.24     393 1915.85   402.11917.007   419.9 1919.39
   445.5    1919   496.2 1921.58   604.7  1922.4   766.6 1921.43   996.9 1922.42
  1034.2 1924.42  1088.8  1930.1    1120 1936.32  1131.7 1942.22  1135.6 1942.87
#Mann= 5 ,-1 , 0
       0      .1       0   383.6    .045       0   402.1      .1       0
  418.42    .035       0 1118.42     .06       0
#XS Ineff= 2 , 0
                           496.6         1926.54
Permanent Ineff=
       F       F
Bank Sta=383.6,402.1
XS Rating Curve= 0 ,0
Exp/Cntr=0.3,0.1

Type RM Length L Ch R = 1 ,59877   ,408.2,404.2,399.5
XS GIS Cut Line= 3
2065465.03636848173375.0688573162065627.02972456173504.615879654
2066176.27977668174571.861707187
#Sta/Elev= 30
       0 1939.14    30.6 1937.62      60 1937.22    90.6 1938.49   134.3  1941.8
   169.3 1942.07   207.4 1939.66   261.9 1931.83     343 1922.86     382 1920.42
   416.9 1919.47   468.5 1919.63     653 1917.99   771.1 1916.26   810.8 1916.71
   829.41914.605     840 1912.82     852 1914.78   863.3 1916.53   892.9  1916.2
   911.3 1917.18   937.4 1916.61   995.4 1917.41  1062.6 1916.59  1106.9 1917.01
  1283.4 1923.34  1323.9 1925.53  1351.6 1928.72  1394.7  1934.6  1407.7 1939.08
#Mann= 7 ,-1 , 0
       0      .1       0      90    .035       0     100      .1       0
  227.42    .035       0   829.4    .045       0     852    .035       0
 1347.42     .04       0
#XS Ineff= 2 , 0
          659.84 1920.99  999.79         1921.09
Permanent Ineff=
       F       F
Bank Sta=829.4,852
XS Rating Curve= 0 ,0
Exp/Cntr=0.5,0.3

Type RM Length L Ch R = 1 ,59473   ,53.7,55.5,57.9
XS GIS Cut Line= 6
 2065374.9342984173691.294953525     2065500.544      174148.995
     2065563.478       174216.27     2065691.516      174211.929
     2066038.799      174439.702     2066184.138      174613.405
#Sta/Elev= 30
       0 1921.33    70.9 1923.14     105 1922.84   121.7 1920.26   166.2 1918.96
   237.7 1919.08   297.9 1920.56   417.9 1918.21   503.2 1917.13   507.7 1916.52
   516.7 1913.47   521.2 1912.27   525.6 1911.86   534.6    1912   539.2 1913.07
   550.8 1915.17   566.7 1915.67   604.5  1915.9   712.4 1915.22   754.7 1915.65
   928.1 1915.89  1103.9 1918.55  1158.2 1922.44    1198 1924.31  1219.6 1925.97
  1275.9 1931.79  1287.5  1933.5  1303.8 1937.17  1314.4 1937.99  1336.7 1940.52
#Mann= 9 ,-1 , 0
       0     .06       0     240    .035       0     450     .04       0
   516.7    .045       0   539.2    .035       0  646.75     .04       0
 1104.86    .035       0 1210.17     .04       0 1336.66     .06       0
#XS Ineff= 3 ,-1
     475     503    1918     503     510    1915     545     560    1915
Permanent Ineff=
       F       F       F
Bank Sta=516.7,539.2
XS Rating Curve= 0 ,0
Exp/Cntr=0.5,0.3

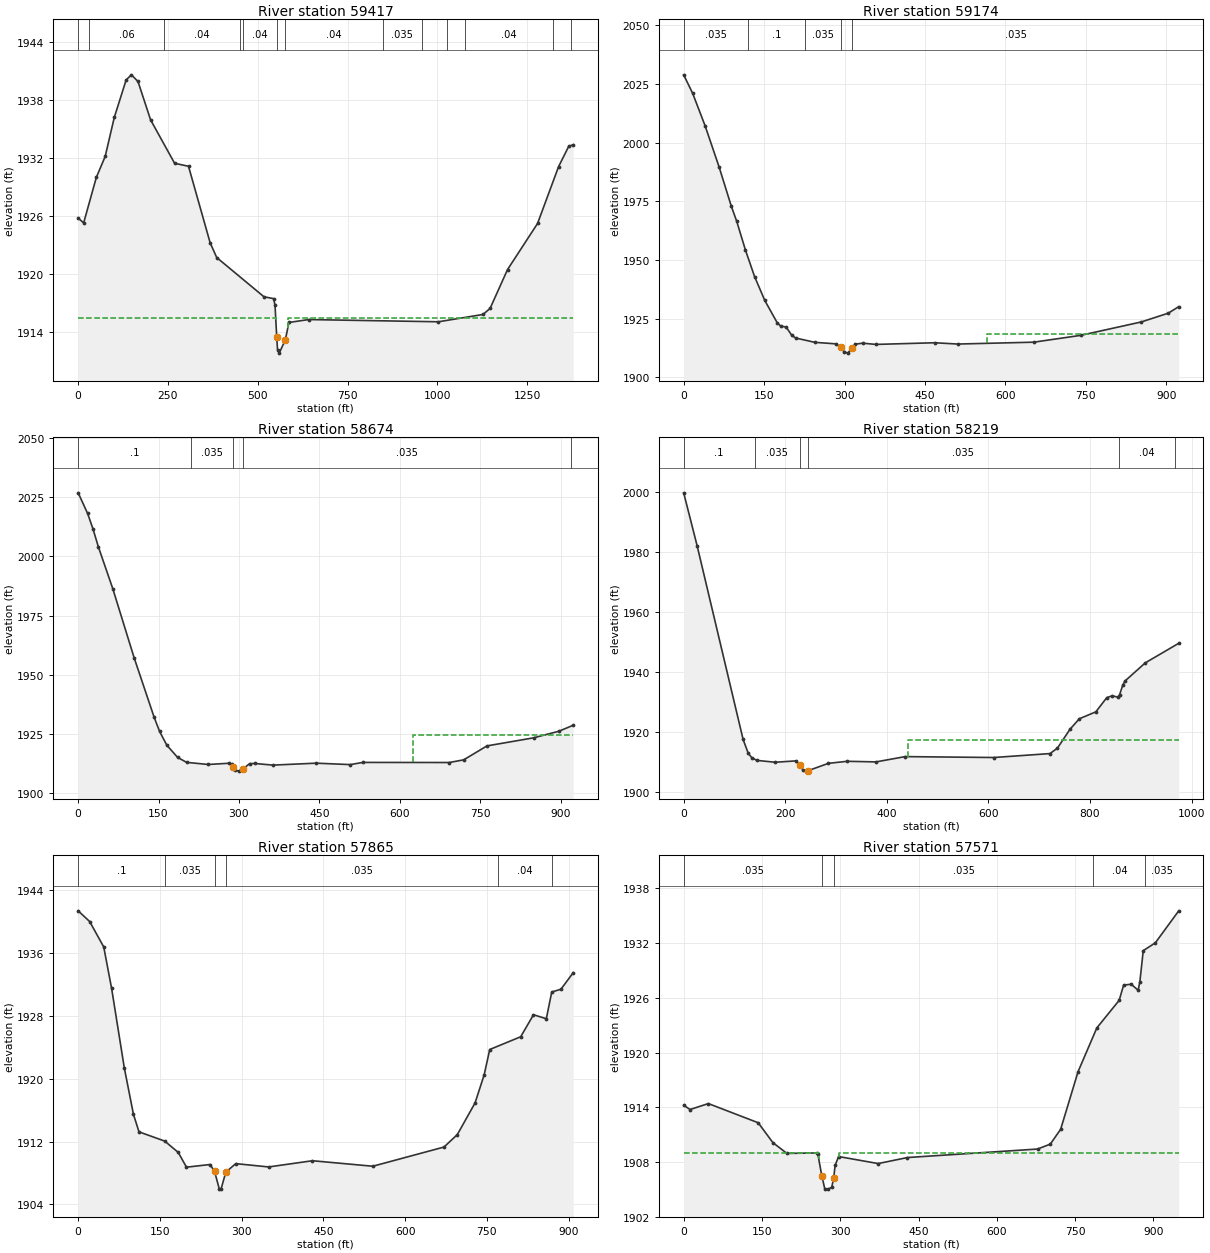
Type RM Length L Ch R = 1 ,59417   ,250,243.2,232.1
XS GIS Cut Line= 6
2065274.89103786173706.0819124352065453.51379508174169.903159017
     2065528.756      174266.183     2065656.794      174261.843
     2065995.336      174483.197     2066132.055      174663.318
#Sta/Elev= 30
       0 1925.76    15.3 1925.26    50.5 1929.97    75.2 1932.15   100.5 1936.19
   133.5 1940.08   148.2 1940.61   166.5 1939.92   201.6 1935.94   268.4 1931.44
   307.1 1931.13   367.3  1923.2   385.6 1921.67   517.2  1917.6   543.9 1917.41
   547.9 1916.73   552.6 1913.46   554.9 1912.12   559.6 1911.76   576.9 1913.17
   586.5 1914.94   641.7 1915.24  1002.8 1915.01  1126.9 1915.77  1146.5  1916.4
    1195 1920.42  1278.6  1925.2  1337.1 1931.09  1365.2 1933.19  1377.9 1933.37
#Mann= 13 ,-1 , 0
       0     .04       0      30     .06       0     240     .04       0
     450      .1       0     460     .04       0   552.6    .045       0
   576.9     .04       0  847.33    .035       0  957.33     .04       0
 1027.33    .035       0 1077.33     .04       0 1321.82    .035       0
 1371.82     .06       0
#XS Ineff= 2 , 0
          550.29 1915.45  583.61         1915.37
Permanent Ineff=
       F       F
Bank Sta=552.6,576.9
XS Rating Curve= 0 ,0
Exp/Cntr=0.5,0.3

Type RM Length L Ch R = 1 ,59174   ,497.1,500.5,489.5
XS GIS Cut Line= 3
     2065222.766      174410.497     2065409.398      174412.667
     2066084.312      174707.806
#Sta/Elev= 30
       0 2028.84    16.8 2020.94    39.8 2007.24      66 1989.64      89 1972.77
    98.8 1966.54   115.2 1954.21   132.2 1942.93   151.3 1932.73   174.3  1923.3
   180.9 1921.82   191.1 1921.43   201.8 1917.82     209 1916.73   244.8 1914.89
   284.2 1914.25   293.11912.736   299.3 1910.91   305.7  1910.3   314.31912.429
     320 1914.11   333.9 1914.54   358.5 1914.01   468.2 1914.72   511.1 1914.17
   652.8 1914.96   740.3 1917.86   853.5 1923.58   903.7 1927.31   923.3 1930.09
#Mann= 5 ,-1 , 0
       0    .035       0     120      .1       0  226.64    .035       0
   293.1    .045       0   314.3    .035       0
#XS Ineff= 2 , 0
                          565.27         1918.36
Permanent Ineff=
       F       F
Bank Sta=293.1,314.3
XS Rating Curve= 0 ,0
Exp/Cntr=0.3,0.1

Type RM Length L Ch R = 1 ,58674   ,447.2,454.4,447.4
XS GIS Cut Line= 2
     2065133.791      174814.143     2066036.569      175009.455
#Sta/Elev= 30
       0 2026.88    17.6 2018.17    27.7  2011.6    37.7 2004.05    64.6 1986.38
   104.5 1957.14   141.8 1932.05   151.9  1926.1   165.4 1920.28   185.4 1915.15
   202.2 1913.03   242.5 1912.13   281.1 1912.64   286.1 1912.17   288.21911.149
   292.9 1909.75   299.6 1909.32   307.91910.357   319.9 1912.47   329.8 1912.55
   363.3 1911.86   443.9 1912.68   507.7 1912.08   531.2    1913   692.3 1912.96
   719.2 1914.08   762.8 1919.98   849.6 1923.38   897.1 1926.18   923.7 1928.71
#Mann= 5 ,-1 , 0
       0      .1       0     210    .035       0   288.2    .045       0
   307.9    .035       0     920     .04       0
#XS Ineff= 2 , 0
                          624.24         1924.47
Permanent Ineff=
       F       F
Bank Sta=288.2,307.9
XS Rating Curve= 0 ,0
Exp/Cntr=0.3,0.1

Type RM Length L Ch R = 1 ,58219   ,351.8,354.3,351.8
XS GIS Cut Line= 3
     2065112.089      175159.195  2065724.989726175292.546396984
     2066040.909      175436.973
#Sta/Elev= 30
       0 1999.61    26.4 1982.06     117 1917.56   127.1 1912.96   133.8 1911.54
   143.9  1910.6   180.1 1909.97   221.1 1910.43   228.61908.895   234.6 1907.47
   241.3 1907.02   243.91907.107   284.9 1909.61   321.9 1910.29   378.6 1910.09
     436 1911.85   610.6 1911.55   721.2 1912.86   735.8 1914.68   760.5 1920.94
   778.9 1924.44   811.4 1926.74     833 1931.48   843.8 1932.09   854.7 1931.64
   858.3 1932.49   864.5 1935.68   869.1 1937.05   908.8 1943.05   974.6 1949.55
#Mann= 6 ,-1 , 0
       0      .1       0     140    .035       0   228.6    .045       0
   243.9    .035       0  857.24     .04       0  967.24    .035       0
#XS Ineff= 2 , 0
                          442.42         1917.48
Permanent Ineff=
       F       F
Bank Sta=228.6,243.9
XS Rating Curve= 0 ,0
Exp/Cntr=0.3,0.1

Type RM Length L Ch R = 1 ,57865   ,290.6,294,254.2
XS GIS Cut Line= 2
2064985.99943836175443.0941123272065875.24882756175628.115642383
#Sta/Elev= 30
       0 1941.33    21.1 1939.97    46.9 1936.74    61.3 1931.49    84.7 1921.34
   101.5 1915.44   111.6 1913.23   158.7 1912.06   183.6 1910.62   198.7 1908.74
   241.9 1909.08   250.2 1908.22     259 1905.95   262.4 1906.02   270.91908.116
   289.2 1909.19   349.5 1908.77   429.9 1909.56   540.5 1908.86   671.2  1911.3
   695.6 1912.88   728.2 1916.91   744.9 1920.48   755.1  1923.7   811.9 1925.32
   835.4 1928.12   858.9 1927.61   868.9 1931.01   885.7 1931.36   908.3 1933.47
#Mann= 6 ,-1 , 0
       0      .1       0     160    .035       0   250.2    .045       0
   270.9    .035       0     770     .04       0     870    .035       0
Bank Sta=250.2,270.9
XS Rating Curve= 0 ,0
Exp/Cntr=0.5,0.3

Type RM Length L Ch R = 1 ,57571   ,61.4,63,67.1
XS GIS Cut Line= 3
      2064968.86      175612.754     2065207.575       175701.73
      2065897.68      175630.115
#Sta/Elev= 30
       0 1914.23    12.3 1913.76    47.3 1914.41   142.8 1912.31     171 1910.13
   197.9 1908.95   254.8    1909   257.2 1908.84   264.61906.519   270.4 1905.07
     277 1905.04   283.7 1905.24   287.51906.283   290.2 1907.63   296.8 1908.61
   372.7 1907.84   428.8  1908.5   678.1 1909.43   702.5 1909.97   722.3 1911.59
   755.8 1917.92   791.7  1922.7   834.5 1925.72     843 1927.39   857.6 1927.48
   870.8 1926.82   874.1 1927.74   880.6 1931.16   903.7 1932.01   948.6 1935.52
#Mann= 5 ,-1 , 0
       0    .035       0   264.6    .045       0   287.5    .035       0
  784.76     .04       0  884.76    .035       0
#XS Ineff= 2 , 0
          258.65 1909.04  298.18         1909.04
Permanent Ineff=
       F       F
Bank Sta=264.6,287.5
XS Rating Curve= 0 ,0
Exp/Cntr=0.5,0.3

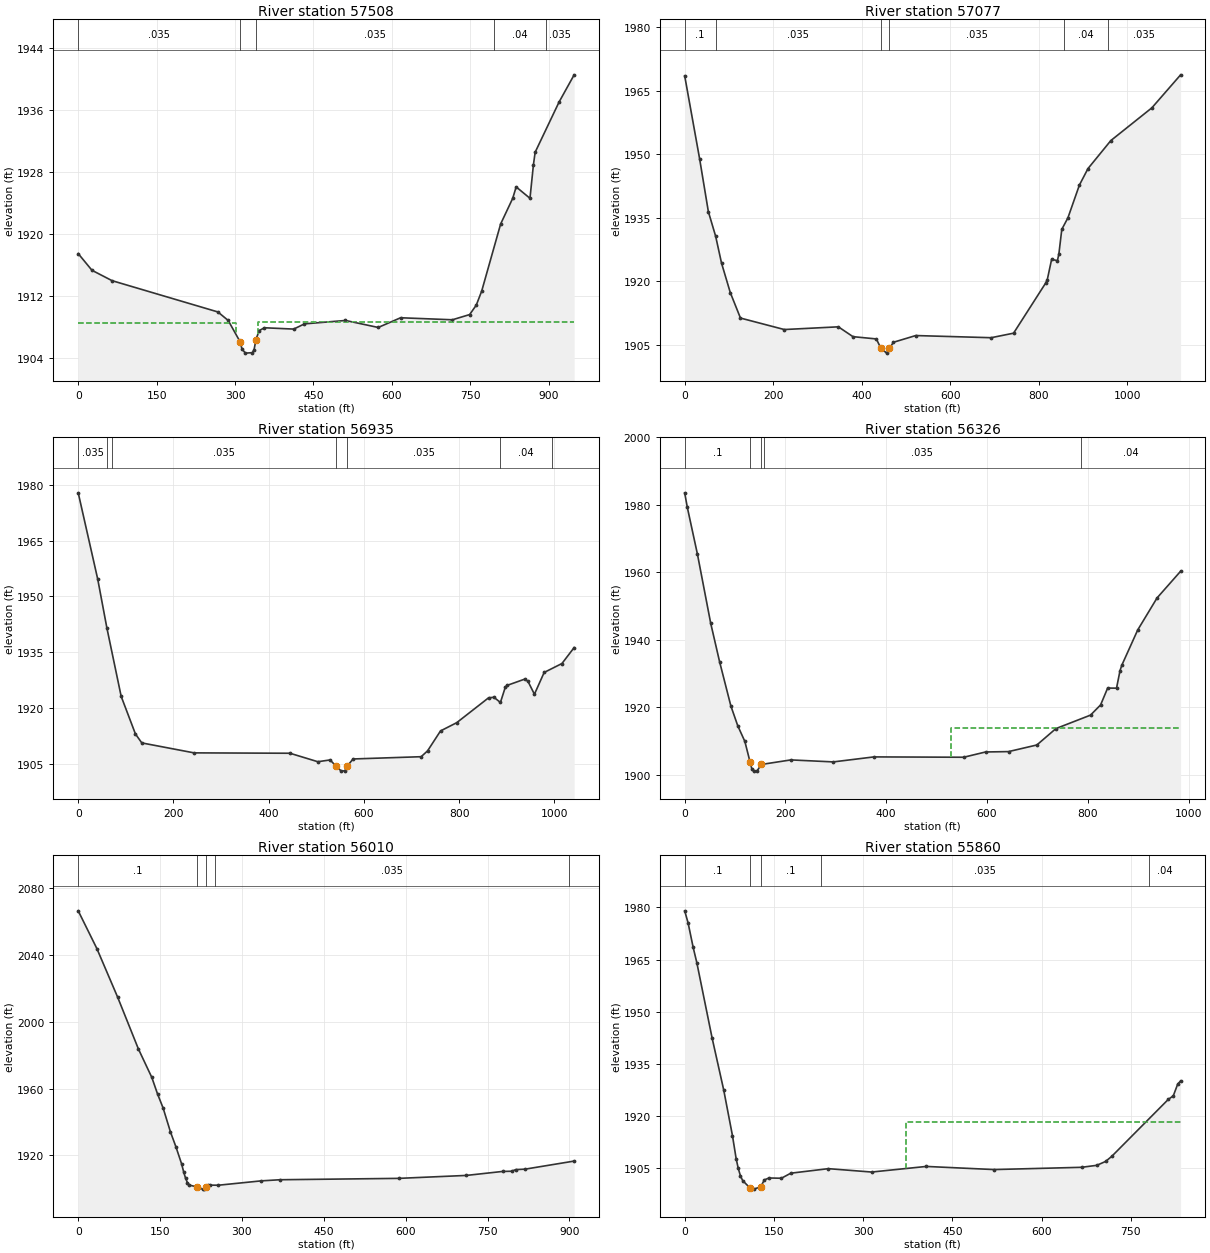
Type RM Length L Ch R = 1 ,57508   ,423.3,430.6,410.9
XS GIS Cut Line= 3
      2064962.35      175664.837     2065201.065      175753.813
     2065891.169      175682.199
#Sta/Elev= 30
       0 1917.46    26.3 1915.31    64.8 1913.97   267.1 1909.94   286.9 1908.84
   309.71906.087   313.3 1905.15   319.9 1904.63   333.1 1904.69   336.4 1905.08
   339.91906.349     346 1907.53   356.1  1907.9   412.2 1907.73   432.7  1908.4
   511.2 1908.84   573.8 1907.94   616.7 1909.19   715.7 1908.93   748.7  1909.6
   761.4 1910.82   771.7 1912.62     808 1921.28   831.1 1924.59   837.7 1926.06
   864.1 1924.59   870.7 1928.91     874 1930.53   919.8 1937.01   948.6 1940.51
#Mann= 5 ,-1 , 0
       0    .035       0   309.7    .045       0   339.9    .035       0
  794.76     .04       0  894.76    .035       0
#XS Ineff= 2 , 0
          301.89 1908.55     344          1908.7
Permanent Ineff=
       F       F
Bank Sta=309.7,339.9
XS Rating Curve= 0 ,0
Exp/Cntr=0.5,0.3

Type RM Length L Ch R = 1 ,57077   ,144.8,141.9,152.3
XS GIS Cut Line= 3
     2064979.711      176035.931     2065821.725      175946.955
     2066095.162      175951.296
#Sta/Elev= 30
       0 1968.56    33.7 1948.97    53.5 1936.47      70 1930.65    83.2 1924.34
     103 1917.37     126 1911.35     225 1908.64   347.1 1909.28   380.1 1906.96
   432.9 1906.42   442.8 1904.31     456 1903.07   462.6 1904.18   471.4 1905.63
   521.9 1907.22   692.2 1906.71   742.9 1907.78   815.6 1919.65   818.9 1920.34
   828.8  1925.2     842 1924.91   845.3 1926.55   851.8 1932.29   865.7 1935.03
   891.6 1942.76     911 1946.65   962.6 1953.26  1055.3 1960.99  1120.2 1968.78
#Mann= 6 ,-1 , 0
       0      .1       0      70    .035       0   442.8    .045       0
   462.6    .035       0   856.7     .04       0   956.7    .035       0
Bank Sta=442.8,462.6
XS Rating Curve= 0 ,0
Exp/Cntr=0.3,0.1

Type RM Length L Ch R = 1 ,56935   ,585.4,609.1,626.8
XS GIS Cut Line= 5
2064983.38649376176096.8042371232065333.99387233176036.354689092
2065487.13272734176112.9241165982065523.40245616176100.834206992
2065982.81902119176225.763272921
#Sta/Elev= 30
       0 1977.83      41 1954.59    60.2 1941.48    90.2 1923.08   120.1 1912.98
   133.5 1910.56   243.3 1907.88   444.6 1907.78   503.1  1905.5   528.9 1905.98
  540.92 1904.36   552.4 1902.97     560 1903.07   564.8 1904.32   577.1 1906.24
   720.1 1906.85   733.5 1908.42   760.7 1913.78   794.7    1916   861.7  1922.7
   872.9 1922.83   886.5 1921.44   896.7 1925.53   900.1 1926.01   937.5 1927.72
   944.3 1927.13   957.9 1923.65   978.3 1929.51  1015.7 1931.92  1041.3 1936.21
#Mann= 7 ,-1 , 0
       0    .035       0      60      .1       0      70    .035       0
  540.92    .045       0   564.8    .035       0  885.23     .04       0
  995.23      .1       0
Bank Sta=540.92,564.8
XS Rating Curve= 0 ,0
Exp/Cntr(USF)=0,0
Exp/Cntr=0.3,0.1

Type RM Length L Ch R = 1 ,56326   ,316.2,316,314.7
XS GIS Cut Line= 3
     2064994.902      176239.924     2065090.388      176255.115
     2065919.381      176571.955
#Sta/Elev= 30
       0 1983.53     5.2 1979.25    25.2 1965.45    51.7 1944.88    69.3 1933.52
    91.6 1920.47   105.4 1914.55   119.4 1909.95     130 1903.72   133.5 1901.67
     137 1901.15     144 1901.32   152.41903.126   210.7 1904.47     295 1903.88
   375.6 1905.36   553.8 1905.26   597.1 1906.82   642.7 1906.93   698.9 1908.89
   736.7 1913.74   805.4 1917.73   825.4 1920.75   839.4 1925.74     857 1925.71
     864 1930.92   867.5  1932.5   899.1 1942.95   937.5 1952.43   984.2 1960.32
#Mann= 5 ,-1 , 0
       0      .1       0     130    .045       0   152.4      .1       0
  156.69    .035       0  786.69     .04       0
#XS Ineff= 2 , 0
                          528.81         1913.98
Permanent Ineff=
       F       F
Bank Sta=130,152.4
XS Rating Curve= 0 ,0
Exp/Cntr=0.3,0.1

Type RM Length L Ch R = 1 ,56010   ,147.7,150.6,150.7
XS GIS Cut Line= 2
 2064810.0977894176495.771254124 2065672.5113413176781.899114802
#Sta/Elev= 30
       0 2066.21    34.2 2043.63    72.3 2014.55   110.3 1983.62   134.9 1966.59
   145.3 1956.77   155.6 1948.29     169 1934.05     179 1925.16   189.4 1914.98
   193.2 1910.15   196.7 1906.38   200.2 1903.62   203.6 1902.28   217.9 1901.15
   227.8 1899.86   231.3 1900.09   234.7 1901.33   238.2  1902.1   241.6 1902.24
   256.9  1902.2     335 1904.79   369.5 1905.47   587.3 1906.29   711.1 1908.05
   777.4 1910.43   794.1 1910.55   801.6 1911.53   818.9 1911.81   908.6 1916.63
#Mann= 5 ,-1 , 0
       0      .1       0   217.9    .045       0   234.7      .1       0
     250    .035       0     900     .04       0
Bank Sta=217.9,234.7
XS Rating Curve= 0 ,0
Exp/Cntr(USF)=0,0
Exp/Cntr=0.3,0.1

Type RM Length L Ch R = 1 ,55860   ,764.3,769.8,757.2
XS GIS Cut Line= 2
     2064840.822      176632.719      2065585.18      177008.153
#Sta/Elev= 30
       0 1978.99     5.7 1975.55    14.3 1968.46    20.4  1964.1      46 1942.53
    65.6 1927.52    80.3 1914.41    86.5  1907.8      90 1905.02    93.8  1902.8
    97.5 1901.48   109.6 1899.39   115.9 1899.02   127.51899.645     134 1901.67
   141.6 1902.22   162.6 1902.15   178.4  1903.6   241.5  1904.9   314.3 1903.93
   406.2 1905.54   520.1 1904.64   667.1 1905.29   692.8 1905.86   707.5 1906.97
   717.8 1908.42     813 1924.81   821.4 1925.83   828.8  1929.2   833.7 1930.12
#Mann= 5 ,-1 , 0
       0      .1       0   109.6    .045       0   127.5      .1       0
     230    .035       0     780     .04       0
#XS Ineff= 2 , 0
                          372.32         1918.29
Permanent Ineff=
       F       F
Bank Sta=109.6,127.5
XS Rating Curve= 0 ,0
Exp/Cntr=0.3,0.1

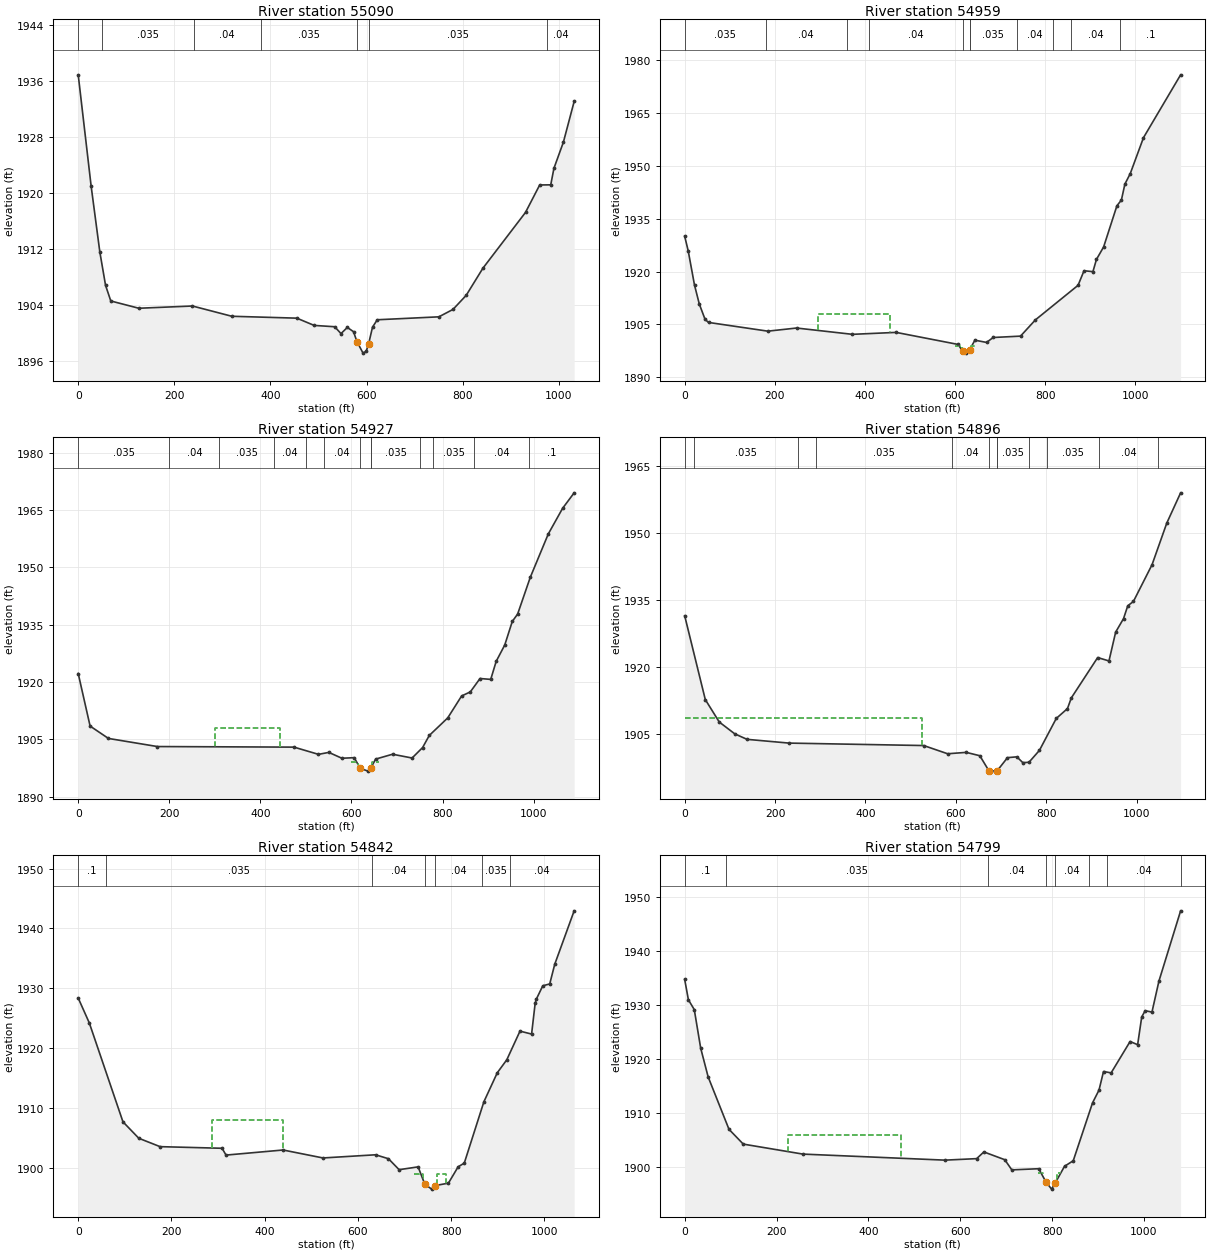
Type RM Length L Ch R = 1 ,55090   ,126.3,130.5,133.2
XS GIS Cut Line= 3
2064525.75706942177046.0660028472064861.07879919177253.965475302
2065498.19008574177265.701735844
#Sta/Elev= 30
       0 1936.93    26.9 1920.98      45 1911.54    56.9 1906.77    67.8 1904.53
   126.1 1903.49   237.7 1903.81   319.6 1902.34   454.8 1902.07   490.9 1901.03
   533.6 1900.84   546.7 1899.86   559.9 1900.74   572.8 1900.13   579.8 1898.72
   592.6 1897.06   599.2 1897.33   604.21898.397   612.3 1900.78   622.2 1901.84
   750.3 1902.26   779.7 1903.32   807.1 1905.33     842 1909.23   930.6 1917.22
   960.1 1921.15   983.1 1921.17   989.7 1923.53  1009.4 1927.28  1031.8 1933.11
#Mann= 7 ,-1 , 0
       0      .1       0      50    .035       0     240     .04       0
     380    .035       0   579.8    .045       0   604.2    .035       0
  974.54     .04       0
Bank Sta=579.8,604.2
XS Rating Curve= 0 ,0
Exp/Cntr(USF)=0,0
Exp/Cntr=0.5,0.3

Type RM Length L Ch R = 1 ,54959   ,33.4,32.7,32.4
XS GIS Cut Line= 4
      2064497.94      177086.278      2064964.52      177364.056
      2065122.94      177405.289     2065450.631      177624.473
#Sta/Elev= 30
       0 1930.04     7.8 1925.92    21.8 1916.18    32.5 1910.77    45.3 1906.42
    52.9 1905.56   184.6 1903.08   248.4 1903.97   372.4 1902.18   469.4 1902.73
   606.9 1899.31   617.31897.332   623.8 1896.84   632.3 1897.71   644.2 1900.52
   670.1 1899.88   684.8 1901.28   745.5 1901.67   778.6 1906.29   873.2  1916.1
   886.5 1920.25   906.2 1919.98   914.1 1923.47     930 1927.01   959.5 1938.71
   969.4 1940.31   977.2 1944.86   989.1 1947.84  1018.5 1958.06  1100.9  1975.9
#Mann= 11 ,-1 , 0
       0    .035       0     180     .04       0     360    .035       0
     410     .04       0   617.3    .045       0   632.3     .04       0
  633.01    .035       0  736.71     .04       0  816.71    .035       0
  856.71     .04       0  966.71      .1       0
#XS Ineff= 3 ,-1
     295     456    1908     600     615    1899     635     650    1899
Permanent Ineff=
       F       F       F
Bank Sta=617.3,632.3
XS Rating Curve= 0 ,0
Exp/Cntr=0.5,0.3

Type RM Length L Ch R = 1 ,54927   ,31.2,30.7,31.4
XS GIS Cut Line= 4
2064486.11305132177109.0907661822064969.04512003177400.453840843
2065120.51827811 177436.094583922065427.91968715177641.028856618
#Sta/Elev= 30
       0 1922.22    26.1 1908.48    66.4 1905.24   173.9 1903.12   473.8 1902.97
   527.6 1901.08   550.4 1901.59     579 1900.06     606 1900.21   619.5 1897.42
   636.3 1896.69   642.5 1897.54   653.2 1899.84   690.3 1901.11   733.2 1900.12
   756.3 1902.86     771 1906.03   811.5 1910.62     842 1916.36     861 1917.41
   882.4 1920.92   905.9 1920.69   917.9 1925.42   936.7 1929.69   953.2 1935.84
     965 1937.79   992.8 1947.41  1032.3 1958.74  1063.8 1965.46  1089.1  1969.5
#Mann= 13 ,-1 , 0
       0    .035       0     200     .04       0     310    .035       0
     430     .04       0     500    .035       0     540     .04       0
   619.5    .045       0   642.5     .04       0  644.02    .035       0
  749.63     .04       0  779.63    .035       0  869.63     .04       0
  989.63      .1       0
#XS Ineff= 3 ,-1
     300     444    1908     600     615    1899     645     660    1899
Permanent Ineff=
       F       F       F
Bank Sta=619.5,642.5
XS Rating Curve= 0 ,0
Exp/Cntr(USF)=0,0
Exp/Cntr=0.5,0.3

Type RM Length L Ch R = 1 ,54896   ,61.9,54,43.9
XS GIS Cut Line= 4
2064443.60324563177114.8069574492064928.14314514177418.273122888
2065155.67570488177478.7718693722065384.23602571177657.220034302
#Sta/Elev= 30
       0 1931.56    45.6 1912.78    76.5 1907.75   110.8  1905.1   137.9 1903.87
   230.8 1903.03   528.8 1902.48   581.7 1900.64   622.8 1900.95   652.9  1900.2
   673.21896.795   676.7 1896.75   691.51896.854   714.1 1899.77   734.8 1899.95
     748 1898.65   761.6 1898.73   784.7 1901.39     822 1908.55   846.8 1910.76
   855.3 1913.15   913.6 1922.19   938.6 1921.43   953.4 1927.89   970.8 1930.91
   980.2 1933.79   992.7 1934.76  1033.9 1942.99  1066.6 1952.34  1097.1 1959.09
#Mann= 12 ,-1 , 0
       0      .1       0      20    .035       0     250     .04       0
     290    .035       0  591.73     .04       0   673.2    .045       0
   691.5     .04       0  691.73    .035       0  761.73     .04       0
  801.73    .035       0  917.16     .04       0 1047.16      .1       0
#XS Ineff= 2 , 0
          526.06 1908.74
Permanent Ineff=
       F       F
Bank Sta=673.2,691.5
XS Rating Curve= 0 ,0
Exp/Cntr(USF)=0,0
Exp/Cntr=0.5,0.3

Type RM Length L Ch R = 1 ,54842   ,42,42.6,42.5
XS GIS Cut Line= 4
2064402.08780702177149.0979665512065020.75639844177509.736486915
2065085.37916239177483.2329046272065305.21825695177653.353627049
#Sta/Elev= 30
       0 1928.36    23.8  1924.2      96 1907.67     130 1904.92   175.6 1903.52
   308.6 1903.25   317.1 1902.11   439.5 1902.96   525.1 1901.63   637.9 1902.16
   665.6  1901.5   688.4 1899.67   729.2 1900.14   743.4 1897.26   758.1 1896.42
   765.6 1897.01   794.2 1897.42     815 1900.15   828.2 1900.77   870.3 1911.03
     899 1915.87   919.4 1918.04   947.7 1922.83   972.6 1922.34   980.2 1927.45
   982.6 1928.15   996.6 1930.41  1011.5 1930.72  1022.3 1934.02  1063.9 1942.94
#Mann= 7 ,-1 , 0
       0      .1       0      60    .035       0     630     .04       0
   743.4    .045       0   765.6     .04       0  865.95    .035       0
  925.95     .04       0
#XS Ineff= 3 ,-1
     288     440    1908     720     740    1899     770     790    1899
Permanent Ineff=
       F       F       F
Bank Sta=743.4,765.6
XS Rating Curve= 0 ,0
Exp/Cntr(USF)=0,0
Exp/Cntr=0.5,0.3

Type RM Length L Ch R = 1 ,54799   ,90,106.3,117.7
XS GIS Cut Line= 4
     2064382.923      177170.9142065019.57665019177553.476148616
2065111.17125692177518.9715695752065299.72157818177666.206513925
#Sta/Elev= 30
       0 1934.79     8.1 1931.02    20.9  1929.2    34.9 1922.04    51.1 1916.73
    96.5 1907.02   127.6 1904.28   257.4 1902.43   566.9 1901.31   635.8 1901.59
   651.5 1902.83     697 1901.39   712.3 1899.51     771 1899.72     787 1897.21
     799 1895.94   807.4 1897.16   827.1 1900.17   846.1  1901.2   888.1 1911.92
   902.2 1914.29     912 1917.73   928.6 1917.48   969.9 1923.29   986.3  1922.7
   995.2 1927.84  1002.7    1929  1017.5 1928.74  1032.7 1934.49  1079.9  1947.5
#Mann= 8 ,-1 , 0
       0      .1       0      90    .035       0     660     .04       0
     787    .045       0   807.4     .04       0  880.63    .035       0
  920.63     .04       0 1079.86      .1       0
#XS Ineff= 3 ,-1
     225     470    1906     770     780    1899     810     820    1899
Permanent Ineff=
       F       F       F
Bank Sta=787,807.4
XS Rating Curve= 0 ,0
Exp/Cntr=0.5,0.3

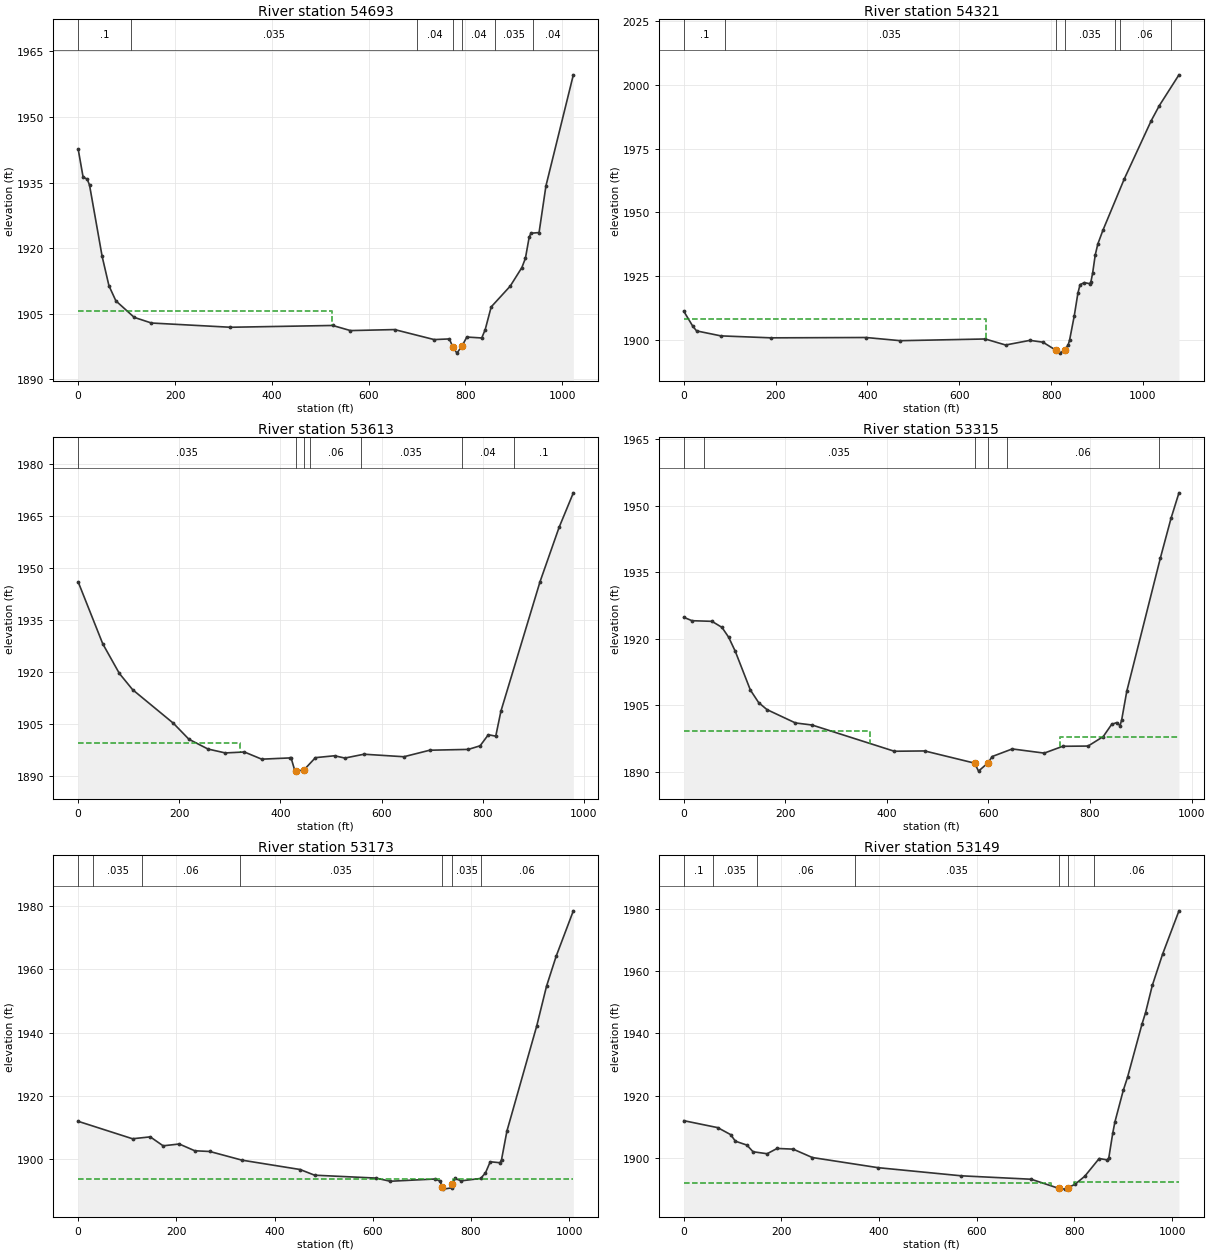
Type RM Length L Ch R = 1 ,54693   ,368.2,372,370.5
XS GIS Cut Line= 2
2064362.91897967177189.1945850882065217.27012546177751.428529388
#Sta/Elev= 30
       0 1942.65    10.2 1936.23    18.7 1935.78    23.5 1934.39    49.5 1918.09
    63.6 1911.37    77.9 1907.92   115.8 1904.14   151.4 1902.85   314.5 1901.88
   525.6 1902.29   562.4 1901.12   653.5 1901.35   735.3 1899.06   766.7 1899.21
   774.1 1897.29   782.4 1895.96   793.3  1897.7   802.8 1899.64   833.6 1899.43
   840.7 1901.33   853.1 1906.54   892.4 1911.29   916.5 1915.55   923.8 1917.66
   931.6 1922.51   935.2  1923.4     952 1923.55   966.2 1934.23  1022.8 1959.65
#Mann= 7 ,-1 , 0
       0      .1       0     110    .035       0     700     .04       0
   774.1    .045       0   793.3     .04       0     860    .035       0
     940     .04       0
#XS Ineff= 2 , 0
          525.13 1905.56
Permanent Ineff=
       F       F
Bank Sta=774.1,793.3
XS Rating Curve= 0 ,0
Exp/Cntr(USF)=0,0
Exp/Cntr=0.3,0.1

Type RM Length L Ch R = 1 ,54321   ,710.8,708.1,703.2
XS GIS Cut Line= 2
     2064285.266      177403.119     2065157.662      178036.799
#Sta/Elev= 30
       0 1911.17    19.5 1905.32    27.9 1903.46    80.7 1901.51   190.1 1900.74
   396.9 1900.87   471.7 1899.62   656.4 1900.29   700.8 1897.93   753.7 1899.75
   782.1 1899.03   809.51895.971   818.3 1894.74   829.21895.841   837.1 1898.02
   840.2 1899.92   850.3 1909.37   858.2 1918.25   862.9 1921.62   872.3 1922.41
     884    1922   886.4 1922.58   890.4 1926.24     896  1933.3   901.6 1937.56
   912.7 1942.96   959.2  1963.1  1017.9 1985.97  1035.6  1991.9  1078.3 2003.96
#Mann= 7 ,-1 , 0
       0      .1       0      90    .035       0   809.5    .045       0
   829.2    .035       0     940     .04       0     950     .06       0
    1060      .1       0
#XS Ineff= 2 , 0
          657.18 1908.28
Permanent Ineff=
       F       F
Bank Sta=809.5,829.2
XS Rating Curve= 0 ,0
Exp/Cntr=0.3,0.1

Type RM Length L Ch R = 1 ,53613   ,302.7,297.9,292
XS GIS Cut Line= 4
     2064016.495      178196.579     2064164.932      178201.788
     2064828.995      178402.308     2064955.839      178453.466
#Sta/Elev= 30
       0 1946.11    48.6 1928.25    81.4 1919.71   107.7 1915.01   188.1 1905.35
     219 1900.71   256.7 1897.89   290.9 1896.77   328.6 1897.04   362.9 1894.97
   418.6 1895.33   421.2 1895.21     428 1891.84   429.9 1891.67     433 1891.52
   446.61891.911   469.1 1895.41   506.8 1895.95   527.4 1895.29   565.1  1896.4
   643.9 1895.67     695 1897.55   771.4 1897.79   794.7 1898.83   810.9 1902.02
   825.6 1901.61   835.8 1908.81     913 1946.11   950.8 1961.84     979 1971.81
#Mann= 7 ,-1 , 0
       0    .035       0   429.9    .045       0   446.6    .035       0
  458.53     .06       0  558.53    .035       0  758.53     .04       0
  862.21      .1       0
#XS Ineff= 2 , 0
           319.6 1899.73
Permanent Ineff=
       F       F
Bank Sta=429.9,446.6
XS Rating Curve= 0 ,0
Exp/Cntr=0.3,0.1

Type RM Length L Ch R = 1 ,53315   ,143.5,142,146.3
XS GIS Cut Line= 3
2063921.00328634178592.7227449422064236.20571232178609.488831431
2064888.40647671178512.245529798
#Sta/Elev= 30
       0 1924.85    16.1 1924.08    55.5 1923.94    75.2 1922.57    88.4 1920.35
   101.5 1917.15   131.1 1908.46   147.5 1905.61   163.9 1904.04   219.8 1901.04
   252.7 1900.57   414.6 1894.66   474.3 1894.73   572.7 1891.98   580.4 1890.18
   598.8 1892.02   607.3 1893.47   646.8 1895.18   709.8 1894.24   746.3 1895.78
   796.1 1895.83   825.9 1897.96   842.5 1900.71   852.4 1901.12   859.1 1900.42
   862.4  1901.8   872.3 1908.16   938.7  1938.3   959.5 1947.17   975.1  1952.9
#Mann= 6 ,-1 , 0
       0     .06       0      40    .035       0   572.7    .045       0
   598.8    .035       0  635.65     .06       0  935.65      .1       0
#XS Ineff= 2 , 0
          367.51 1899.26  740.57         1897.82
Permanent Ineff=
       F       F
Bank Sta=572.7,598.8
XS Rating Curve= 0 ,0
Exp/Cntr(USF)=0,0
Exp/Cntr=0.5,0.3

Type RM Length L Ch R = 1 ,53173   ,23.5,23.6,23
XS GIS Cut Line= 3
     2063833.012      178663.193     2064699.763      178687.841
      2064814.78      178770.306
#Sta/Elev= 30
       0 1911.94   110.7 1906.42   146.8 1907.02     173 1904.19   205.9 1904.76
   237.5 1902.62   268.2 1902.39   333.9 1899.64     452 1896.69   481.6 1894.89
   606.3 1893.98   635.6 1892.97   727.3 1893.69   737.6 1892.97   740.9 1891.25
   744.1 1890.48   760.5 1890.88   762.41892.022   767.1 1893.86   780.2  1893.1
   819.6 1893.85   829.5 1895.58   839.3 1899.14     859 1898.84   862.3 1899.78
   873.3 1908.85   933.9 1942.05     954 1954.71   973.6 1964.18  1008.6 1978.55
#Mann= 7 ,-1 , 0
       0      .1       0      30    .035       0     130     .06       0
     330    .035       0   740.9    .045       0   762.4    .035       0
     820     .06       0
#XS Ineff= 2 , 0
          736.73 1893.84  764.49         1893.79
Permanent Ineff=
       F       F
Bank Sta=740.9,762.4
XS Rating Curve= 0 ,0
Exp/Cntr=0.5,0.3

Type RM Length L Ch R = 1 ,53149   ,257.8,259.1,254.8
XS GIS Cut Line= 3
2063811.74237104178682.8422967172064683.85509981178710.348747634
2064791.38050032178802.622249842
#Sta/Elev= 30
       0 1911.92    69.6 1909.68    95.9 1907.44   105.7 1905.32   129.3 1904.07
   141.8 1901.93   170.7 1901.29   191.1 1902.99   223.9 1902.77   263.3 1900.07
   397.8 1896.81   568.5 1894.19   711.6 1893.09     7681890.158   781.7 1889.91
     7871890.392   801.6 1891.49   821.3 1894.06   850.8 1899.75   867.2 1899.31
   870.5 1899.96   878.5 1907.83   882.9 1911.45   900.1 1921.65   908.8 1925.84
   938.3 1942.88   945.7 1946.61   959.6 1955.41   980.6 1965.43  1014.2 1979.39
#Mann= 7 ,-1 , 0
       0      .1       0      60    .035       0     150     .06       0
     350    .035       0     768    .045       0     787    .035       0
     840     .06       0
#XS Ineff= 2 , 0
          752.06 1891.93  798.34         1892.23
Permanent Ineff=
       F       F
Bank Sta=768,787
XS Rating Curve= 0 ,0
Exp/Cntr=0.5,0.3