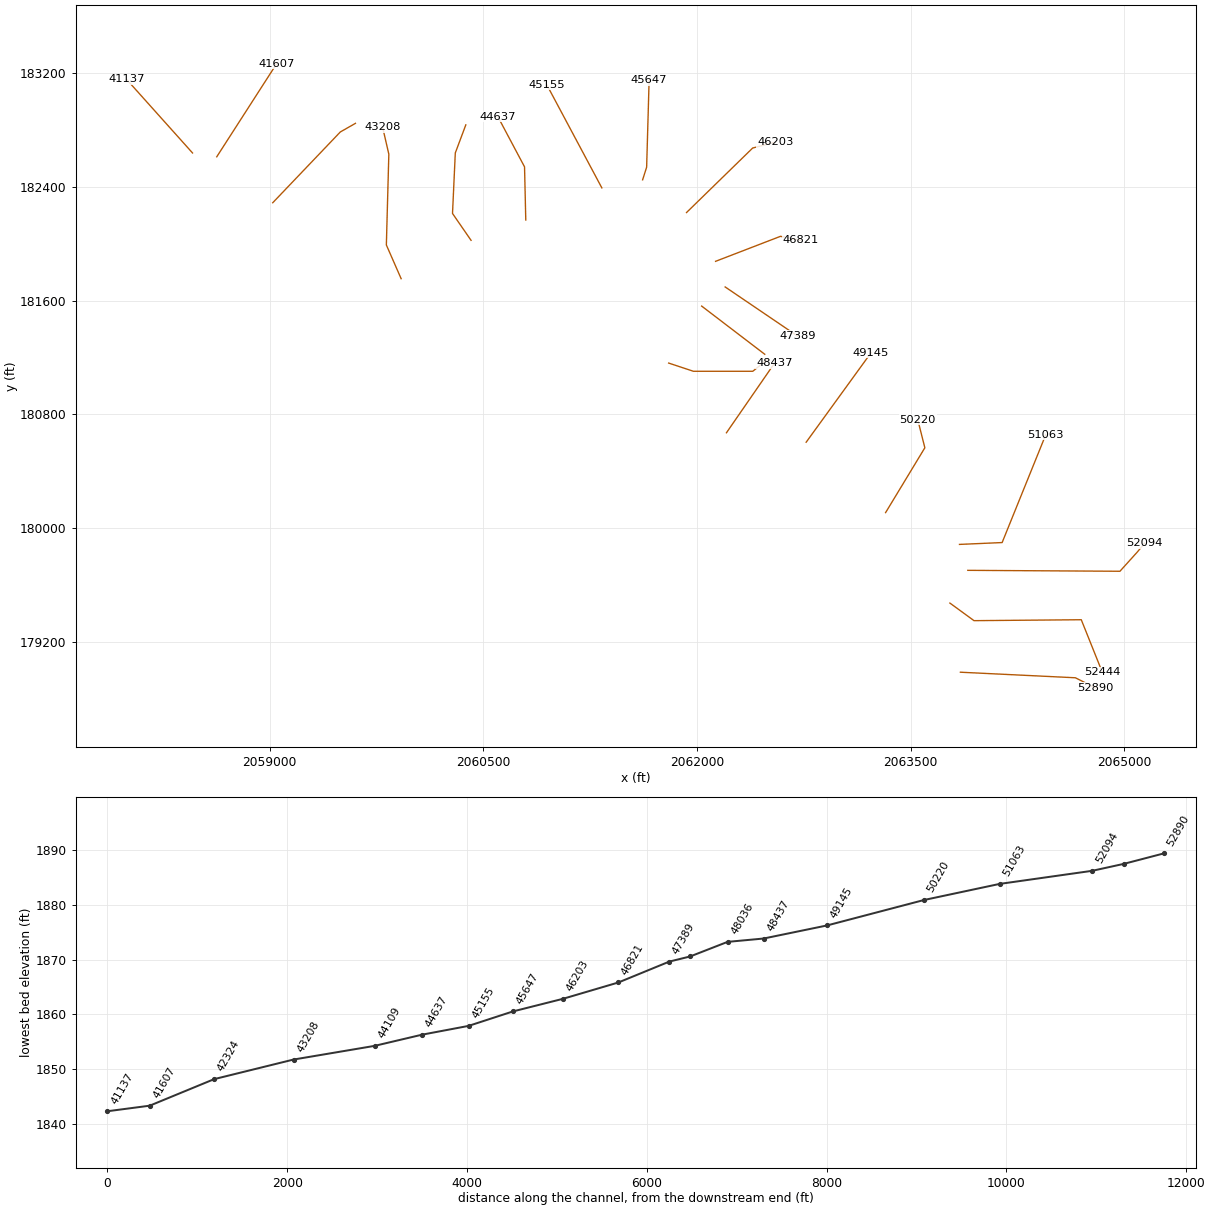
HEC-RAS study HNSCK.prj: HNSCK

--- HNSCK.g01 (geometry) --- (continued)

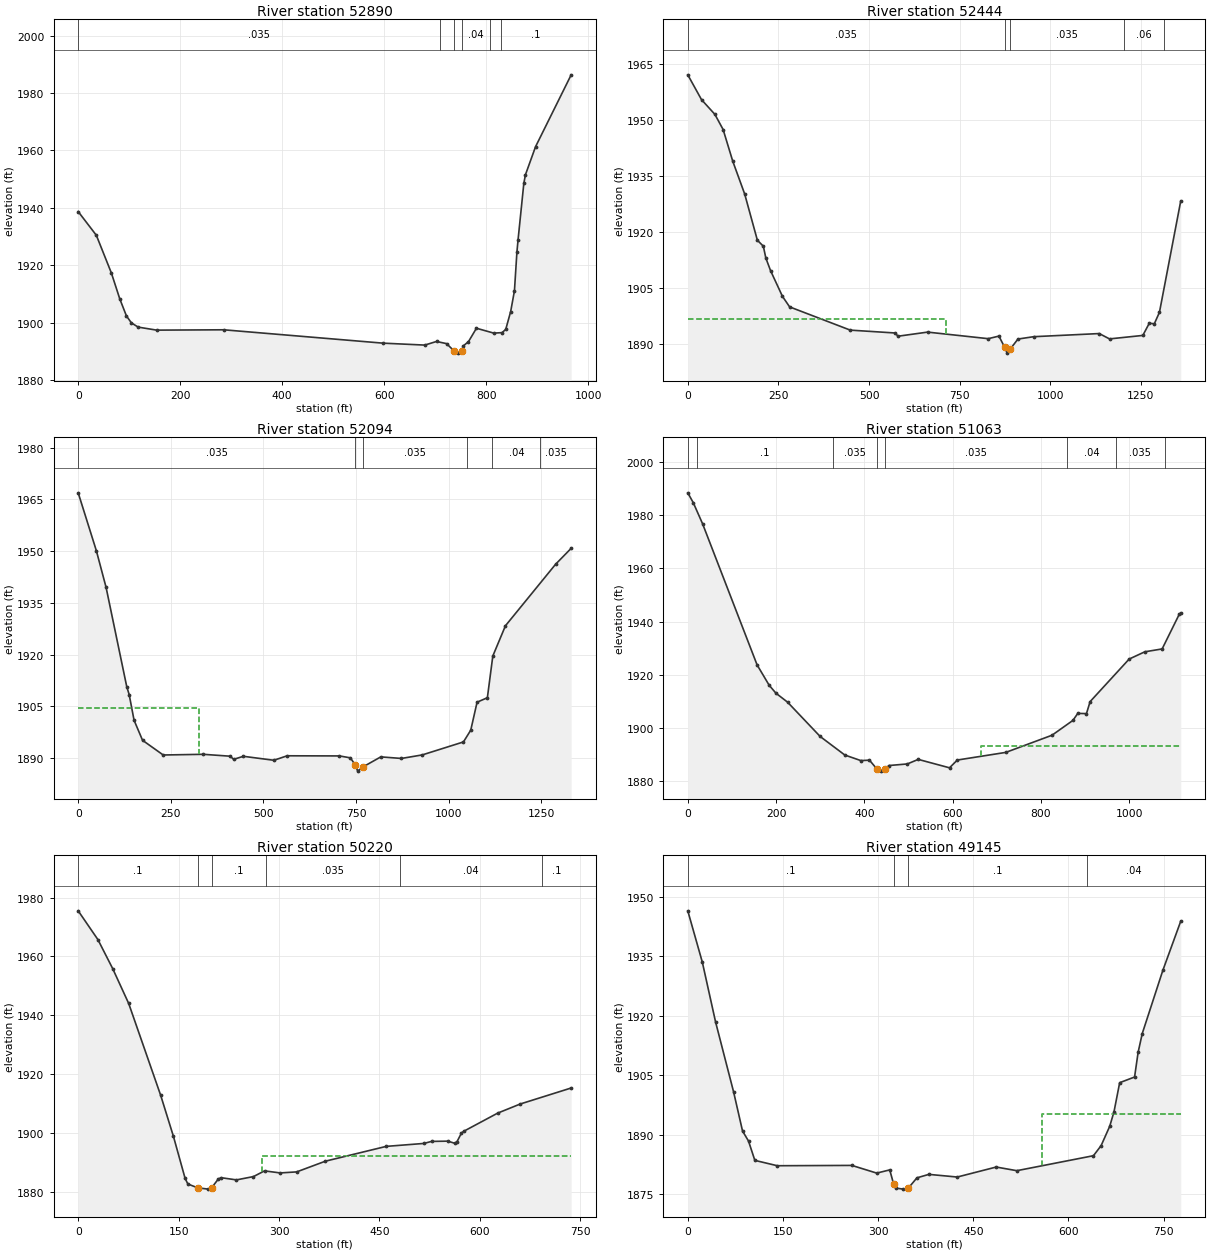
Type RM Length L Ch R = 1 ,52890   ,443.8,446.8,445.6
XS GIS Cut Line= 3
     2063849.069       178987.32      2064656.36      178948.258
     2064797.419      178876.643
#Sta/Elev= 30
       0 1938.66    35.6  1930.4    65.1 1917.25    81.5 1908.26    94.6  1902.3
   104.5 1899.85   117.7 1898.41   153.8 1897.36   285.2 1897.48   597.2 1892.83
   679.4 1892.15   702.4 1893.41   722.1 1892.66     7371890.091   745.1 1889.35
     7521890.125   754.9 1891.86   765.1 1893.35   780.7 1898.02   814.7 1896.32
   830.8 1896.49   838.1  1897.6   847.8 1903.84   855.2 1911.07     860 1924.43
   862.3 1928.87   873.6 1948.49   876.8 1951.51   896.6 1961.27   966.4  1986.3
#Mann= 6 ,-1 , 0
       0    .035       0     710     .04       0     737    .045       0
     752     .04       0  808.24     .06       0  828.24      .1       0
Bank Sta=737,752
XS Rating Curve= 0 ,0
Exp/Cntr=0.3,0.1

Type RM Length L Ch R = 1 ,52444   ,348.6,350,350.4
XS GIS Cut Line= 4
     2063775.284      179473.431     2063944.555      179349.733
     2064697.593      179356.244     2064845.162       178987.32
#Sta/Elev= 30
       0 1961.97    37.9 1955.32    74.8 1951.38    97.5 1947.32   124.1 1938.83
     157 1930.05     192 1917.67   208.5 1916.07   215.3 1912.92   228.4 1909.52
   261.2 1902.64     281 1899.82   448.3  1893.6   572.9 1892.83   579.5 1891.96
   661.6 1893.07   828.8 1891.31   858.4    1892   874.31888.987   881.3 1887.44
   890.31888.611   910.9 1891.21   954.2 1891.84  1135.2 1892.68  1163.5 1891.25
  1255.4 1892.18  1273.2 1895.43  1287.2 1895.31  1301.3 1898.38  1360.1 1928.22
#Mann= 5 ,-1 , 0
       0    .035       0   874.3    .045       0   890.3    .035       0
 1202.72     .06       0 1312.72     .04       0
#XS Ineff= 2 , 0
          711.43 1896.62
Permanent Ineff=
       F       F
Bank Sta=874.3,890.3
XS Rating Curve= 0 ,0
Exp/Cntr=0.3,0.1

Type RM Length L Ch R = 1 ,52094   ,1005.1,1030.9,1038
XS GIS Cut Line= 4
     2063901.152      179703.466      2064968.86      179696.955
     2065090.388      179831.504     2065142.471      179894.438
#Sta/Elev= 30
       0 1966.93    49.1 1950.11    75.3 1939.49   131.1 1910.67   137.6 1908.41
   150.8 1900.95   173.7 1895.13   229.5 1890.86   337.8 1891.06     410 1890.51
   419.8 1889.61     446 1890.48   528.1 1889.33   564.2 1890.63   705.2 1890.59
   734.8 1890.03   748.4 1887.88   754.4 1886.18   769.71887.466   816.8 1890.31
   872.5 1889.86   928.6 1890.88  1039.9 1894.65  1059.6 1898.06  1076.7 1906.18
  1104.5 1907.48  1119.2 1919.58  1153.3 1928.36  1288.7 1946.21  1330.7 1950.83
#Mann= 6 ,-1 , 0
       0    .035       0   748.4    .045       0   769.7    .035       0
    1050     .06       0 1117.73     .04       0 1247.73    .035       0
#XS Ineff= 2 , 0
          325.27 1904.64
Permanent Ineff=
       F       F
Bank Sta=748.4,769.7
XS Rating Curve= 0 ,0
Exp/Cntr=0.3,0.1

Type RM Length L Ch R = 1 ,51063   ,843.6,843.1,837.9
XS GIS Cut Line= 3
     2063842.558      179885.758     2064142.037      179898.778
     2064448.027      180656.157
#Sta/Elev= 30
       0 1988.42    12.5 1984.69    33.4 1976.83     157 1923.72   184.4 1916.06
   199.7 1913.09     226 1909.72   299.8 1896.82   355.7 1889.84     392 1887.75
   411.5 1887.91   427.71884.721   437.1 1883.79   447.4 1884.74   455.8  1885.9
   497.3 1886.49     522  1888.2   592.8 1885.04   610.5 1887.96   720.2 1890.83
   824.9 1897.28   872.4 1902.87   883.3 1905.49     903 1905.42   911.3 1909.93
   999.7 1925.92  1035.1 1928.65  1074.4 1929.73    1113  1942.7  1116.6 1943.25
#Mann= 8 ,-1 , 0
       0    .035       0      20      .1       0  329.76    .035       0
   427.7    .045       0   447.4    .035       0  859.76     .04       0
  969.76    .035       0 1079.76      .1       0
#XS Ineff= 2 , 0
                          664.76         1893.36
Permanent Ineff=
       F       F
Bank Sta=427.7,447.4
XS Rating Curve= 0 ,0
Exp/Cntr=0.3,0.1

Type RM Length L Ch R = 1 ,50220   ,1064.6,1075.1,1064.8
XS GIS Cut Line= 3
     2063323.895      180109.282     2063599.503      180565.011
     2063549.589      180762.494
#Sta/Elev= 30
       0 1975.51    29.4 1965.74    51.5 1955.87    75.4 1944.01   123.2 1912.76
   142.3 1898.76   159.7 1884.49   163.8  1882.6   178.31881.303   194.2 1880.85
   199.3 1881.31   209.2 1884.27   213.4 1884.74   236.4 1883.99   261.8 1885.12
   278.3 1887.06   301.6 1886.36   326.3 1886.71   369.3 1890.36   460.1 1895.39
   516.3 1896.39   527.8 1897.08     552 1897.17   562.2 1896.46   565.6 1896.91
   572.4  1899.9   575.7 1900.51   626.5  1906.7   660.3 1909.81   736.3 1915.25
#Mann= 6 ,-1 , 0
       0      .1       0   178.3    .045       0   199.3      .1       0
     280    .035       0     480     .04       0  692.59      .1       0
#XS Ineff= 2 , 0
                          274.75         1892.17
Permanent Ineff=
       F       F
Bank Sta=178.3,199.3
XS Rating Curve= 0 ,0
Exp/Cntr=0.3,0.1

Type RM Length L Ch R = 1 ,49145   ,690.9,707.3,701.8
XS GIS Cut Line= 2
     2062766.169      180604.074     2063221.898      181233.414
#Sta/Elev= 30
       0 1946.41    22.9 1933.48    43.9 1918.32    72.2 1900.75    86.3 1890.88
    95.7 1888.36   105.7 1883.48   141.1 1882.13   258.6 1882.21   297.8 1880.27
   318.3 1881.08   324.61877.426   327.5  1876.5   339.6 1876.23   347.51876.473
   361.2 1879.08     380 1879.95   424.7 1879.28   486.1  1881.8   518.6 1880.88
   639.4 1884.66   651.5 1887.21   665.1 1892.11   671.8 1895.76   680.7 1903.07
   704.2  1904.5   709.8 1910.74   716.3 1915.46   748.7 1931.37     777 1943.81
#Mann= 4 ,-1 , 0
       0      .1       0   324.6    .045       0   347.5      .1       0
     630     .04       0
#XS Ineff= 2 , 0
                          558.06         1895.05
Permanent Ineff=
       F       F
Bank Sta=324.6,347.5
XS Rating Curve= 0 ,0
Exp/Cntr=0.3,0.1

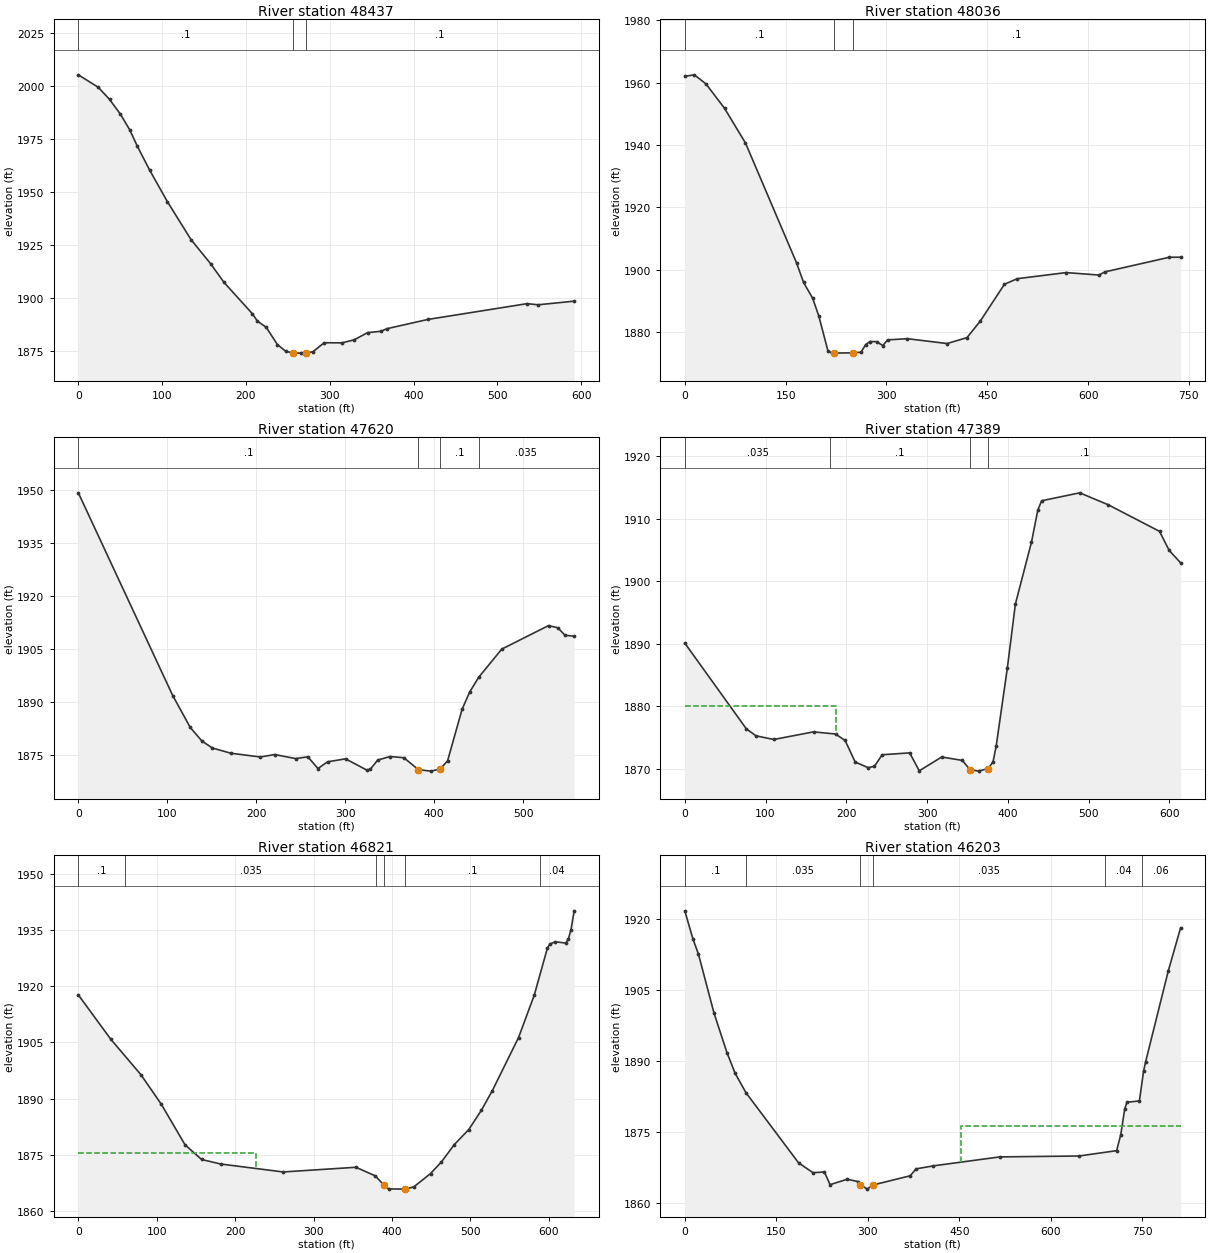
Type RM Length L Ch R = 1 ,48437   ,424.7,401,388.8
XS GIS Cut Line= 2
     2062206.599      180670.538     2062542.536      181157.517
#Sta/Elev= 30
       0 2005.28    23.7 1999.41    37.3 1993.67    50.2  1986.7    61.4 1979.26
    70.1  1971.8      85 1960.35   106.2 1945.41   134.5 1927.43   157.8 1916.09
   173.7 1907.31   207.7 1892.43   213.6    1889   224.2 1886.02   237.5 1877.91
   247.7 1874.62   256.41873.978   265.4 1873.84   271.41873.977   279.9 1874.46
   293.3 1878.75   314.6 1878.68   329.2 1880.14   345.1 1883.51   361.1 1884.17
     368 1885.36   416.9 1889.74   535.5 1897.21   548.4 1896.67   591.6 1898.38
#Mann= 3 ,-1 , 0
       0      .1       0   256.4    .045       0   271.4      .1       0
Bank Sta=256.4,271.4
XS Rating Curve= 0 ,0
Exp/Cntr=0.3,0.1

Type RM Length L Ch R = 1 ,48036   ,434.4,416.7,409.1
XS GIS Cut Line= 4
     2061800.895      181160.586     2061974.828      181102.829
     2062391.495      181102.829     2062498.812      181189.232
#Sta/Elev= 30
       0 1962.07    14.2 1962.54    31.5 1959.63    59.2 1951.77    90.3 1940.66
   166.3 1902.18   176.7 1895.91   190.2 1890.86   199.4 1885.12   213.1 1873.84
   219.7 1873.23   222.31873.254   249.71873.319   262.3 1873.53   268.9 1875.94
   275.5 1876.95   285.3 1876.91   294.6 1875.66   301.7 1877.48   331.2 1877.86
   390.3 1876.31   419.8  1878.2   439.5 1883.47   475.6 1895.34   494.7 1897.12
   567.4 1899.08   616.1 1898.29   625.2 1899.31   721.1 1904.01   737.7    1904
#Mann= 3 ,-1 , 0
       0      .1       0   222.3    .045       0   249.7      .1       0
Bank Sta=222.3,249.7
XS Rating Curve= 0 ,0
Exp/Cntr=0.3,0.1

Type RM Length L Ch R = 1 ,47620   ,230.1,231,231.2
XS GIS Cut Line= 2
     2062032.662      181561.105     2062475.371      181222.563
#Sta/Elev= 30
       0 1949.08   106.1 1891.89   125.8 1882.89   138.9 1879.07   150.6  1877.1
   171.3 1875.63   204.5 1874.56   220.8 1875.25   244.2 1874.11     258 1874.61
   269.3 1871.31   280.1 1873.19   300.3 1874.04   324.1 1870.89   328.2 1871.12
   336.5 1873.69   350.3 1874.69   365.9 1874.35   382.3 1870.98   396.3 1870.57
   406.51871.156     415 1873.45   431.3 1887.98   439.7 1892.82   450.1 1897.08
   475.9 1904.99   528.5 1911.63   538.9 1911.01   547.1 1908.89   557.3 1908.63
#Mann= 4 ,-1 , 0
       0      .1       0   382.3    .045       0   406.5      .1       0
     450    .035       0
Bank Sta=382.3,406.5
XS Rating Curve= 0 ,0
Exp/Cntr=0.3,0.1

Type RM Length L Ch R = 1 ,47389   ,552.2,567.3,584.1
XS GIS Cut Line= 2
     2062197.593      181695.653     2062705.405      181350.601
#Sta/Elev= 30
       0 1890.11    76.1 1876.42      88 1875.29   110.2  1874.7   159.4 1875.92
   186.7 1875.57   198.5 1874.54     211 1871.09   226.9  1870.2   234.8 1870.41
   244.4 1872.26   278.4 1872.56   290.3 1869.69   318.1  1871.9   343.7 1871.35
   353.11869.883   363.9 1869.64   375.6 1870.06   381.6 1871.11   385.5 1873.61
   399.3 1886.07   409.3 1896.35   429.2 1906.24   437.1 1911.38   441.8 1912.87
     489 1914.14   524.4 1912.22   587.8 1907.98   599.7 1904.94   613.9 1902.94
#Mann= 4 ,-1 , 0
       0    .035       0     180      .1       0   353.1    .045       0
   375.6      .1       0
#XS Ineff= 2 , 0
          186.67 1880.04
Permanent Ineff=
       F       F
Bank Sta=353.1,375.6
XS Rating Curve= 0 ,0
Exp/Cntr=0.3,0.1

Type RM Length L Ch R = 1 ,46821   ,609.8,617.8,622.8
XS GIS Cut Line= 3
     2062130.319      181875.775     2062586.048      182051.556
     2062727.107      182023.344
#Sta/Elev= 30
       0 1917.71    41.2 1905.92    79.8  1896.4   105.8 1888.51   136.1 1877.66
   157.2 1873.75   181.8 1872.53   261.2 1870.42   354.1 1871.67   378.7 1869.37
   390.11866.812   395.7 1865.89   416.31865.838   417.4 1865.83     428 1866.46
   449.1 1869.98   463.1 1873.11   479.4 1877.72   497.8 1881.72     514 1886.89
     528 1892.16   561.4 1906.33   581.5  1917.7   598.2 1930.25   601.5 1931.31
   608.2 1931.91   621.6 1931.56     625 1932.69   628.3 1935.17   632.3 1940.17
#Mann= 6 ,-1 , 0
       0      .1       0      60    .035       0     380      .1       0
   390.1    .045       0   416.3      .1       0  588.45     .04       0
#XS Ineff= 2 , 0
          226.61 1875.54
Permanent Ineff=
       F       F
Bank Sta=390.1,416.3
XS Rating Curve= 0 ,0
Exp/Cntr=0.3,0.1

Type RM Length L Ch R = 1 ,46203   ,544.5,556.5,567.7
XS GIS Cut Line= 3
     2061926.325      182218.657     2062390.735      182672.216
     2062549.155      182713.449
#Sta/Elev= 30
       0 1921.82    13.2 1915.92    22.4 1912.64    47.8 1900.19    69.1 1891.78
    82.6 1887.37   100.3 1883.28   186.5 1868.42   210.2 1866.33   228.8 1866.49
   238.2 1863.79   265.9 1864.94   283.8 1864.46   287.81863.786   299.2 1862.85
   308.21863.721   369.6 1865.68     379 1867.14   407.4 1867.78   516.4 1869.68
   646.1 1869.87   707.9    1871   714.7 1874.41   721.2 1879.87   724.8 1881.26
   745.2 1881.54     752 1887.79   755.4 1889.82   792.6 1909.11   812.8 1918.23
#Mann= 6 ,-1 , 0
       0      .1       0     100    .035       0   287.8    .045       0
   308.2    .035       0  689.15     .04       0  749.15     .06       0
#XS Ineff= 2 , 0
                           452.8         1876.17
Permanent Ineff=
       F       F
Bank Sta=287.8,308.2
XS Rating Curve= 0 ,0
Exp/Cntr=0.3,0.1

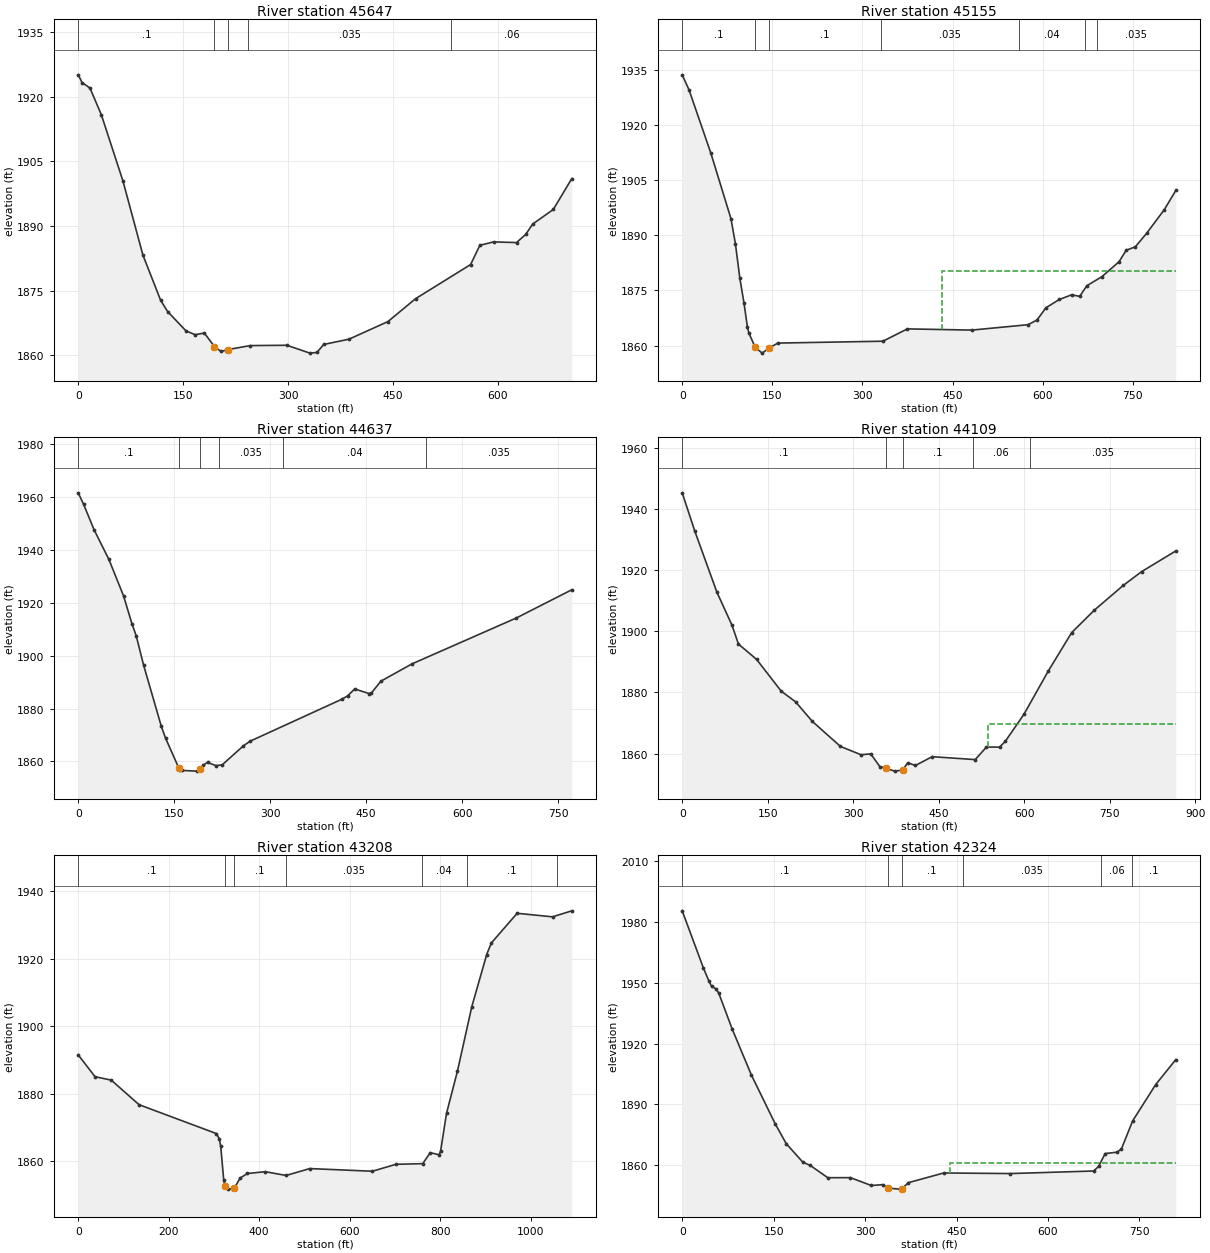
Type RM Length L Ch R = 1 ,45647   ,482.3,492.3,495.6
XS GIS Cut Line= 3
     2061618.166      182448.692     2061646.378      182537.667
     2061663.739      183149.646
#Sta/Elev= 30
       0  1925.1     5.5 1923.32    16.8 1922.03    33.1 1915.82      64 1900.45
    92.5 1883.28   117.9 1872.78   127.8  1870.2     154 1865.72   167.1 1864.83
   180.3 1865.21   194.81862.061   204.1 1860.93   214.51861.386   245.9  1862.3
   298.4 1862.37   331.2 1860.55   341.3 1860.71   350.9 1862.56     387 1863.78
   442.8 1867.87   482.2 1873.17     561  1881.1   574.1 1885.55   593.8 1886.35
   626.6 1886.19   639.8  1888.1   649.6 1890.47   679.2 1893.88   705.6 1901.03
#Mann= 5 ,-1 , 0
       0      .1       0   194.8    .045       0   214.5      .1       0
  243.34    .035       0  533.34     .06       0
Bank Sta=194.8,214.5
XS Rating Curve= 0 ,0
Exp/Cntr=0.3,0.1

Type RM Length L Ch R = 1 ,45155   ,526.6,517.4,508.7
XS GIS Cut Line= 2
     2061331.707      182392.268     2060945.423      183117.094
#Sta/Elev= 30
       0 1933.81    11.4 1929.69    47.6 1912.49    81.1  1894.6    88.5 1887.78
    95.9 1878.34   102.9  1871.5   108.4 1865.15   110.8 1863.46   121.51859.481
   133.1 1857.92     1441859.243   159.1 1860.66     334 1861.17   374.7 1864.53
   481.8  1864.2   575.5 1865.67   590.4 1866.96   605.2 1870.28   627.5 1872.55
   647.9 1873.82   661.3  1873.4   673.4 1876.31   698.2 1878.75   726.8 1882.83
   738.9 1885.98   753.9  1886.9   772.9 1890.61   802.3 1897.07   821.3 1902.27
#Mann= 7 ,-1 , 0
       0      .1       0   121.5    .045       0     144      .1       0
     330    .035       0     560     .04       0     670     .06       0
     690    .035       0
#XS Ineff= 2 , 0
                          431.88         1880.36
Permanent Ineff=
       F       F
Bank Sta=121.5,144
XS Rating Curve= 0 ,0
Exp/Cntr=0.3,0.1

Type RM Length L Ch R = 1 ,44637   ,525.2,528.3,524.6
XS GIS Cut Line= 3
     2060797.853      182166.574     2060789.173      182539.837
     2060602.541        182891.4
#Sta/Elev= 30
       0  1961.7     8.5  1957.3    24.9 1947.66    47.9  1936.5    70.9 1922.65
      84  1912.1    90.6  1907.6   102.2 1896.44   129.9 1873.27   136.5 1868.82
   157.2 1857.49   159.5 1856.73   162.8 1856.58   185.7 1856.32     1901856.937
   195.6 1858.65   202.1 1859.63   215.3 1858.39   225.1 1858.72   257.9 1865.85
   268.6 1867.65     412 1883.54     421 1884.82   432.1 1887.43   454.4 1885.71
   458.1 1885.87     473 1890.37   521.3 1896.89   684.8 1914.32   771.4    1925
#Mann= 6 ,-1 , 0
       0      .1       0   157.2    .045       0     190      .1       0
     220    .035       0     320     .04       0  543.36    .035       0
Bank Sta=157.2,190
XS Rating Curve= 0 ,0
Exp/Cntr=0.3,0.1

Type RM Length L Ch R = 1 ,44109   ,885.6,901.2,897.6
XS GIS Cut Line= 4
     2060413.739      182023.344      2060283.53      182212.146
     2060303.062      182637.494     2060376.846      182834.976
#Sta/Elev= 30
       0 1945.26      22 1932.79    60.8 1912.81    87.2 1902.05    98.7 1895.82
   130.6 1890.79   173.8  1880.4   198.9 1876.95   228.2 1870.56   277.6 1862.36
   313.8 1859.63   330.8 1859.92   346.7 1855.77   357.1 1855.19   372.9 1854.28
   386.61854.636   395.9 1857.04     409 1856.12   438.6    1859   514.1 1858.05
   533.8 1862.15   556.8 1862.13   566.7 1863.98   599.5 1872.83   642.2 1886.97
   683.4 1899.58   723.2 1906.92   773.7 1914.97   805.9 1919.48     866 1926.26
#Mann= 5 ,-1 , 0
       0      .1       0   357.1    .045       0   386.6      .1       0
  509.35     .06       0  609.35    .035       0
#XS Ineff= 2 , 0
                          536.36         1869.73
Permanent Ineff=
       F       F
Bank Sta=357.1,386.6
XS Rating Curve= 0 ,0
Exp/Cntr=0.3,0.1

Type RM Length L Ch R = 1 ,43208   ,895.3,883.6,871.9
XS GIS Cut Line= 4
     2059922.745      181753.871     2059819.121      181990.792
     2059836.482      182628.813     2059793.079      182817.615
#Sta/Elev= 30
       0 1891.56    37.2  1885.1      73 1884.08   134.5  1876.8   305.1 1868.26
   311.7 1866.72   314.9 1864.42   321.5 1854.52     3241852.755   331.4 1851.79
   345.11852.043   357.6 1855.07     374 1856.42   413.4 1856.95   459.4 1855.84
   511.7 1857.88     650 1857.09   702.2 1859.15   761.3 1859.34   777.7 1862.58
   797.4 1861.98   800.7 1863.03   813.8 1874.25     838 1886.78   869.6 1905.81
   902.6  1921.3   912.8 1924.72   969.9 1933.51    1048 1932.46  1090.6 1934.24
#Mann= 7 ,-1 , 0
       0      .1       0     324    .045       0   345.1      .1       0
  458.59    .035       0  758.59     .04       0  858.59      .1       0
 1056.85    .035       0
Bank Sta=324,345.1
XS Rating Curve= 0 ,0
Exp/Cntr=0.3,0.1

Type RM Length L Ch R = 1 ,42324   ,715.7,717.6,719.6
XS GIS Cut Line= 3
     2059021.703      182287.725      2059495.77      182785.063
     2059602.107      182845.827
#Sta/Elev= 30
       0  1985.6    34.7 1957.44    43.8 1950.93    48.3 1948.25    55.4  1947.1
    60.1 1944.86    81.8 1927.38   113.4  1904.6   152.6 1880.41   170.7 1870.65
   197.9  1861.5   210.2  1859.9   238.7 1853.86   275.9 1853.89   310.1 1850.02
   329.2 1850.43     3371848.728   356.6 1848.22   359.9 1848.35     371 1851.41
     429  1856.2   538.1  1855.9     675 1857.17   682.9 1859.42   693.8 1865.78
     713 1866.45   720.3 1867.97   738.9 1881.94   776.7 1899.86   809.6 1912.16
#Mann= 6 ,-1 , 0
       0      .1       0     337    .045       0   359.9      .1       0
     460    .035       0  687.08     .06       0  737.08      .1       0
#XS Ineff= 2 , 0
                          438.66         1861.08
Permanent Ineff=
       F       F
Bank Sta=337,359.9
XS Rating Curve= 0 ,0
Exp/Cntr=0.3,0.1

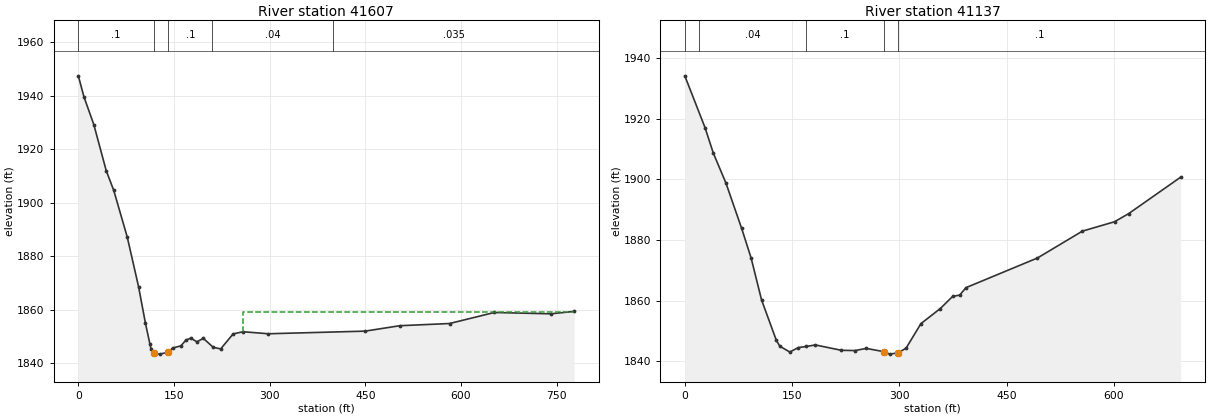
Type RM Length L Ch R = 1 ,41607   ,445,469.4,485.5
XS GIS Cut Line= 2
     2058628.474      182610.642     2059048.721      183264.664
#Sta/Elev= 30
       0 1947.39     8.7 1939.62    24.3 1929.15    43.8 1911.88    55.5 1904.59
    76.7 1887.13    94.5 1868.52   105.2 1854.95   112.3 1847.09     114 1845.36
   118.11843.674   127.9 1843.38     1411844.142   147.9 1845.67   160.8 1846.47
   168.6  1848.6   176.4 1849.36   185.9 1847.98   195.9 1849.29   211.5 1845.93
   223.2 1845.33   242.7 1850.93   258.3 1851.75   297.8 1850.99   449.5 1851.97
     504    1854     582 1854.82   652.2 1858.94   740.8 1858.45   777.4 1859.35
#Mann= 5 ,-1 , 0
       0      .1       0   118.1    .045       0     141      .1       0
     210     .04       0     400    .035       0
#XS Ineff= 2 , 0
                          257.72         1858.94
Permanent Ineff=
       F       F
Bank Sta=118.1,141
XS Rating Curve= 0 ,0
Exp/Cntr=0.3,0.1

Type RM Length L Ch R = 1 ,41137   ,479.4,477.3,459.6
XS GIS Cut Line= 2
     2058458.444      182637.494     2057996.204      183153.987
#Sta/Elev= 30
       0 1934.16    28.3 1917.06    39.9 1908.65    57.5  1898.8    79.5 1883.81
    92.7 1874.08   107.3 1860.25   127.9 1846.96   132.8 1844.98   146.8 1843.06
   158.4 1844.51     170 1844.91   182.6  1845.4   218.8 1843.63     238 1843.55
   253.6 1844.26   277.91843.201   286.2 1842.37   298.41842.787   309.4 1844.37
   330.1 1852.43   356.9 1857.35   374.4  1861.4   384.3 1861.84     393 1864.29
     493 1874.08   555.7 1882.93   600.7 1886.03   620.4  1888.7   693.1 1900.73
#Mann= 5 ,-1 , 0
       0      .1       0      20     .04       0     170      .1       0
   277.9    .045       0   298.4      .1       0
Bank Sta=277.9,298.4
XS Rating Curve= 0 ,0
Exp/Cntr=0.3,0.1