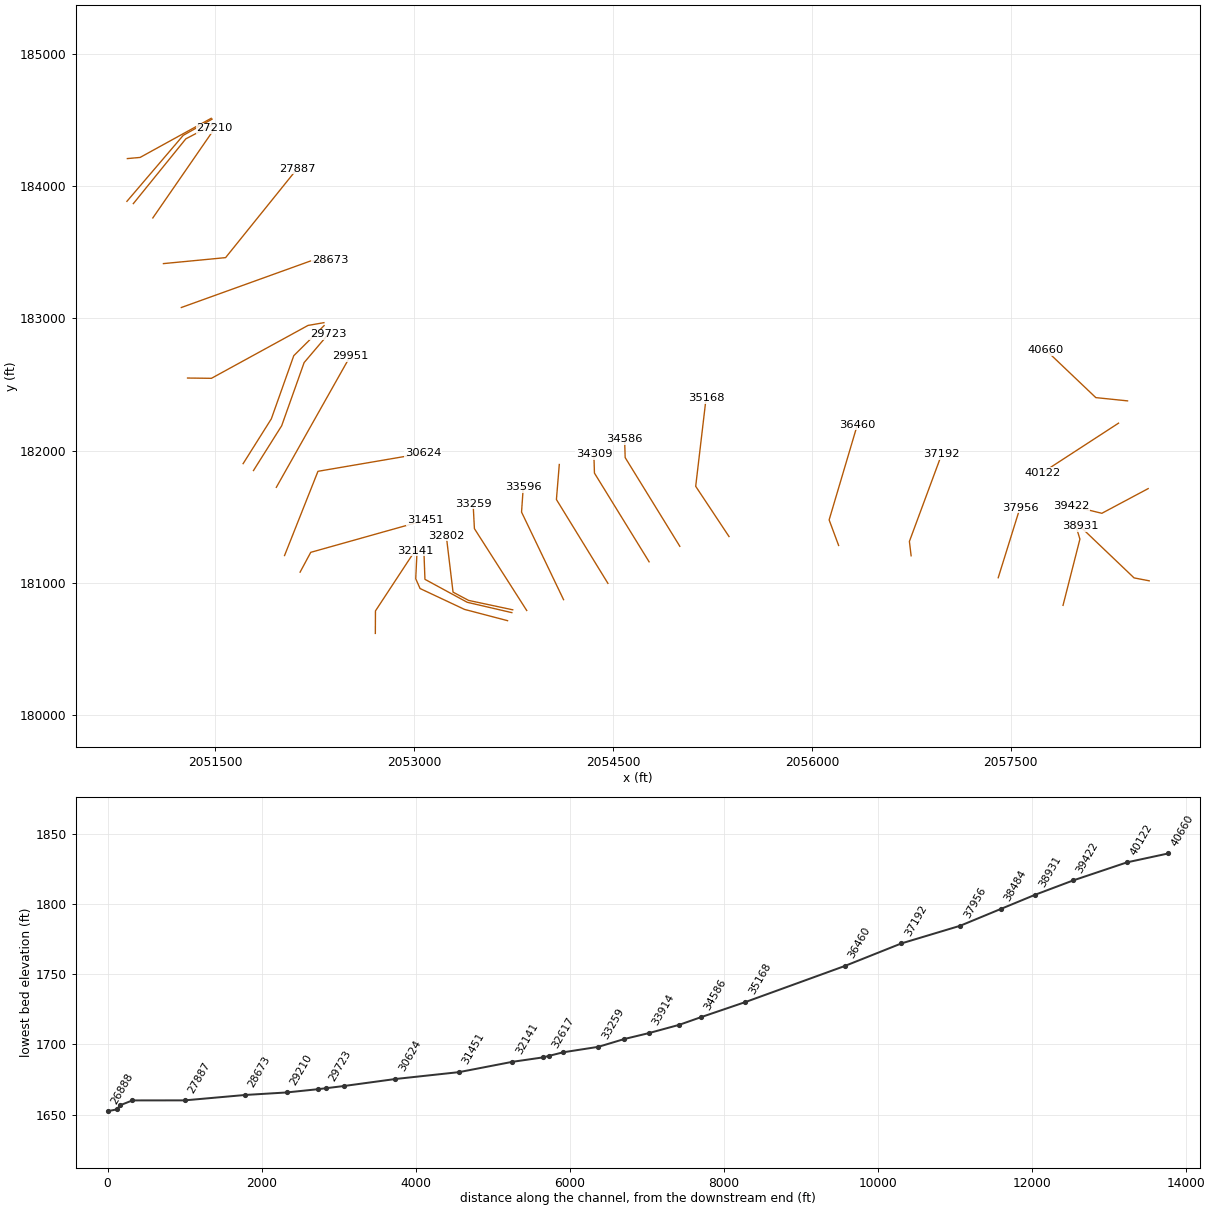
HEC-RAS study HNSCK.prj: HNSCK

--- HNSCK.g01 (geometry) --- (continued)

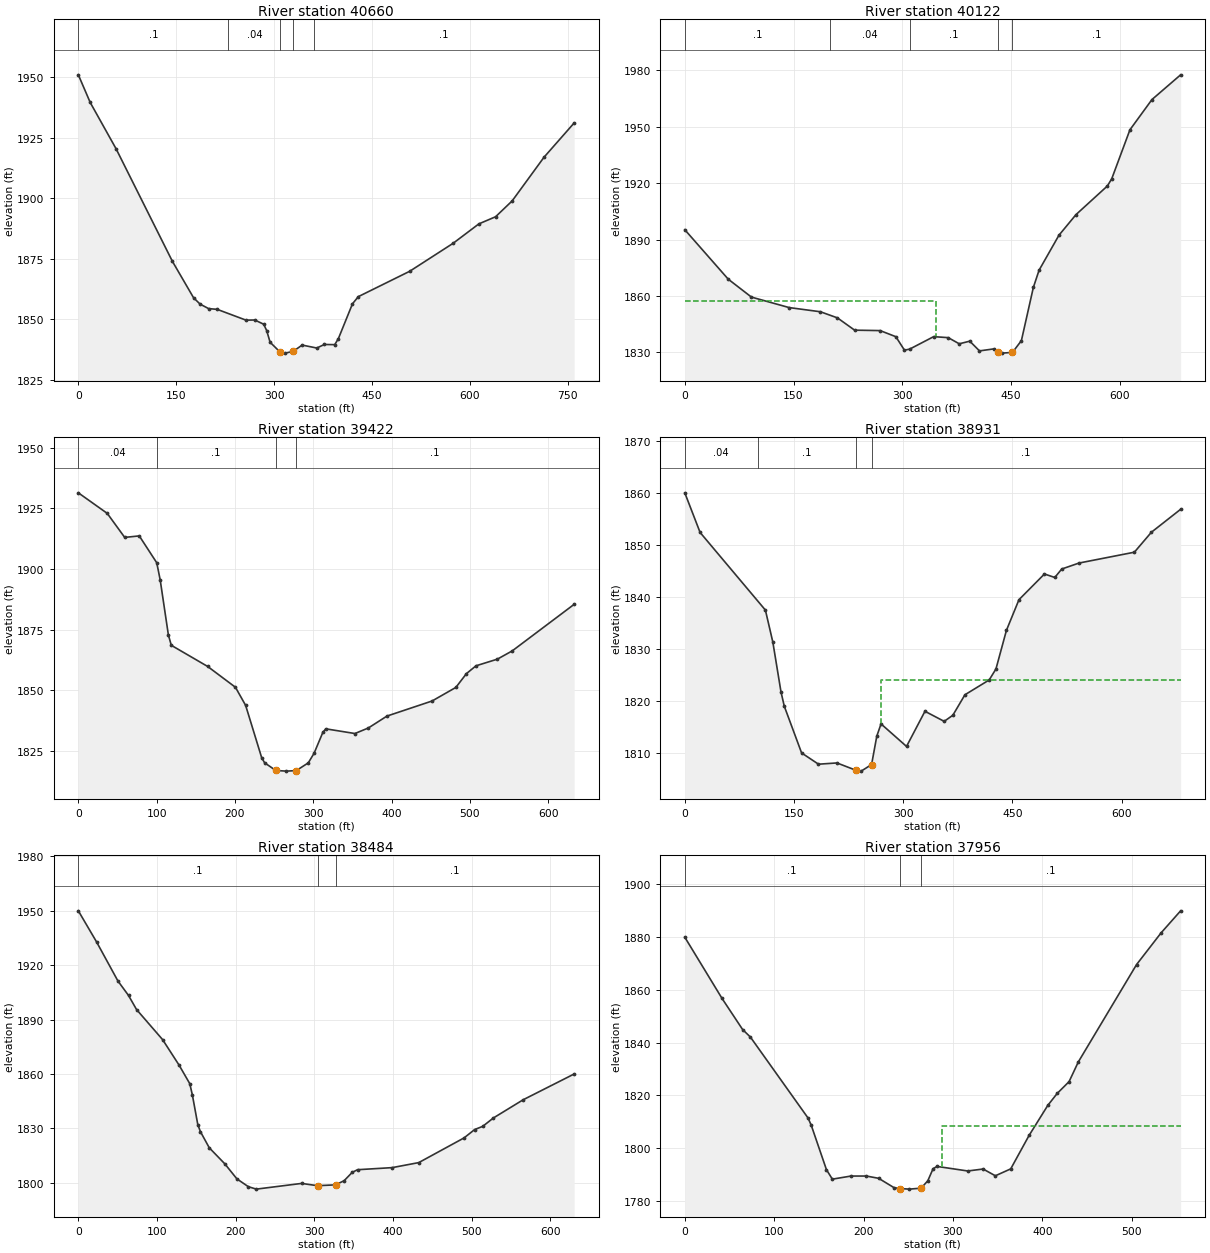
Type RM Length L Ch R = 1 ,40660   ,509.7,538.1,559.2
XS GIS Cut Line= 3
     2058381.078      182376.267     2058141.603      182400.949
     2057766.169      182759.021
#Sta/Elev= 30
       0 1950.92    18.2  1939.5    57.8  1920.4   144.1 1873.92   176.5  1858.9
   186.4 1856.28   199.6  1854.4   212.8 1854.09   256.8 1849.64   270.4 1849.69
     284 1847.95   288.5 1845.36   293.8 1840.51   309.2 1836.43   316.6 1836.02
   328.8  1836.7   342.9 1839.34   365.3 1838.13   376.9 1839.59   392.8 1839.52
   398.4 1842.01     420 1856.39     429 1859.35   507.7 1869.82   574.2 1881.37
   613.6 1889.38   639.2 1892.32   664.6 1898.86   713.4 1916.89   759.6 1931.06
#Mann= 5 ,-1 , 0
       0      .1       0     230     .04       0   309.2    .045       0
   328.8     .04       0  360.74      .1       0
Bank Sta=309.2,328.8
XS Rating Curve= 0 ,0
Exp/Cntr=0.3,0.1

Type RM Length L Ch R = 1 ,40122   ,697.4,699.4,694.5
XS GIS Cut Line= 2
     2058313.044      182207.806     2057740.128      181834.542
#Sta/Elev= 30
       0 1895.27    59.9 1868.98    91.9 1859.45     144 1853.87   187.1 1851.65
   210.5  1848.4   234.2 1841.87   269.4 1841.64   291.1 1838.39   302.9 1831.24
     310 1831.77   343.2 1838.42   363.3 1837.89   378.5 1834.62     393 1836.02
   406.4 1830.85     426  1831.9   431.91830.417   437.7 1829.66   451.91830.042
   464.2  1836.3   480.7 1864.59   488.6 1873.76     516 1892.34   539.5  1903.3
   582.8 1918.53   588.8 1922.36   613.9  1948.4   644.3 1964.49   683.8 1977.62
#Mann= 5 ,-1 , 0
       0      .1       0     200     .04       0     310      .1       0
   431.9    .045       0   451.9      .1       0
#XS Ineff= 2 , 0
          347.03 1857.14
Permanent Ineff=
       F       F
Bank Sta=431.9,451.9
XS Rating Curve= 0 ,0
Exp/Cntr=0.3,0.1

Type RM Length L Ch R = 1 ,39422   ,508.4,491.7,466.4
XS GIS Cut Line= 3
     2058536.569      181713.015     2058187.176      181526.383
     2057957.141      181582.806
#Sta/Elev= 30
       0 1931.39    36.9 1922.93    59.2 1913.03    77.8 1913.65   100.1 1902.59
   104.5 1895.55     115 1872.79   118.7 1868.59   165.1 1859.88   200.6  1851.3
   213.6 1843.84     234 1822.37   237.8 1820.21   252.11817.034   265.7 1816.77
   278.31816.993   293.6 1820.18     301 1824.15   312.1 1832.68   315.9 1834.19
   353.1 1832.26   370.2 1834.53     394 1839.44   451.6 1845.65     482 1851.25
   495.5 1856.94   507.7 1860.15   534.9 1862.88   553.9 1866.28     633 1885.47
#Mann= 4 ,-1 , 0
       0     .04       0     100      .1       0   252.1    .045       0
   278.3      .1       0
Bank Sta=252.1,278.3
XS Rating Curve= 0 ,0
Exp/Cntr=0.3,0.1

Type RM Length L Ch R = 1 ,38931   ,456.2,446.7,429.7
XS GIS Cut Line= 3
     2058544.286      181016.056     2058430.232      181038.101
     2058021.972      181428.322
#Sta/Elev= 30
       0    1860      21  1852.4   110.7  1837.5   120.9 1831.36   132.1 1821.81
   136.6 1819.07   160.4  1810.1   183.6 1807.94     209 1808.18   234.7 1806.79
   242.2 1806.61   256.5 1807.87   263.7 1813.34   269.5 1815.67   304.5 1811.35
   329.8 1818.09   356.2 1816.16   368.1 1817.33   384.7 1821.26     418  1824.1
   427.3 1826.21   441.7 1833.62   458.9  1839.5   493.9 1844.43   508.1 1843.76
   517.6 1845.38   541.4 1846.53   617.4 1848.61   640.7 1852.43   680.9 1856.84
#Mann= 4 ,-1 , 0
       0     .04       0     100      .1       0   234.7    .045       0
   256.5      .1       0
#XS Ineff= 2 , 0
                          269.87         1824.17
Permanent Ineff=
       F       F
Bank Sta=234.7,256.5
XS Rating Curve= 0 ,0
Exp/Cntr=0.3,0.1

Type RM Length L Ch R = 1 ,38484   ,527.1,527.7,525.3
XS GIS Cut Line= 3
     2057894.261      180830.413     2058021.635      181331.138
     2057988.704      181439.947
#Sta/Elev= 30
       0    1950    23.2 1932.84    50.3 1911.32    63.8 1903.32      74 1895.56
   107.2 1878.92   128.2 1864.81   141.7 1854.65     145 1848.42   151.9 1832.05
   155.2 1828.21   166.5 1819.27   186.2 1810.46   201.6 1802.14   216.2 1797.82
   226.3 1796.48   283.9 1799.63   304.11798.373     3271798.832     338 1801.15
   348.2 1805.72     355 1807.19     399 1808.34   432.8 1811.11   490.4 1824.73
   503.9 1829.35   514.1 1831.09   527.7 1835.73   565.5 1845.76   630.4    1860
#Mann= 3 ,-1 , 0
       0      .1       0   304.1    .045       0     327      .1       0
Bank Sta=304.1,327
XS Rating Curve= 0 ,0
Exp/Cntr=0.3,0.1

Type RM Length L Ch R = 1 ,37956   ,763.9,764.2,761.9
XS GIS Cut Line= 2
     2057405.416      181039.443     2057570.112      181569.254
#Sta/Elev= 30
       0    1880    41.7 1856.77    64.7    1845    73.4 1842.15   137.9 1811.46
   141.5  1808.7   158.5 1791.88   165.1 1788.28     186 1789.46   203.2 1789.46
   216.9  1788.6   234.1 1785.06   240.31784.733   251.3  1784.5   264.41784.868
   271.9 1787.66   277.8 1792.23   282.2 1793.11   316.6 1791.38   333.8 1792.12
   347.5 1789.56   364.7 1792.18   385.2 1804.84   406.2 1816.26   416.7 1820.78
     430 1825.26   440.3  1832.7   505.5 1869.63     533 1881.67   554.8    1890
#Mann= 3 ,-1 , 0
       0      .1       0   240.3    .045       0   264.4      .1       0
#XS Ineff= 2 , 0
                          287.28         1808.57
Permanent Ineff=
       F       F
Bank Sta=240.3,264.4
XS Rating Curve= 0 ,0
Exp/Cntr=0.3,0.1

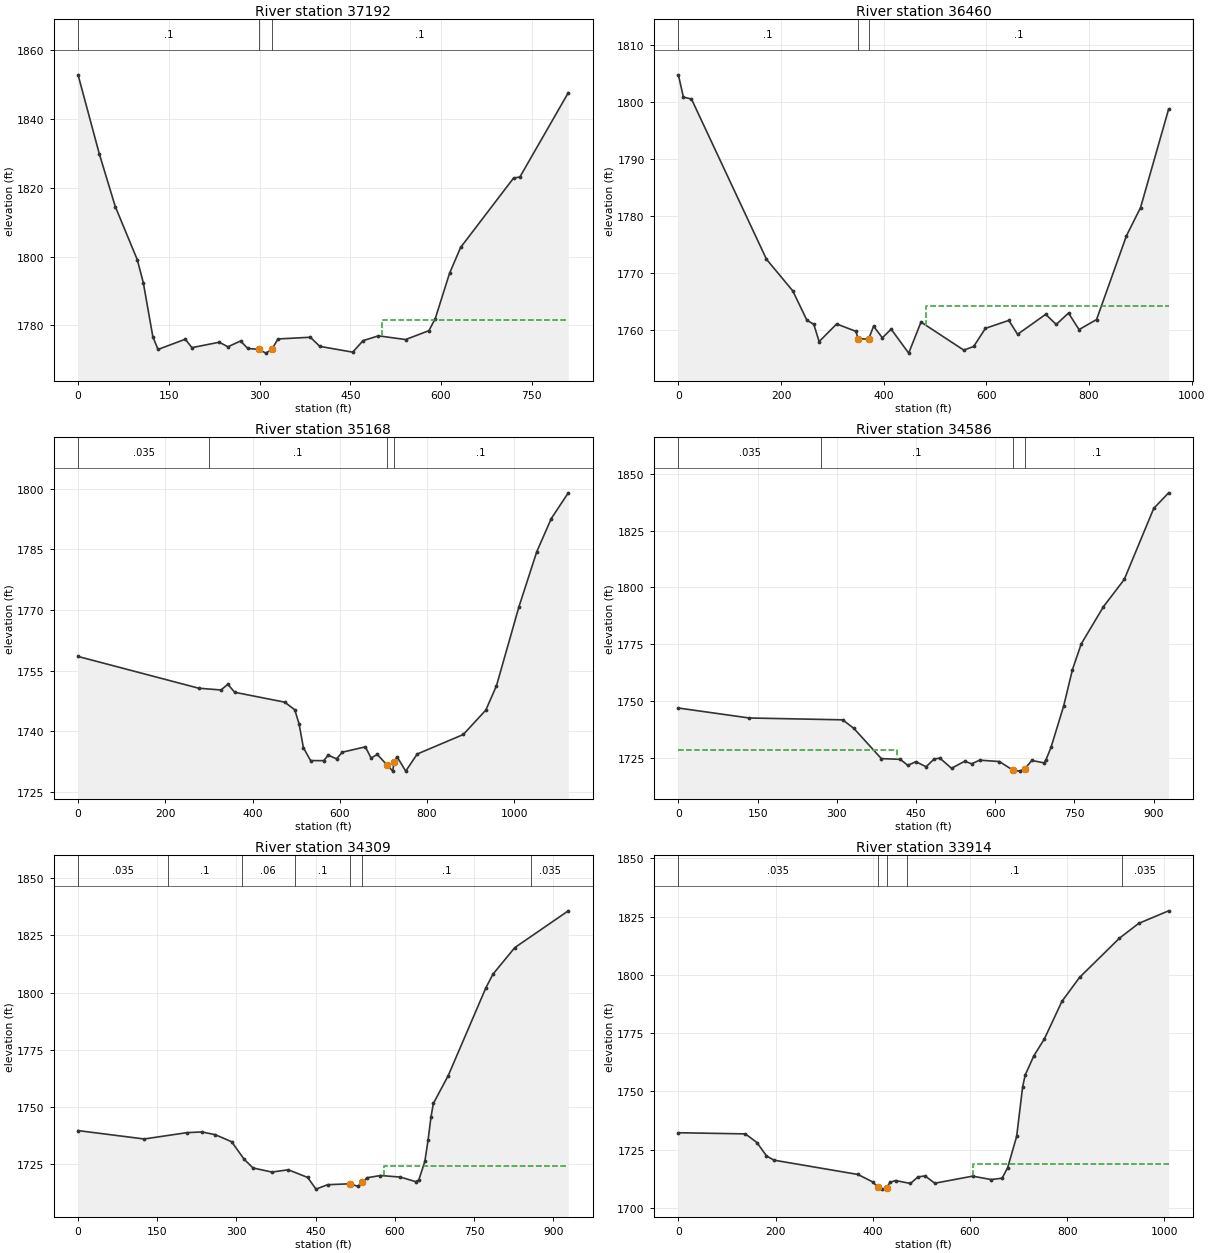
Type RM Length L Ch R = 1 ,37192   ,729.5,732,731.4
XS GIS Cut Line= 3
     2056748.374      181205.202     2056735.353      181313.709
     2056978.409      181971.261
#Sta/Elev= 30
       0 1852.83    35.1 1829.87    61.5 1814.54    97.9 1799.07   107.8 1792.43
   123.7 1776.62   132.2 1772.98   177.3 1775.96   188.2  1773.5   233.5 1775.09
   247.6 1773.75   268.6 1775.43   280.5 1773.28   298.41772.998   310.6 1771.91
   320.21773.011   330.5 1776.03     384 1776.53   399.5 1773.88     454 1772.19
     471 1775.53   496.5 1776.94   541.4 1775.86   579.9 1778.44   590.4 1781.95
     614 1795.12   632.4 1802.66   719.8 1822.81   730.3 1823.13   810.3 1847.63
#Mann= 3 ,-1 , 0
       0      .1       0   298.4    .045       0   320.2      .1       0
#XS Ineff= 2 , 0
                          502.47         1781.42
Permanent Ineff=
       F       F
Bank Sta=298.4,320.2
XS Rating Curve= 0 ,0
Exp/Cntr=0.3,0.1

Type RM Length L Ch R = 1 ,36460   ,1284,1292.5,1291.7
XS GIS Cut Line= 3
     2056201.499      181283.327     2056129.885      181476.469
     2056342.558      182194.785
#Sta/Elev= 30
       0 1804.81     9.8 1800.89    25.5 1800.56   171.6  1772.4   222.9 1766.83
   250.3 1761.69   263.9 1760.95   274.2 1757.92   308.4 1761.02   346.1 1759.71
   349.91758.443   370.51758.342   380.3 1760.62   397.4 1758.58   414.5 1760.11
   448.7 1755.89   472.7 1761.35     556 1756.42   575.3 1757.06   598.2 1760.25
   643.7 1761.64   660.9  1759.2   715.6 1762.71   736.1 1760.93   760.1 1762.93
   780.6 1760.03   814.7 1761.79     873 1776.53   900.4 1781.47   955.1 1798.78
#Mann= 3 ,-1 , 0
       0      .1       0   349.9    .045       0   370.5      .1       0
#XS Ineff= 2 , 0
                          483.05         1764.21
Permanent Ineff=
       F       F
Bank Sta=349.9,370.5
XS Rating Curve= 0 ,0
Exp/Cntr=0.3,0.1

Type RM Length L Ch R = 1 ,35168   ,568.5,581.1,586.8
XS GIS Cut Line= 3
     2055374.676      181350.601     2055123.266      181730.433
     2055201.391      182394.496
#Sta/Elev= 30
       0 1758.52   276.6 1750.67   327.7 1750.23   343.5 1751.63   359.2 1749.66
   473.8 1747.22   496.9 1745.33   506.8 1741.85   516.7 1735.96   533.2 1732.77
     563 1732.75   573.7  1734.1   592.7  1733.2   605.9 1734.84   658.8 1736.17
     672 1733.38     686  1734.3   707.91731.739   721.5 1730.18   724.51732.323
   731.4 1733.73   751.3 1730.16   777.7 1734.39   883.4 1739.22     935 1745.26
   959.4 1751.27  1011.1 1770.87  1051.9 1784.45    1085 1792.62  1124.1 1798.99
#Mann= 4 ,-1 , 0
       0    .035       0     300      .1       0   707.9    .045       0
   724.5      .1       0
Bank Sta=707.9,724.5
XS Rating Curve= 0 ,0
Exp/Cntr=0.3,0.1

Type RM Length L Ch R = 1 ,34586   ,278.7,276.9,276.8
XS GIS Cut Line= 3
     2055003.582      181276.817     2054591.256       181947.39
     2054586.916      182088.449
#Sta/Elev= 30
       0 1747.04     134 1742.66   311.2 1741.85   332.4 1738.07   384.3 1724.81
   420.1  1724.5   434.4 1721.86   449.8 1723.46   469.1 1721.23   484.5 1724.68
   495.2 1725.02   517.2 1720.56   542.2 1723.66   555.3 1722.53   570.4 1724.12
   607.8 1723.53     633 1719.81     646 1719.31   656.51720.459   669.3 1723.99
   692.5 1722.94   696.1 1724.29   705.6 1729.75   729.5 1747.86   746.1 1763.85
   762.8  1775.2   804.9 1791.56   844.3 1803.54   900.1 1834.74   928.3 1841.59
#Mann= 4 ,-1 , 0
       0    .035       0     270      .1       0     633    .045       0
   656.5      .1       0
#XS Ineff= 2 , 0
          414.21 1728.63
Permanent Ineff=
       F       F
Bank Sta=633,656.5
XS Rating Curve= 0 ,0
Exp/Cntr=0.3,0.1

Type RM Length L Ch R = 1 ,34309   ,389.2,395.7,393.7
XS GIS Cut Line= 3
     2054771.812      181159.629     2054359.485      181830.202
     2054355.145      181971.261
#Sta/Elev= 30
       0 1739.58   125.2 1735.91   206.1 1738.68   234.4 1738.99   259.8 1737.79
   290.8 1734.71   314.6    1727   331.3 1723.22   367.1 1721.43   398.1 1722.43
   434.8 1719.07   450.6 1713.96   472.4 1715.89     5151716.305   529.6  1715.2
   538.5 1717.03   547.6 1718.95   572.6 1719.92   610.5 1719.23     639 1717.25
   645.2 1717.97   656.7 1726.11   662.9 1735.67   668.3 1745.54   672.8 1751.46
     701 1763.67   772.3  1802.1   785.6 1808.04     827 1819.67   928.3 1835.77
#Mann= 7 ,-1 , 0
       0    .035       0     170      .1       0     310     .06       0
     410      .1       0     515    .045       0   538.5      .1       0
   857.2    .035       0
#XS Ineff= 2 , 0
                          579.46         1724.25
Permanent Ineff=
       F       F
Bank Sta=515,538.5
XS Rating Curve= 0 ,0
Exp/Cntr=0.3,0.1

Type RM Length L Ch R = 1 ,33914   ,318.6,317.5,316.1
XS GIS Cut Line= 3
     2054461.048      180996.869     2054072.593      181630.549
     2054094.294      181895.306
#Sta/Elev= 30
       0 1732.24   137.9 1731.74   161.8 1728.01   181.3  1722.3   196.7 1720.47
   369.4 1714.34   400.4 1711.08   410.11708.885   418.7 1708.04   428.91708.556
   435.3 1710.94   446.9 1711.72   477.6 1710.47     493 1713.28   507.7 1713.72
   527.7 1710.57   605.5 1713.61   643.7 1712.15   666.2 1712.73   677.7 1717.27
   696.2 1730.71   708.5 1751.96   713.7    1757   731.6 1765.27   753.1 1772.46
   789.3 1788.59   825.5 1798.87   907.8 1815.74   947.3 1822.07  1008.9 1827.46
#Mann= 5 ,-1 , 0
       0    .035       0   410.1    .045       0   428.9    .035       0
     470      .1       0  913.27    .035       0
#XS Ineff= 2 , 0
                          606.03         1718.87
Permanent Ineff=
       F       F
Bank Sta=410.1,428.9
XS Rating Curve= 0 ,0
Exp/Cntr=0.3,0.1

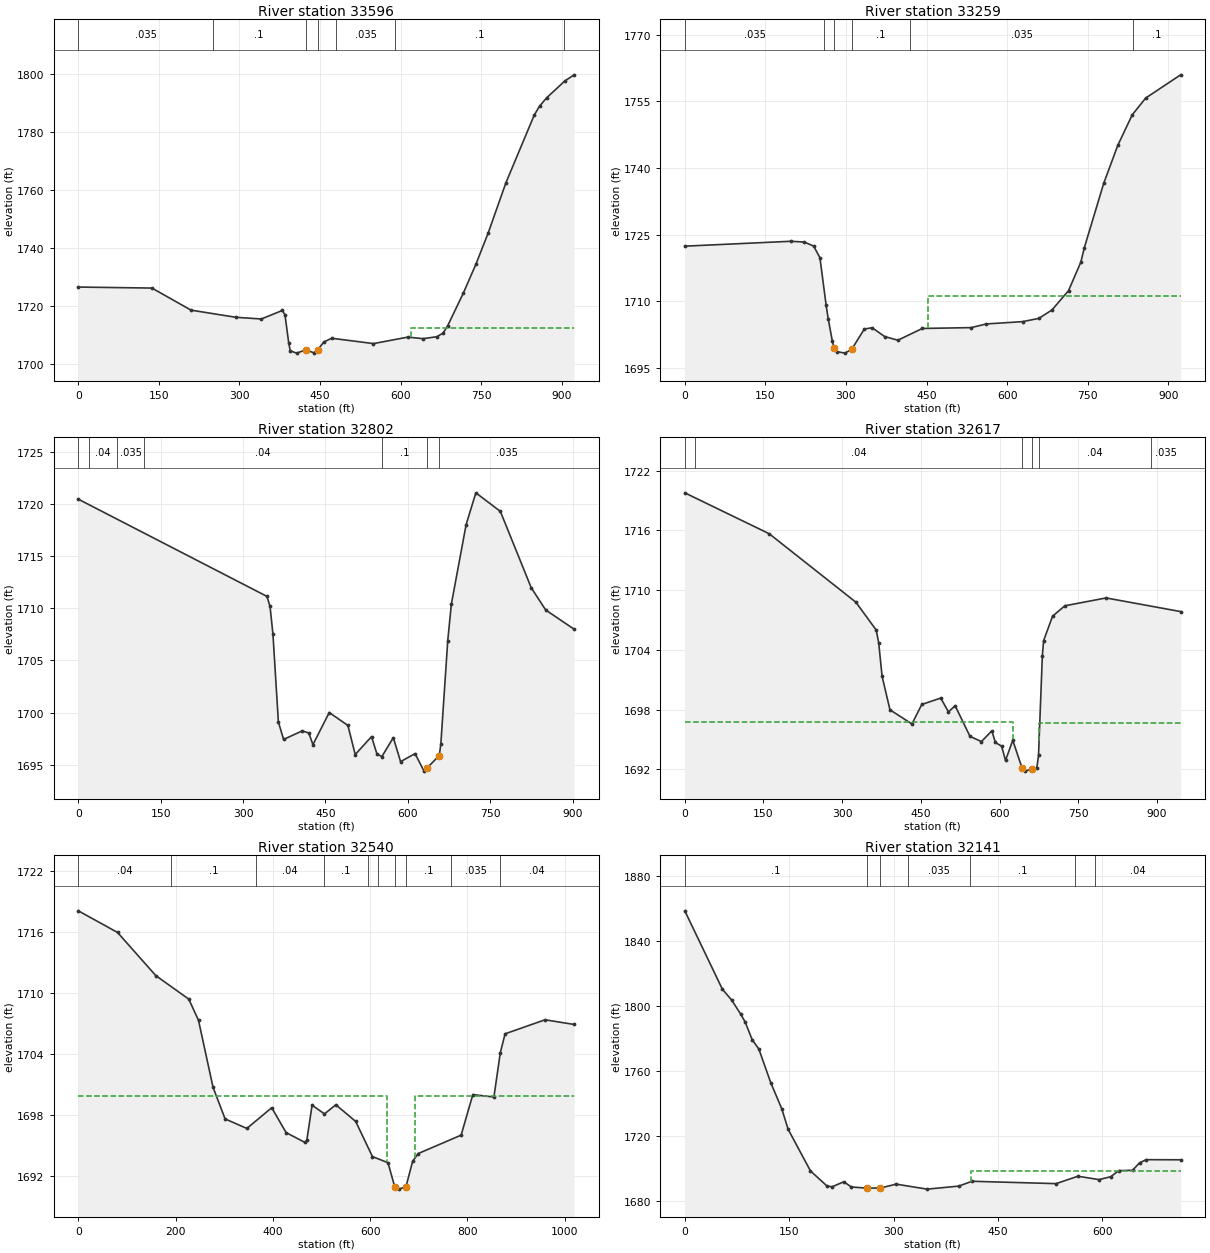
Type RM Length L Ch R = 1 ,33596   ,337.3,336.9,339.5
XS GIS Cut Line= 3
     2054126.412      180873.605     2053809.572      181535.497
     2053822.593      181724.299
#Sta/Elev= 30
       0 1726.63   137.1 1726.28   209.8 1718.67   293.5  1716.2   340.8 1715.62
   379.8 1718.56   384.7 1717.08   391.7 1707.37   394.5 1704.67   406.3 1703.85
   423.41704.972   438.8 1703.96   445.51704.962   457.2 1707.71   471.7 1708.98
   549.5 1707.14   613.5 1709.37   641.8 1708.84   667.6 1709.51   679.1 1710.77
   687.3 1713.16   716.8 1724.55   740.2 1734.51   763.2 1745.35   796.1  1762.6
   848.7 1785.89   858.6 1788.98   871.8 1791.86   905.5 1797.65   923.1  1799.8
#Mann= 7 ,-1 , 0
       0    .035       0     250      .1       0   423.4    .045       0
   445.5      .1       0     480    .035       0     590      .1       0
  903.82    .035       0
#XS Ineff= 2 , 0
                          619.96         1712.62
Permanent Ineff=
       F       F
Bank Sta=423.4,445.5
XS Rating Curve= 0 ,0
Exp/Cntr=0.3,0.1

Type RM Length L Ch R = 1 ,33259   ,472.7,457.6,451.3
XS GIS Cut Line= 3
     2053848.536      180791.704     2053454.018      181410.449
     2053444.123       181599.44
#Sta/Elev= 30
       0 1722.39   197.1 1723.49   222.5 1723.32   239.9  1722.4   251.6 1719.78
   263.2 1709.02   267.1 1705.94   274.6 1701.04   278.51699.325   282.7 1698.63
   298.3 1698.28   310.91699.165   334.2 1703.71   348.8 1704.01     372 1702.02
   396.7 1701.19   442.2 1703.84   533.1 1704.03   561.5 1704.86     629 1705.38
   659.1 1706.11   683.5    1708   714.4 1712.36   737.3 1718.79   743.9 1722.07
   779.9 1736.55   806.3 1745.17   833.1 1752.01   858.1 1755.78   923.1 1761.01
#Mann= 6 ,-1 , 0
       0    .035       0     260      .1       0   278.5    .045       0
   310.9      .1       0     420    .035       0  833.82      .1       0
#XS Ineff= 2 , 0
                          453.54         1711.06
Permanent Ineff=
       F       F
Bank Sta=278.5,310.9
XS Rating Curve= 0 ,0
Exp/Cntr=0.3,0.1

Type RM Length L Ch R = 1 ,32802   ,167.6,185.3,196.8
XS GIS Cut Line= 4
2053742.91286569180796.9224261832053409.77168689180868.028373353
2053292.81378881180930.4059189932053241.57509061181357.023775779
#Sta/Elev= 30
       0 1720.46   343.4 1711.14   349.1 1710.18   354.4 1707.51   364.3 1699.09
   373.8 1697.42   407.7 1698.24   419.7 1698.04   427.2 1696.92   456.9    1700
   490.9 1698.76   504.2 1695.97   533.9 1697.69   543.8 1696.02   552.8 1695.78
   573.6 1697.59   586.8 1695.29   613.2 1696.06   629.5 1694.38   635.21694.694
   657.21695.873   660.1 1696.95   672.7 1706.89   679.3  1710.4   706.2 1718.03
   723.9 1721.07   768.5 1719.29   824.7 1711.97   851.1 1709.83   902.9 1707.99
#Mann= 7 ,-1 , 0
       0    .035       0      20     .04       0      70    .035       0
     120     .04       0   553.2      .1       0   635.2    .045       0
   657.2    .035       0
Bank Sta=635.2,657.2
XS Rating Curve= 0 ,0
Exp/Cntr(USF)=0,0
Exp/Cntr=0.5,0.3

Type RM Length L Ch R = 1 ,32617   ,75.6,76.4,78.1
XS GIS Cut Line= 4
     2053736.221      180775.515      2053399.85       180853.64
     2053080.839      181027.251     2053072.159      181263.796
#Sta/Elev= 30
       0 1719.78   160.9 1715.67   326.2 1708.79   364.9 1705.99   369.6 1704.72
   376.1 1701.35   391.1 1697.98     433 1696.56   451.8 1698.52   487.9 1699.16
   502.6 1697.77   515.4 1698.39   543.7 1695.31   565.5 1694.79   585.3 1695.87
   592.1  1694.7     604 1694.32   611.4 1692.89   625.2 1694.92   643.1  1692.1
   647.7 1691.82   662.11692.028   671.2 1692.18   674.3  1693.4   681.6  1703.4
     684 1704.93   701.1 1707.39   724.5 1708.43   803.1 1709.22   945.2 1707.85
#Mann= 6 ,-1 , 0
       0    .035       0      20     .04       0   643.1    .045       0
   662.1      .1       0  675.32     .04       0  888.52    .035       0
#XS Ineff= 2 , 0
          625.25 1696.75  675.35          1696.7
Permanent Ineff=
       F       F
Bank Sta=643.1,662.1
XS Rating Curve= 0 ,0
Exp/Cntr=0.5,0.3

Type RM Length L Ch R = 1 ,32540   ,424.9,398.9,371.9
XS GIS Cut Line= 5
     2053703.995      180714.808     2053379.306      180799.909
     2053043.947      180957.806     2053011.395      181031.591
     2053022.246      181263.796
#Sta/Elev= 30
       0 1718.13    80.7    1716   159.2 1711.76   227.1 1709.44   247.1 1707.35
   276.9 1700.78   301.7 1697.66   346.5 1696.72   397.6 1698.76   427.2 1696.31
   466.1 1695.34   469.8 1695.57   480.6 1699.01   506.1 1698.15   529.4 1699.05
   570.2 1697.41   604.7 1693.95   636.6 1693.35   650.61690.965   658.3 1690.75
   673.51690.974   687.3 1693.48   698.8 1694.25     787 1696.06   811.1 1700.05
   854.4 1699.81   867.6 1704.18   877.4 1706.03   959.5 1707.41  1019.4 1706.95
#Mann= 10 ,-1 , 0
       0     .04       0     190      .1       0  365.66     .04       0
  505.66      .1       0  595.66     .04       0  615.66      .1       0
   650.6    .045       0   673.5      .1       0  766.33    .035       0
  866.97     .04       0
#XS Ineff= 2 , 0
          635.15 1699.96  692.12         1699.89
Permanent Ineff=
       F       F
Bank Sta=650.6,673.5
XS Rating Curve= 0 ,0
Exp/Cntr=0.5,0.3

Type RM Length L Ch R = 1 ,32141   ,701.9,690.2,680.1
XS GIS Cut Line= 3
     2052706.599      180618.454     2052707.575      180788.535
     2053004.885      181242.094
#Sta/Elev= 30
       0 1858.55      54 1810.38    67.1 1803.87    80.5 1794.99    86.8 1790.21
    96.7 1779.49   106.5 1773.55   123.4 1753.07   139.3 1736.97   148.5 1724.31
   180.6 1698.74   204.2 1689.54   211.7 1689.01   228.5 1692.12   239.2 1688.91
   261.61688.186     2811688.267   303.7 1690.64   348.2 1687.58   393.7 1689.44
   412.7 1692.41   533.5 1690.95   564.8  1695.5   595.1 1693.43   611.9 1695.21
   623.6 1698.94   643.3 1699.14   653.4 1703.75   662.9 1705.68   712.4 1705.61
#Mann= 7 ,-1 , 0
       0      .1       0   261.6    .045       0     281      .1       0
  320.08    .035       0  410.08      .1       0  560.08    .035       0
  590.08     .04       0
#XS Ineff= 2 , 0
                          411.53         1698.88
Permanent Ineff=
       F       F
Bank Sta=261.6,281
XS Rating Curve= 0 ,0
Exp/Cntr=0.3,0.1

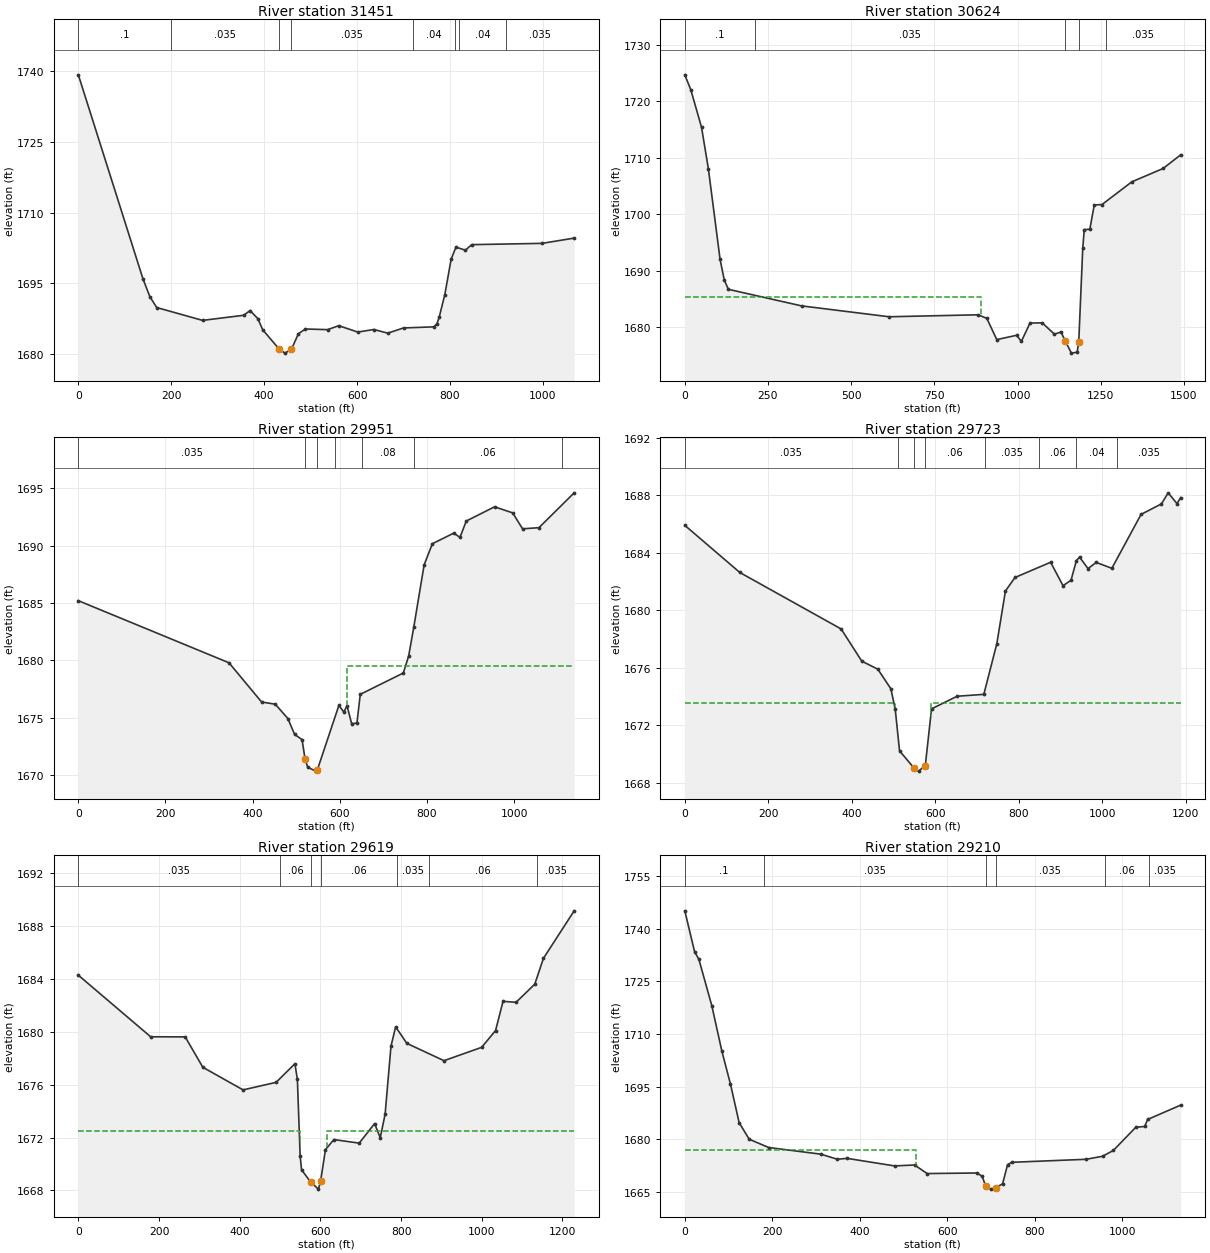
Type RM Length L Ch R = 1 ,31451   ,817.4,827,826.6
XS GIS Cut Line= 3
     2052138.999      181081.504     2052219.294      181231.244
      2053083.01      181474.299
#Sta/Elev= 30
       0 1739.16   138.9 1696.04   153.8 1692.24   168.7 1689.91   267.4 1687.19
     356 1688.27   369.6 1689.27   386.6 1687.53   396.9 1685.19   431.91681.161
   444.6 1680.26   458.71681.086   473.8 1684.38   488.9 1685.37   536.6 1685.23
   560.5 1686.07   601.4 1684.72   636.1 1685.26   666.1 1684.48   699.9 1685.59
     765 1685.82   771.8 1686.46   776.6 1687.83   788.8 1692.64   802.4 1700.12
   812.7 1702.69   833.1 1702.05   846.8 1703.22   997.8 1703.49  1067.2  1704.6
#Mann= 8 ,-1 , 0
       0      .1       0  199.91    .035       0   431.9    .045       0
   458.7    .035       0  719.91     .04       0  809.91    .035       0
  819.91     .04       0  919.91    .035       0
Bank Sta=431.9,458.7
XS Rating Curve= 0 ,0
Exp/Cntr=0.3,0.1

Type RM Length L Ch R = 1 ,30624   ,636.4,673,684.9
XS GIS Cut Line= 3
     2052021.703      181206.9962052273.79249714  181843.7800421
2053067.59847921181979.846700363
#Sta/Elev= 30
       0 1724.73    17.9 1722.11    50.3 1715.42    70.8 1708.09   106.1 1691.97
   118.5 1688.38   130.8 1686.68   351.1 1683.74     614 1681.81   881.2 1682.16
   907.8 1681.53   937.7 1677.76   997.7 1678.53  1011.5 1677.43  1037.6  1680.7
  1074.3 1680.73  1110.9 1678.73  1130.8  1679.1  1144.2 1677.43  1162.1 1675.36
  1179.2 1675.52  1184.1 1677.33  1196.2 1694.03  1200.7 1697.27  1217.4 1697.33
  1230.7 1701.64    1254 1701.72  1343.7 1705.75  1437.8 1708.12  1490.3 1710.53
#Mann= 5 ,-1 , 0
       0      .1       0     210    .035       0  1144.2    .045       0
  1184.1     .04       0 1264.87    .035       0
#XS Ineff= 2 , 0
          889.49 1685.39
Permanent Ineff=
       F       F
Bank Sta=1144.2,1184.1
XS Rating Curve= 0 ,0
Exp/Cntr=0.3,0.1

Type RM Length L Ch R = 1 ,29951   ,225,228.5,230.4
XS GIS Cut Line= 2
2051959.69598677181722.7255502592052517.47144364182714.645821493
#Sta/Elev= 30
       0  1685.2   345.9 1679.78   420.6 1676.36     452 1676.17   480.9 1674.92
   496.4 1673.53   513.5 1673.08   520.2 1671.43   526.5 1670.66   545.3 1670.33
   548.11670.388     598 1676.06   609.3 1675.49   616.8 1676.02   627.3 1674.47
   639.4 1674.52   647.1 1677.03   745.9 1678.89   758.2 1680.38     770 1682.91
   793.7 1688.33   812.6 1690.17   861.4 1691.09     876 1690.73   890.4 1692.15
   955.3 1693.39     997 1692.86  1019.6 1691.47  1057.2 1691.57    1138 1694.61
#Mann= 7 ,-1 , 0
       0    .035       0   520.2    .045       0   548.1    .035       0
     590     .06       0     650     .08       0     770     .06       0
    1110    .035       0
#XS Ineff= 2 , 0
                          616.27         1679.54
Permanent Ineff=
       F       F
Bank Sta=520.2,548.1
XS Rating Curve= 0 ,0
Exp/Cntr(USF)=0,0
Exp/Cntr=0.5,0.3

Type RM Length L Ch R = 1 ,29723   ,103.5,103.5,103.1
XS GIS Cut Line= 4
     2051787.437      181849.733      2052000.11      182188.275
     2052169.381      182665.705     2052351.673      182880.549
#Sta/Elev= 30
       0  1685.9   131.8 1682.62   374.6 1678.69   424.1 1676.45   462.6 1675.89
   493.7 1674.53   504.2 1673.12   514.6 1670.21   550.11668.988   560.1  1668.8
   576.31669.187   591.2 1673.13   652.6 1674.01   716.5 1674.14   747.7 1677.67
   768.3 1681.33   791.2 1682.27   876.6 1683.33   906.3  1681.7   925.5 1682.08
   938.4 1683.45   945.9 1683.69   966.2 1682.89   985.8 1683.32  1023.3 1682.91
  1093.3 1686.66  1142.1 1687.39  1158.3 1688.16  1179.4 1687.41  1188.1 1687.83
#Mann= 8 ,-1 , 0
       0    .035       0   509.8     .06       0   550.1    .045       0
   576.3     .06       0   719.8    .035       0   849.8     .06       0
  936.35     .04       0 1036.35    .035       0
#XS Ineff= 2 , 0
          503.03 1673.52  589.09         1673.52
Permanent Ineff=
       F       F
Bank Sta=550.1,576.3
XS Rating Curve= 0 ,0
Exp/Cntr=0.5,0.3

Type RM Length L Ch R = 1 ,29619   ,419.4,409.1,396.7
XS GIS Cut Line= 4
     2051709.312      181901.817     2051921.985      182240.358
     2052091.256      182717.789     2052319.989      182945.219
#Sta/Elev= 30
       0 1684.29   179.2 1679.63   264.9 1679.62   308.6 1677.32   408.3 1675.61
   490.2 1676.18   536.8 1677.59   542.9 1676.41   549.8 1670.58   553.3 1669.56
   576.31668.618   595.1  1668.1   600.61668.728   612.5 1671.09   633.4 1671.85
   696.1 1671.58   734.3 1673.06   748.3 1671.99   760.4 1673.78   774.9 1678.92
   786.5 1680.38   814.2 1679.13   906.3 1677.82   999.6 1678.83  1034.1  1680.1
  1052.6 1682.31    1085 1682.24  1131.3 1683.61  1152.7 1685.56  1228.9 1689.16
#Mann= 7 ,-1 , 0
       0    .035       0   499.8     .06       0   576.3    .045       0
   600.6     .06       0   789.8    .035       0   869.8     .06       0
 1136.35    .035       0
#XS Ineff= 2 , 0
          548.69 1672.47  616.57         1672.52
Permanent Ineff=
       F       F
Bank Sta=576.3,600.6
XS Rating Curve= 0 ,0
Exp/Cntr=0.5,0.3

Type RM Length L Ch R = 1 ,29210   ,541,536.8,532
XS GIS Cut Line= 4
     2051290.041      182548.952     2051470.162      182546.782
     2052198.786      182946.579     2052318.578      182967.413
#Sta/Elev= 30
       0 1745.12    22.4 1733.45    32.2 1731.28    61.8 1718.03    84.7  1705.1
   104.4 1695.69   124.1 1684.74   147.1    1680   191.8 1677.63   310.8 1675.74
   348.4 1674.29   370.7 1674.54   479.2 1672.39   524.8 1672.65   553.8 1670.21
   667.4 1670.37   679.4 1669.42   687.31666.654   698.8 1665.77   710.21666.086
   726.2 1667.33   737.4 1672.73   747.1 1673.42   917.1 1674.28   954.5 1675.15
   979.1  1676.8  1030.2 1683.39  1050.7 1683.64  1057.3 1685.63  1132.8 1689.72
#Mann= 6 ,-1 , 0
       0      .1       0     180    .035       0   687.3    .045       0
   710.2    .035       0  960.13     .06       0 1061.24    .035       0
#XS Ineff= 2 , 0
          528.48 1677.04
Permanent Ineff=
       F       F
Bank Sta=687.3,710.2
XS Rating Curve= 0 ,0
Exp/Cntr=0.3,0.1

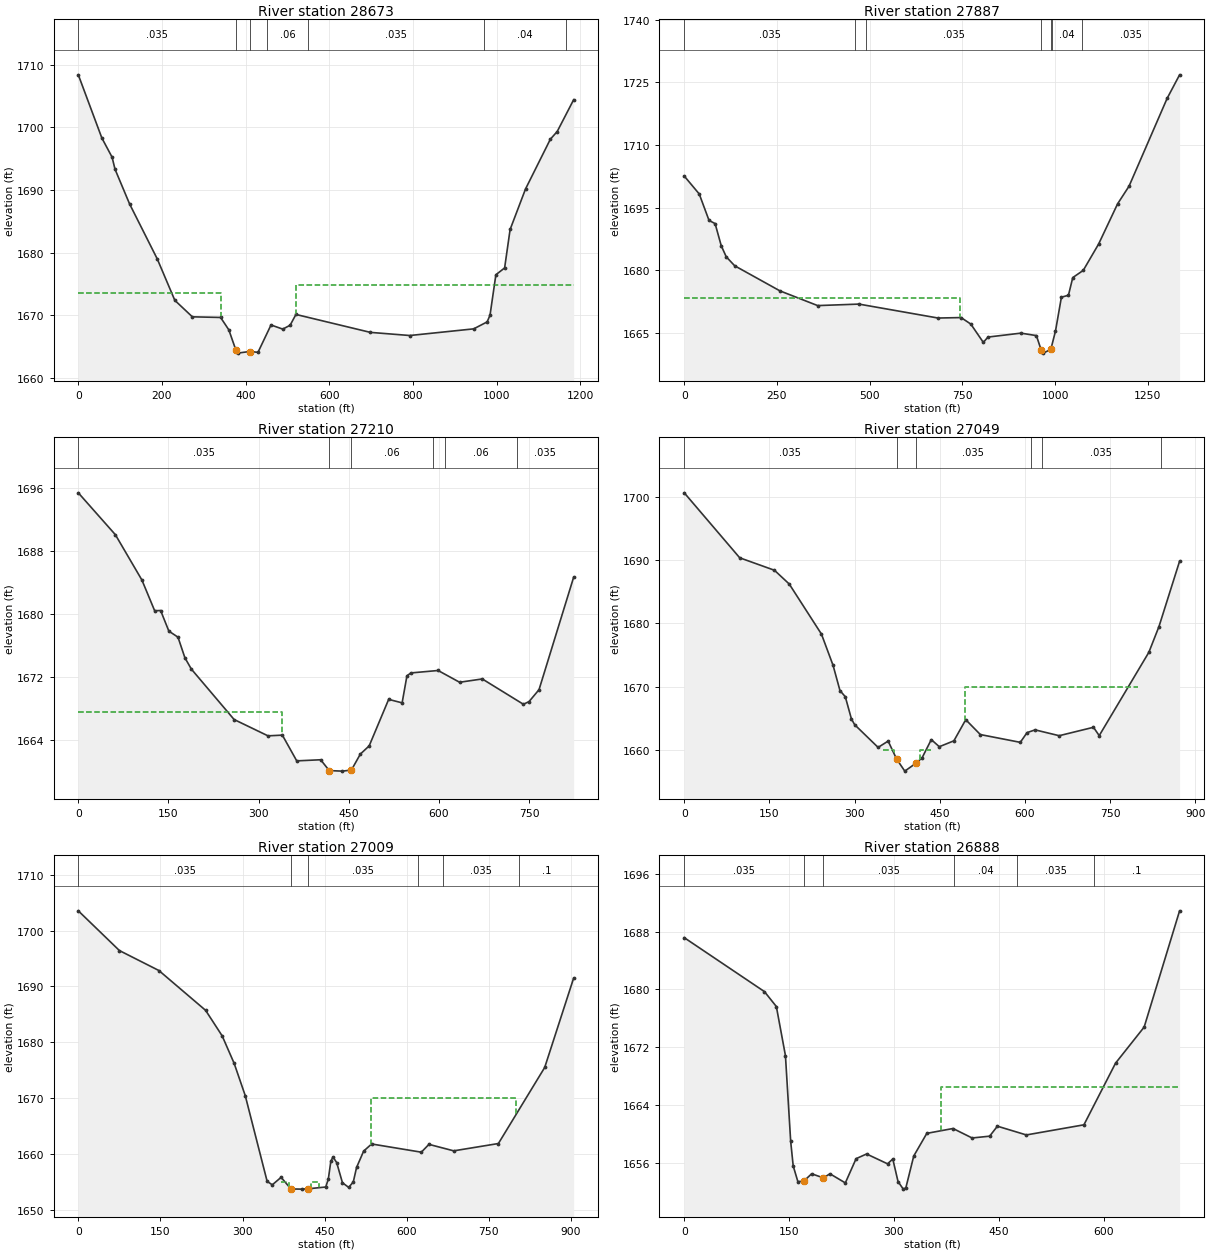
Type RM Length L Ch R = 1 ,28673   ,778,785.9,793.5
XS GIS Cut Line= 3
     2051243.057      183081.996     2052217.016      183433.558
     2052365.453      183438.767
#Sta/Elev= 30
       0 1708.37    56.3 1698.29    80.7 1695.24    87.7 1693.32   122.6 1687.77
   188.9 1678.98   230.7  1672.4   272.6 1669.77   340.1 1669.67   359.8 1667.69
   376.81664.429   380.7 1663.98   409.61664.239   429.5 1664.11   460.6 1668.47
   488.7 1667.81   506.3 1668.43   520.2 1670.15   698.1 1667.29   792.3 1666.79
     945 1667.85   977.2 1668.96   984.1 1670.03   998.1 1676.48    1019 1677.57
  1032.1  1683.7    1069 1690.17  1128.3  1698.1  1144.7 1699.33    1184  1704.4
#Mann= 7 ,-1 , 0
       0    .035       0   376.8    .045       0   409.6    .035       0
     450     .06       0     550    .035       0     970     .04       0
 1165.47    .035       0
#XS Ineff= 2 , 0
          340.61  1673.5  521.21         1674.82
Permanent Ineff=
       F       F
Bank Sta=376.8,409.6
XS Rating Curve= 0 ,0
Exp/Cntr=0.3,0.1

Type RM Length L Ch R = 1 ,27887   ,678.1,677.6,678.7
XS GIS Cut Line= 3
     2051108.183      183413.969     2051576.933      183459.108
       2052118.6      184132.719
#Sta/Elev= 30
       0 1702.57    40.4 1698.28    66.8 1691.94    83.2 1691.18    99.7 1685.88
   113.2 1683.22     136 1681.07   257.9 1675.06   359.7 1671.53   470.9 1671.89
   684.1 1668.55   746.3 1668.66   772.5  1667.1   806.2 1662.71   818.8 1663.99
   907.5 1664.93   949.3 1664.34     9621660.925     968 1660.14   988.21661.053
  1000.7  1665.4  1016.7 1673.54  1035.7 1674.01  1047.3 1678.24  1075.6 1679.97
  1116.9 1686.26  1168.2 1695.92    1199 1700.14  1301.7 1721.19  1335.3 1726.83
#Mann= 7 ,-1 , 0
       0    .035       0     460     .06       0  490.92    .035       0
     962    .045       0   988.2    .035       0  990.92     .04       0
 1070.92    .035       0
#XS Ineff= 2 , 0
          743.84 1673.32
Permanent Ineff=
       F       F
Bank Sta=962,988.2
XS Rating Curve= 0 ,0
Exp/Cntr=0.3,0.1

Type RM Length L Ch R = 1 ,27210   ,159.8,160.5,156.9
XS GIS Cut Line= 2
2051028.07878446183759.1477706742051495.63534349184437.563170048
#Sta/Elev= 30
       0 1695.37    61.7 1690.06   105.8 1684.32     127 1680.43   136.9 1680.46
   150.6 1677.85   165.8 1677.08   177.3 1674.47     188 1673.04   259.1 1666.65
   315.5 1664.58   339.4 1664.67   363.3 1661.41   403.1 1661.55   417.41660.177
     439 1660.11   454.2 1660.24   469.1 1662.27   483.8 1663.31   516.2  1669.2
   538.6 1668.76   546.6 1672.18   553.1 1672.55   598.4 1672.86   634.2 1671.37
   671.9 1671.79   740.3 1668.58   749.7 1668.92   766.3 1670.43   823.9 1684.68
#Mann= 6 ,-1 , 0
       0    .035       0   417.4    .045       0   454.2     .06       0
     590    .035       0     610     .06       0     730    .035       0
#XS Ineff= 2 , 0
          338.38 1667.61
Permanent Ineff=
       F       F
Bank Sta=417.4,454.2
XS Rating Curve= 0 ,0
Exp/Cntr(USF)=0,0
Exp/Cntr=0.5,0.3

Type RM Length L Ch R = 1 ,27049   ,39,40.4,38.5
XS GIS Cut Line= 3
2050881.19360819183867.5089403072051277.02760819184357.092940307
2051492.30560819184469.939940307
#Sta/Elev= 30
       0 1700.64    97.7 1690.37   158.9  1688.4     185 1686.22   241.7 1678.31
   262.2 1673.36   274.3 1669.39   283.7 1668.41   294.5  1664.9   300.2 1663.99
   341.5  1660.4   359.2  1661.4     3741658.573   388.5 1656.65   408.61657.926
     419 1658.76   435.2 1661.63   449.3 1660.51     475 1661.44   495.9 1664.78
   521.6 1662.43     592  1661.2   603.9 1662.74   618.1 1663.17   660.5 1662.25
   720.9 1663.58     731 1662.26   818.5 1675.44   836.3 1679.51   872.6 1689.83
#Mann= 6 ,-1 , 0
       0    .035       0     374    .045       0   408.6    .035       0
     610     .04       0  629.58    .035       0  839.58      .1       0
#XS Ineff= 3 ,-1
     350     370    1660     415     435    1660     495     800    1670
Permanent Ineff=
       F       F       F
Bank Sta=374,408.6
XS Rating Curve= 0 ,0
Exp/Cntr=0.5,0.3

Type RM Length L Ch R = 1 ,27009   ,125.2,121.3,111.4
XS GIS Cut Line= 3
2050832.53303731      183884.4552051257.53503731      184383.529
2051474.89403731      184505.983
#Sta/Elev= 30
       0 1703.54    75.1 1696.43   147.2 1692.86   232.6 1685.73   262.8 1681.17
   284.8 1676.23     305 1670.47     345 1655.13   354.4 1654.51   370.5 1655.85
   388.51653.775   407.9 1653.74   419.8  1653.8   452.1 1654.12   456.8 1655.56
   461.4 1658.74   465.3 1659.49     472  1658.5   482.6 1654.88     494 1654.05
   502.4 1655.03   508.4 1657.62   521.3 1660.54   535.9 1661.82   626.7 1660.35
   640.6 1661.75   685.9 1660.59   767.5  1661.9   852.1 1675.51     905 1691.51
#Mann= 6 ,-1 , 0
       0    .035       0   388.5    .045       0   419.8    .035       0
     620     .04       0  665.52    .035       0  805.52      .1       0
#XS Ineff= 3 ,-1
     370     385    1655     425     440    1655     534     800    1670
Permanent Ineff=
       F       F       F
Bank Sta=388.5,419.8
XS Rating Curve= 0 ,0
Exp/Cntr=0.5,0.3

Type RM Length L Ch R = 1 ,26888   ,285.7,267.2,235.6
XS GIS Cut Line= 3
2050836.13902437184207.8923596252050932.08575578184216.597162621
2051468.42125981184512.333562038
#Sta/Elev= 30
       0 1687.16   114.8  1679.7   131.8 1677.64   144.8 1670.86   152.3 1658.99
   155.9 1655.61   162.6 1653.43   171.21653.524   182.3 1654.52   199.11653.955
   208.5 1654.52   230.5 1653.26   245.9 1656.61   260.9 1657.26   290.9  1655.9
   298.4 1656.56   305.9 1653.45   313.4  1652.4   317.1 1652.58   328.4 1656.98
   347.1 1660.11   384.6 1660.78   411.9 1659.47     437 1659.72   448.1  1661.1
   489.5 1659.89   571.9 1661.29   617.2 1669.82   658.1  1674.8   708.8 1690.87
#Mann= 6 ,-1 , 0
       0    .035       0   171.2    .045       0   199.1    .035       0
  386.34     .04       0  476.34    .035       0  586.34      .1       0
#XS Ineff= 2 , 0
                          367.68         1666.48
Permanent Ineff=
       F       F
Bank Sta=171.2,199.1
XS Rating Curve= 0 ,0
Exp/Cntr(USF)=0,0
Exp/Cntr=0.5,0.3