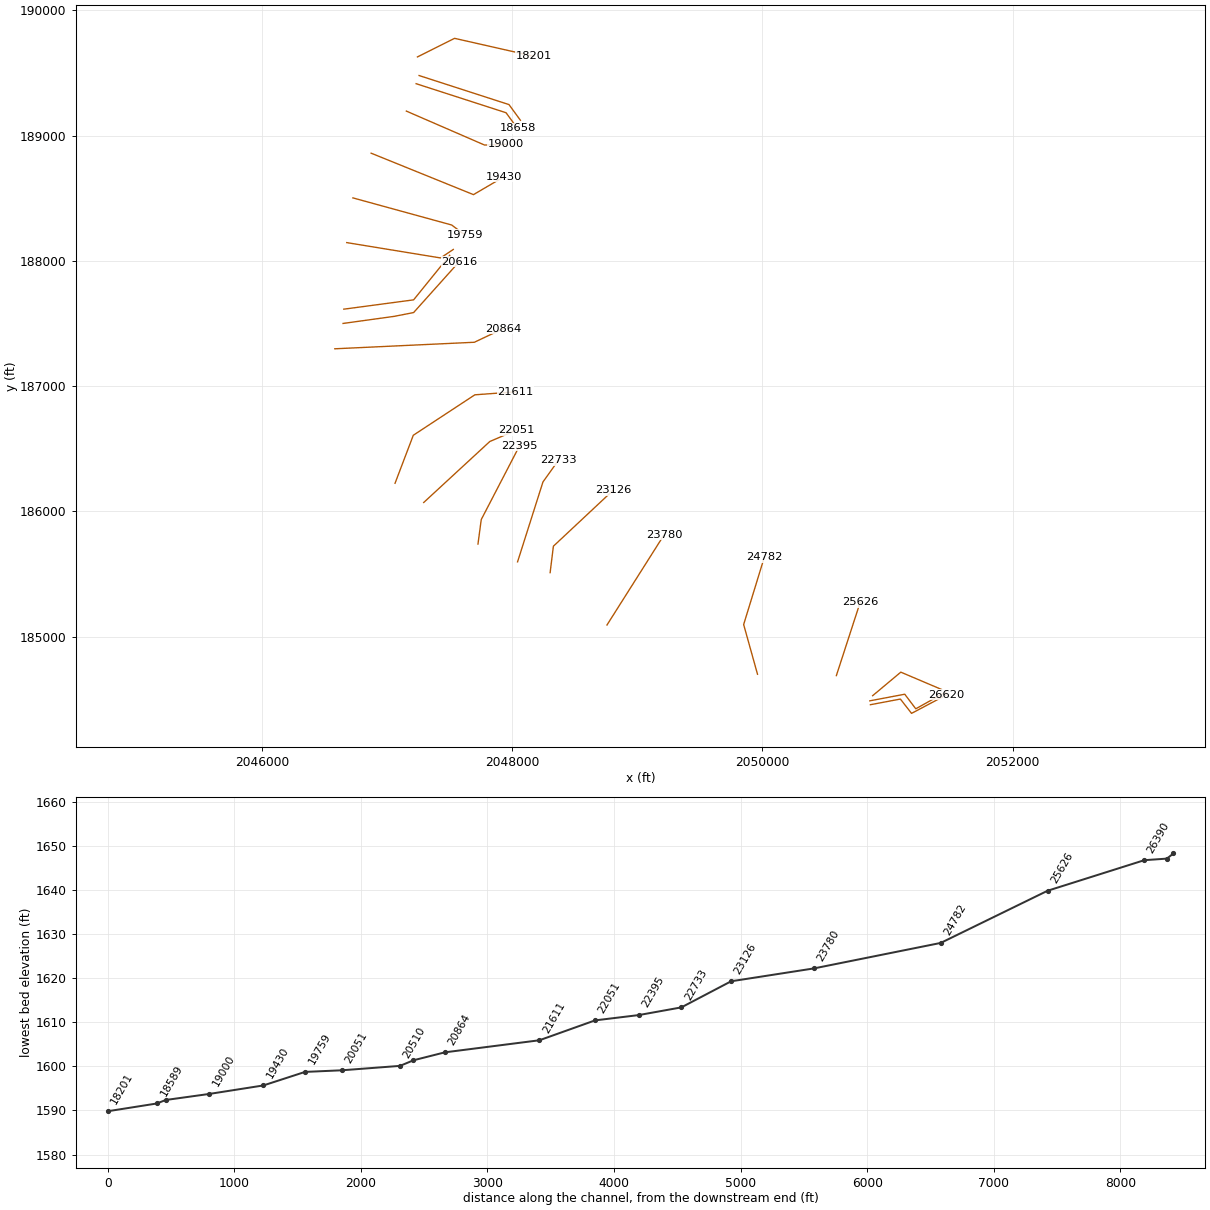
HEC-RAS study HNSCK.prj: HNSCK

--- HNSCK.g01 (geometry) --- (continued)

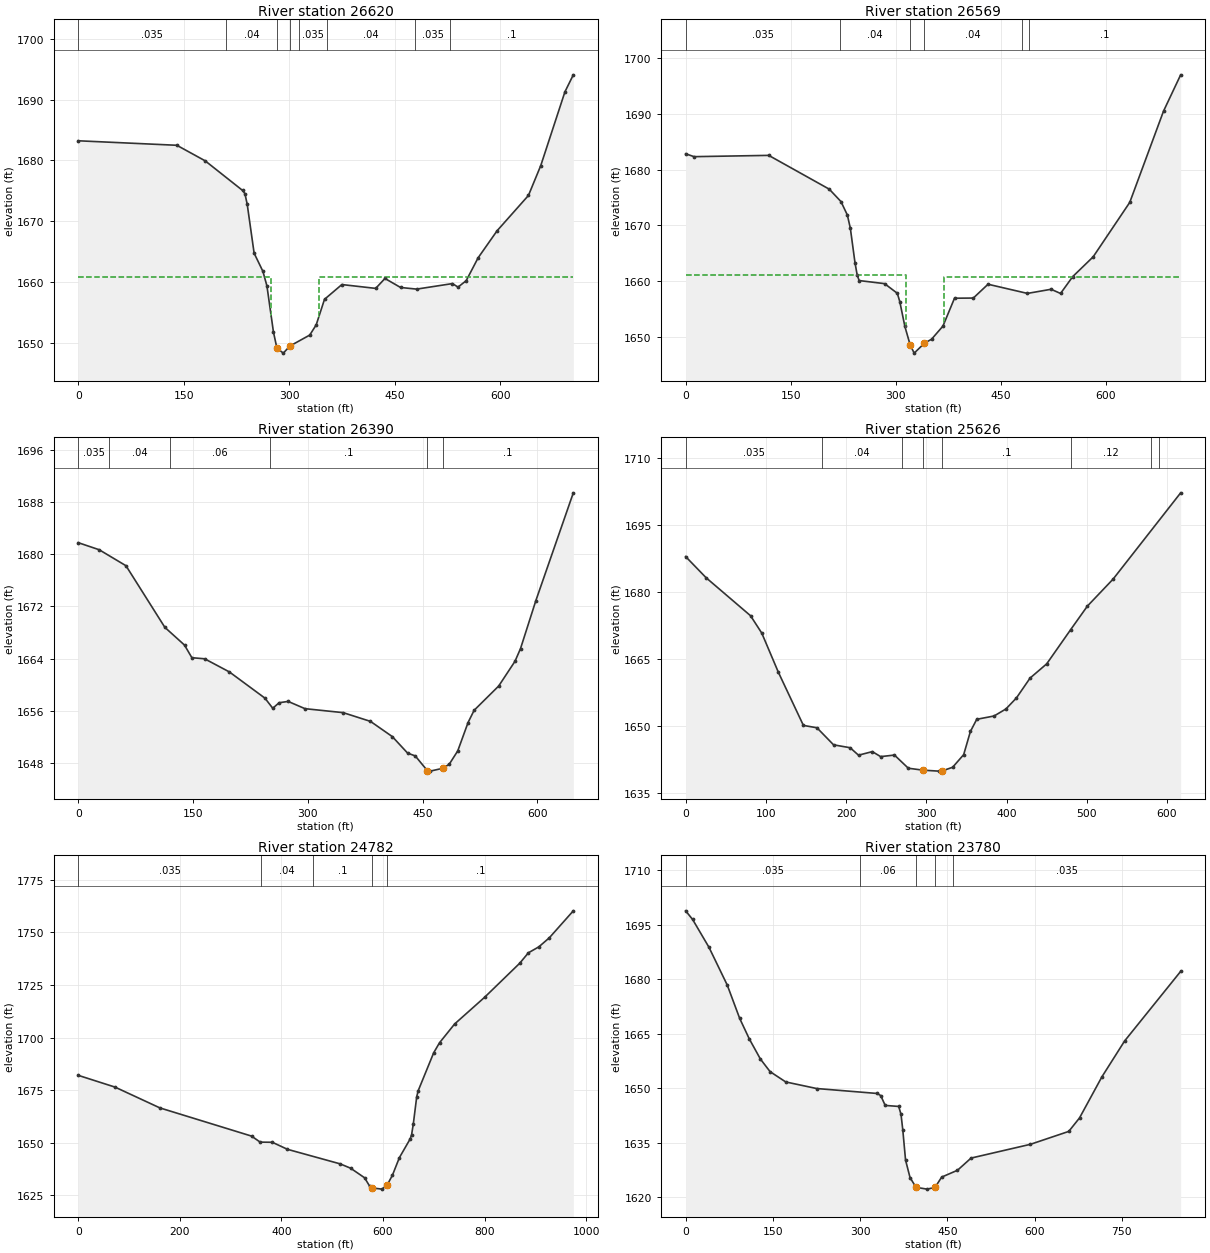
Type RM Length L Ch R = 1 ,26620   ,52,51.5,51.2
XS GIS Cut Line= 4
2050863.00285856184457.744055244 2051102.5994669184502.856387359
2051191.82163486184388.571812669 2051470.5155977184535.938764243
#Sta/Elev= 30
       0 1683.24   140.2  1682.5   180.5 1679.94   233.7 1675.07     237 1674.55
   240.3 1672.77   250.1 1664.75   262.6 1661.76   268.3 1659.37   277.6 1651.77
   282.51649.143   291.6 1648.31     301 1649.48   329.2 1651.28   338.4 1652.96
   350.2 1657.16   374.9 1659.59     423 1658.96   436.2 1660.59   458.4 1659.11
   481.3 1658.84   532.2 1659.75   540.1 1659.17   551.7 1660.22   568.7 1663.99
   595.7 1668.44   640.3 1674.25   657.8 1679.16   692.2  1691.3   704.1 1694.09
#Mann= 8 ,-1 , 0
       0    .035       0     210     .04       0   282.5    .045       0
     301     .04       0  313.81    .035       0  353.81     .04       0
  478.79    .035       0  528.79      .1       0
#XS Ineff= 2 , 0
          274.75 1660.84  341.82         1660.84
Permanent Ineff=
       F       F
Bank Sta=282.5,301
XS Rating Curve= 0 ,0
Exp/Cntr(USF)=0,0
Exp/Cntr=0.5,0.3

Type RM Length L Ch R = 1 ,26569   ,169.6,179,185.4
XS GIS Cut Line= 4
     2050858.183      184488.6222051137.45091046 184541.46240673
2051225.62754104184425.047029846     2051467.558      184559.803
#Sta/Elev= 30
       0 1682.82      12  1682.3   118.7 1682.53   205.2 1676.48   221.9 1674.26
     231 1671.86   235.3 1669.49   241.9 1663.35   245.1 1661.08   247.9 1660.12
   284.2 1659.57   302.4 1657.84   305.9 1656.37   313.2 1651.91   320.8 1648.58
   326.5 1647.13   341.21648.912   351.3 1649.62   367.6 1651.97   384.1 1656.96
     411 1656.99     432 1659.46   488.3 1657.82   522.1 1658.56   535.6 1657.81
     553 1660.83   582.2 1664.37   634.5 1674.12   682.7 1690.45   707.2 1696.95
#Mann= 6 ,-1 , 0
       0    .035       0     220     .04       0   320.8    .045       0
   341.2     .04       0  480.26    .035       0  490.26      .1       0
#XS Ineff= 2 , 0
          315.15 1661.11  369.29         1660.84
Permanent Ineff=
       F       F
Bank Sta=320.8,341.2
XS Rating Curve= 0 ,0
Exp/Cntr=0.5,0.3

Type RM Length L Ch R = 1 ,26390   ,736.4,763.8,785.9
XS GIS Cut Line= 3
     2050881.078      184529.9132051106.02424256184717.606961055
 2051431.7553946184579.421219729
#Sta/Elev= 30
       0 1681.77    27.3 1680.69    62.3 1678.24   113.1  1668.8   138.8 1666.08
   148.4 1664.15   165.1 1663.98   197.4 1661.97   243.9 1657.95   254.1  1656.4
   262.4 1657.25   274.2 1657.45   296.2 1656.34   346.1 1655.73   381.8 1654.39
   410.3 1652.06   430.3 1649.53   440.3  1649.1     4561646.858   459.8 1646.77
   475.91647.194   484.6 1647.81   495.8 1649.87   509.3 1654.22   517.2 1656.09
   549.3 1659.81   570.6  1663.6   577.8 1665.54   597.9 1672.91   646.8 1689.41
#Mann= 6 ,-1 , 0
       0    .035       0      40     .04       0     120     .06       0
     250      .1       0     456    .045       0   475.9      .1       0
Bank Sta=456,475.9
XS Rating Curve= 0 ,0
Exp/Cntr=0.3,0.1

Type RM Length L Ch R = 1 ,25626   ,843.3,844.6,843.7
XS GIS Cut Line= 2
     2050590.822      184690.011     2050781.794      185276.817
#Sta/Elev= 30
       0  1687.9    25.7 1683.13    80.9 1674.65    94.9 1670.76   115.6 1661.98
   146.8 1650.08   163.7 1649.55   184.4 1645.73   205.1 1645.08   215.5 1643.41
   232.7 1644.21   243.1 1643.09   260.3 1643.44   277.6 1640.49     2961640.052
   315.5 1639.84     3201639.906   332.8  1640.7   346.6 1643.53     355 1648.73
   362.9 1651.45   384.5 1652.19   399.3 1653.77   412.3 1656.22   429.4 1660.69
   450.1 1663.87     480 1671.54   500.8  1676.8   532.9 1682.86   617.1 1702.18
#Mann= 8 ,-1 , 0
       0    .035       0     170     .04       0     270      .1       0
     296    .045       0     320      .1       0     480     .12       0
     580     .06       0     590      .1       0
Bank Sta=296,320
XS Rating Curve= 0 ,0
Exp/Cntr=0.3,0.1

Type RM Length L Ch R = 1 ,24782   ,1007.5,1001.5,993.6
XS GIS Cut Line= 3
     2049960.614      184700.775     2049849.828      185097.621
     2050015.301      185635.671
#Sta/Elev= 30
       0 1682.08    72.2 1676.51   160.7 1666.61   341.2 1653.21   358.2 1650.34
   382.1 1650.27     412 1646.92   515.7 1640.01   536.3 1637.95   563.8  1633.4
   574.1  1629.3   578.9 1628.56   598.1    1628   608.4 1629.98   618.7 1634.63
   632.4 1642.98   653.6 1651.87   656.4 1653.83   659.9 1659.16   666.5 1671.91
   669.3 1674.72     700 1692.85   711.4 1697.57   741.2 1706.51   800.6 1719.28
   869.3 1735.36   886.4 1740.33     907 1743.17   927.6 1747.45   974.9 1760.29
#Mann= 5 ,-1 , 0
       0    .035       0     360     .04       0  462.02      .1       0
   578.9    .045       0   608.4      .1       0
Bank Sta=578.9,608.4
XS Rating Curve= 0 ,0
Exp/Cntr=0.3,0.1

Type RM Length L Ch R = 1 ,23780   ,659.5,654.4,648.6
XS GIS Cut Line= 2
     2048757.489      185094.004     2049213.218      185812.754
#Sta/Elev= 30
       0 1698.79      12 1696.41    40.1 1688.76    71.5 1678.38    92.9  1669.2
   109.5 1663.53   128.5 1658.02   145.2 1654.54   172.1 1651.71   225.2  1649.9
   329.3 1648.54   335.4 1647.96   343.1 1645.25   366.3 1644.97   370.3 1642.79
   373.4 1638.43   378.1 1630.21   385.8  1625.4   396.11622.711   415.1 1622.22
   428.81622.693   440.2 1625.53   467.4 1627.41   490.7 1630.76   592.8 1634.55
   658.7  1638.1   677.2 1641.81   715.7 1653.12   754.8    1663   851.1 1682.13
#Mann= 5 ,-1 , 0
       0    .035       0     300     .06       0   396.1    .045       0
   428.8     .06       0     460    .035       0
Bank Sta=396.1,428.8
XS Rating Curve= 0 ,0
Exp/Cntr=0.3,0.1

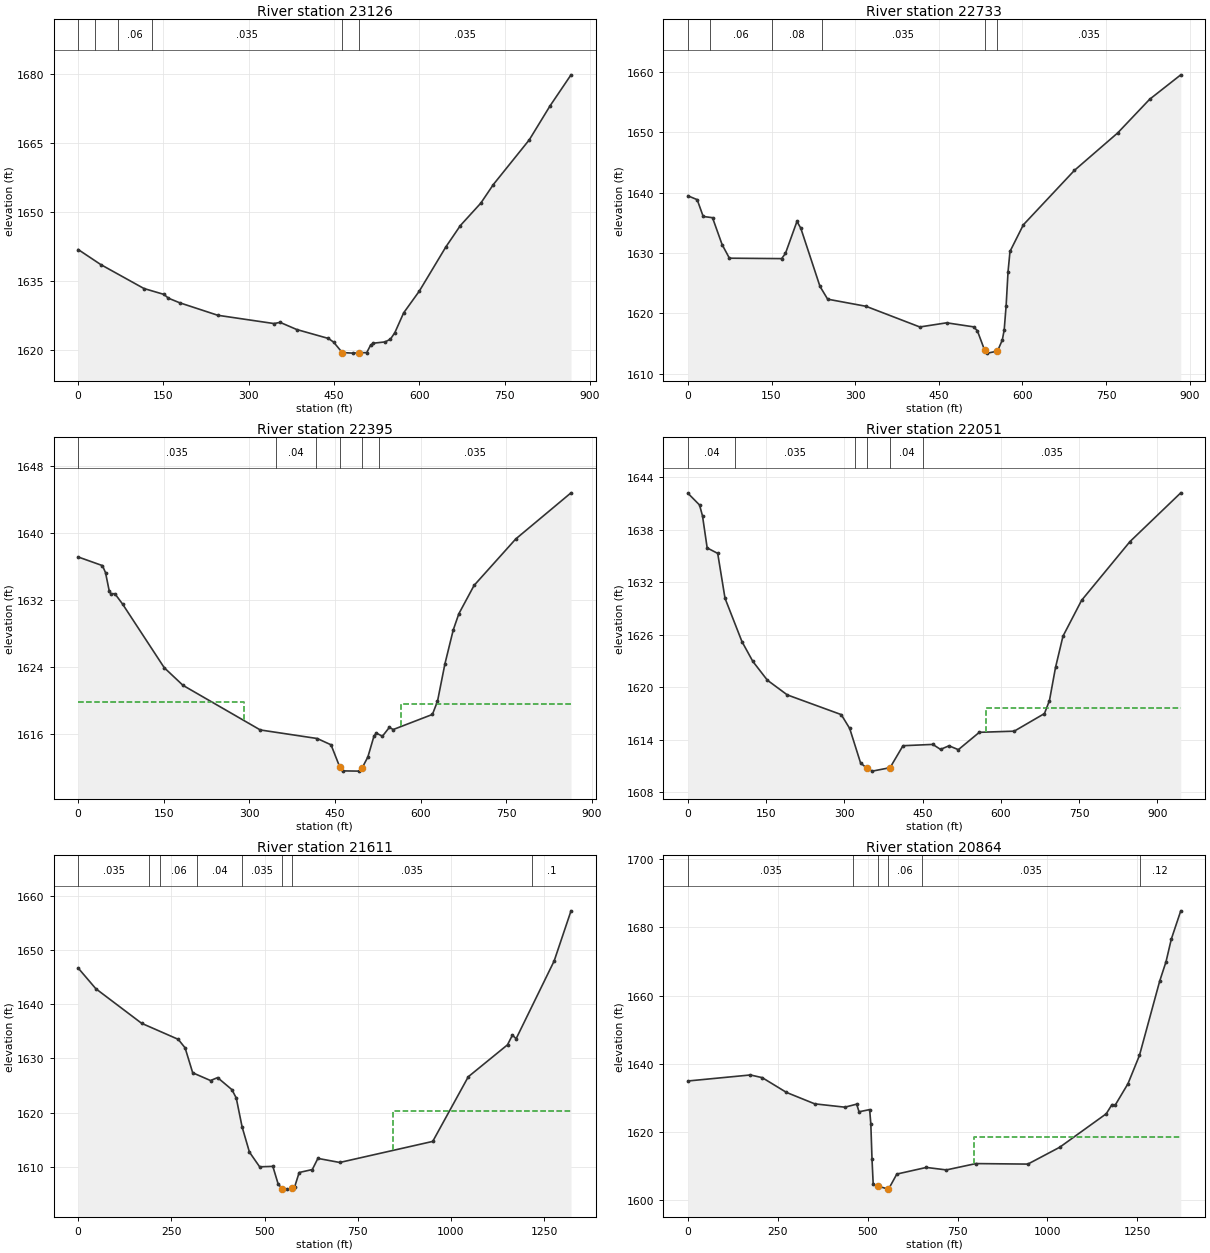
Type RM Length L Ch R = 1 ,23126   ,384,393.1,401
XS GIS Cut Line= 3
     2048302.953      185511.683     2048328.995      185722.621
     2048806.968      186169.525
#Sta/Elev= 30
       0 1641.83    39.7 1638.56   115.7 1633.35   150.9 1632.07   158.7 1631.25
   178.5 1630.25   245.6 1627.53   344.4 1625.73   355.2 1625.99   384.5 1624.43
   440.2 1622.49   449.4 1621.68   464.51619.417   483.6  1619.3   493.91619.374
   507.5 1619.41   514.4 1621.04   519.1 1621.46     540 1621.74   549.3 1622.35
     557 1623.75   572.5 1628.06   600.2 1632.82   646.8 1642.41   672.3 1647.05
   708.2 1651.92   730.3 1655.97   793.5 1665.69   830.1 1673.09   866.9 1679.82
#Mann= 6 ,-1 , 0
       0     .06       0      30     .08       0      70     .06       0
     130    .035       0   464.5    .045       0   493.9    .035       0
Bank Sta=464.5,493.9
XS Rating Curve= 0 ,0
Exp/Cntr=0.3,0.1

Type RM Length L Ch R = 1 ,22733   ,343,337.4,333.5
XS GIS Cut Line= 3
     2048042.536      185597.621     2048245.661      186235.642
     2048370.661      186410.121
#Sta/Elev= 30
       0 1639.48    16.6 1638.84    27.4 1636.05    44.1 1635.85    61.3 1631.39
    74.4 1629.13   168.1 1629.06   174.9 1629.91   195.6 1635.23   202.5  1634.1
   236.9 1624.45   250.7 1622.33   319.5 1621.15     416 1617.72   464.2 1618.41
   512.4 1617.74   519.2 1617.11   532.41613.837   537.2 1613.38   555.31613.704
     564 1615.55   567.4 1617.22   570.9 1621.28   574.3 1626.88   577.8 1630.25
   601.8 1634.67   693.3 1643.69   770.9  1649.9   828.3 1655.49   884.2 1659.55
#Mann= 6 ,-1 , 0
       0      .1       0      40     .06       0     150     .08       0
     240    .035       0   532.4    .045       0   555.3    .035       0
Bank Sta=532.4,555.3
XS Rating Curve= 0 ,0
Exp/Cntr=0.3,0.1

Type RM Length L Ch R = 1 ,22395   ,359.5,344.4,340.4
XS GIS Cut Line= 3
     2047726.239      185739.837      2047752.28       185935.15
     2048059.572      186526.296
#Sta/Elev= 30
       0 1637.17    42.5 1636.14    47.9  1635.3    54.5 1633.08    57.1  1632.8
    64.4 1632.78    77.7 1631.56   150.8 1623.96   183.6 1621.86     319 1616.54
   418.7 1615.52   442.9 1614.77   458.31612.107     463 1611.66   492.6 1611.63
   497.51612.033   507.4 1613.31   518.1  1615.8   522.2 1616.17   532.9 1615.79
   545.1 1616.85   551.8 1616.59   620.5 1618.39   629.4 1619.96   642.4 1624.42
     657 1628.47   666.8  1630.4   693.5 1633.78   766.5 1639.32   863.3 1644.82
#Mann= 6 ,-1 , 0
       0    .035       0  347.04     .04       0  417.04     .06       0
   458.3    .045       0   497.5     .06       0  527.04    .035       0
#XS Ineff= 2 , 0
          289.97  1619.9   566.1         1619.67
Permanent Ineff=
       F       F
Bank Sta=458.3,497.5
XS Rating Curve= 0 ,0
Exp/Cntr=0.3,0.1

Type RM Length L Ch R = 1 ,22051   ,444.2,439.7,437.6
XS GIS Cut Line= 3
     2047292.536      186071.579     2047821.182      186558.558
     2048029.516        186647.1
#Sta/Elev= 30
       0 1642.14    22.3  1640.8      28 1639.54    36.9  1635.9    57.1 1635.28
    71.1 1630.16   103.6 1625.21   124.5 1622.95   152.3 1620.81   190.5 1619.13
     294 1616.88   310.2  1615.3   331.1 1611.36     3431610.771   353.6 1610.43
   387.61610.823   412.4 1613.33   469.6 1613.48   484.4 1612.91   500.6 1613.32
   518.6 1612.88   558.8 1614.86   625.7 1614.99   683.7    1617   693.3 1618.49
   704.9 1622.26   719.2 1625.83   754.9 1629.92   847.6 1636.62   945.1 1642.19
#Mann= 6 ,-1 , 0
       0     .04       0      90    .035       0     320     .04       0
     343    .045       0   387.6     .04       0     450    .035       0
#XS Ineff= 2 , 0
                          570.71         1617.59
Permanent Ineff=
       F       F
Bank Sta=343,387.6
XS Rating Curve= 0 ,0
Exp/Cntr=0.3,0.1

Type RM Length L Ch R = 1 ,21611   ,753.2,747.1,731.7
XS GIS Cut Line= 4
      2047063.37      186225.225     2047209.203      186608.038
     2047701.391      186930.954     2048024.307      186954.392
#Sta/Elev= 30
       0 1646.64    47.4 1642.83   170.3 1636.46   268.4 1633.51   286.8 1631.94
   307.2 1627.35     355 1625.92     374 1626.46   412.3 1624.25     424 1622.71
   439.7 1617.39   459.4 1612.74   486.8 1610.03   522.2 1610.11   536.4 1606.87
     5471606.001   561.4 1605.92   573.2 1606.07     581  1606.4   592.8 1608.98
   628.1 1609.53     643 1611.58   701.7 1610.83   951.1 1614.71  1046.5 1626.62
  1151.7  1632.5  1164.9 1634.29  1174.8 1633.62  1276.8 1647.94  1322.1 1657.18
#Mann= 8 ,-1 , 0
       0    .035       0     190     .04       0     220     .06       0
     320     .04       0  439.65    .035       0     547    .045       0
   573.2    .035       0 1218.31      .1       0
#XS Ineff= 2 , 0
                          843.64         1620.29
Permanent Ineff=
       F       F
Bank Sta=547,573.2
XS Rating Curve= 0 ,0
Exp/Cntr=0.3,0.1

Type RM Length L Ch R = 1 ,20864   ,244.2,247.7,250.2
XS GIS Cut Line= 3
2046581.72660186187298.1958732582047697.17860186187350.278873258
2047927.21260186187458.785873258
#Sta/Elev= 30
       0 1634.93   173.8  1636.7   206.7 1635.91   274.2 1631.57   352.7 1628.22
   436.6 1627.24   469.4 1628.13     476 1625.89   505.5 1626.53   508.8 1622.32
   512.1 1611.92   515.4 1604.59   528.31604.087   555.61603.224   558.1 1603.18
   581.1  1607.6   663.2 1609.55     719 1608.82   801.1 1610.68   945.7 1610.53
  1034.3 1615.48  1163.6  1625.3  1179.6 1627.99    1189 1627.92    1224 1634.11
    1256 1642.42  1312.3 1664.24    1330 1669.96  1344.7  1676.6    1371 1684.89
#Mann= 6 ,-1 , 0
       0    .035       0     460     .04       0   528.3    .045       0
   555.6     .06       0     650    .035       0 1256.67     .12       0
#XS Ineff= 2 , 0
                           795.7         1618.58
Permanent Ineff=
       F       F
Bank Sta=528.3,555.6
XS Rating Curve= 0 ,0
Exp/Cntr=0.5,0.3

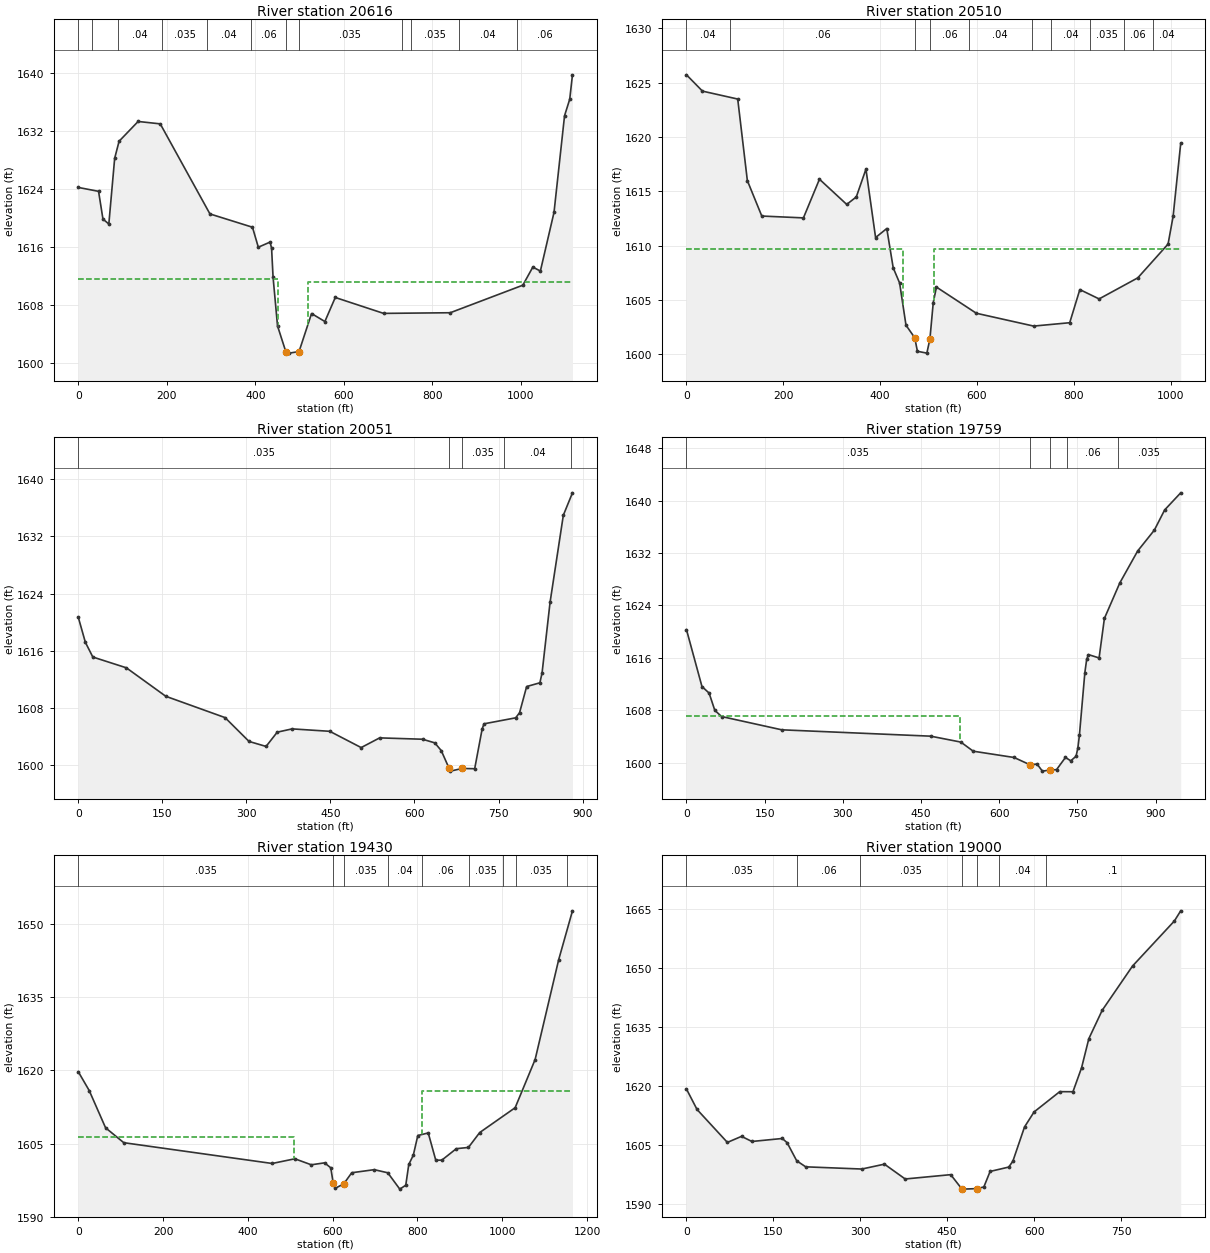
Type RM Length L Ch R = 1 ,20616   ,109.6,106.6,107.6
XS GIS Cut Line= 4
2046647.56775142187500.464502849     2047057.402      187557.112
2047211.73915876187587.379068615     2047576.391      187993.454
#Sta/Elev= 30
       0 1624.19    45.9 1623.65    55.8 1619.84    69.1 1619.15    82.3  1628.2
    92.3 1630.55   135.3 1633.27   185.3 1632.94   297.6 1620.54   393.7 1618.71
   406.9 1615.96   433.6 1616.67   436.9 1615.79   440.2 1611.86   450.3 1605.13
   469.21601.546   476.6 1601.38   498.91601.592   527.2 1606.83   557.3 1605.73
   580.8 1609.04     690 1606.85   840.6 1606.94  1004.6 1610.73  1027.2 1613.22
  1044.3 1612.68  1075.1 1620.76  1098.9 1634.06  1110.6 1636.33  1116.8 1639.69
#Mann= 12 ,-1 , 0
       0    .035       0      30     .06       0      90     .04       0
     190    .035       0     290     .04       0     390     .06       0
   469.2    .045       0   498.9    .035       0  731.01     .04       0
  751.01    .035       0  861.01     .04       0  991.01     .06       0
#XS Ineff= 2 , 0
          451.92 1611.54  518.93         1611.19
Permanent Ineff=
       F       F
Bank Sta=469.2,498.9
XS Rating Curve= 0 ,0
Exp/Cntr=0.5,0.3

Type RM Length L Ch R = 1 ,20510   ,455.8,458.4,438.9
XS GIS Cut Line= 3
     2046653.756      187614.403     2047211.807      187688.767
      2047500.11      188044.091
#Sta/Elev= 30
       0 1625.73      33 1624.23   105.8  1623.5   125.7 1615.99   155.5 1612.73
   241.5 1612.56   274.6 1616.12   330.9  1613.8   350.7 1614.49   370.6 1617.05
   390.5 1610.75   413.6 1611.58   426.9 1607.96   440.1 1606.57   453.3 1602.68
   471.31601.529   476.9 1600.28   496.4 1600.11   502.71601.412   509.6 1604.77
   516.2 1606.19   598.6 1603.78   716.9  1602.6   791.4 1602.91   812.3 1605.96
   852.1  1605.1     932 1607.04   994.5 1610.15  1004.9 1612.69  1020.6 1619.41
#Mann= 10 ,-1 , 0
       0     .04       0      90     .06       0   471.3    .045       0
   502.7     .06       0  582.98     .04       0  712.98    .035       0
  752.98     .04       0  832.98    .035       0  902.98     .06       0
  962.98     .04       0
#XS Ineff= 2 , 0
          447.12 1609.72  510.27         1609.65
Permanent Ineff=
       F       F
Bank Sta=471.3,502.7
XS Rating Curve= 0 ,0
Exp/Cntr=0.5,0.3

Type RM Length L Ch R = 1 ,20051   ,296.5,292,287.2
XS GIS Cut Line= 3
     2046677.194      188145.653     2047427.194      188023.258
     2047528.756      188090.966
#Sta/Elev= 30
       0 1620.69    12.7 1617.16      26  1615.1    85.8 1613.59   156.2  1609.6
     262 1606.61   304.8 1603.27   335.2 1602.57   355.1 1604.57   381.7 1605.03
   448.9 1604.69   504.9 1602.41   537.9 1603.77   614.4 1603.58   636.3 1603.07
   647.8 1601.99   661.71599.523   664.3 1599.11   684.9 1599.48   707.5 1599.45
   720.8 1605.01   724.1 1605.74   780.7 1606.58   787.6  1607.3   800.2 1610.96
   823.9 1611.49   827.8 1612.91     842 1622.76   865.7 1634.97     882 1638.11
#Mann= 5 ,-1 , 0
       0    .035       0   661.7    .045       0   684.9    .035       0
  759.92     .04       0  879.92    .035       0
Bank Sta=661.7,684.9
XS Rating Curve= 0 ,0
Exp/Cntr=0.3,0.1

Type RM Length L Ch R = 1 ,19759   ,322.7,329.1,317.4
XS GIS Cut Line= 3
     2046726.673      188502.424     2047515.735      188286.278
     2047619.902      188208.153
#Sta/Elev= 30
       0 1620.31    29.7 1611.64    43.4 1610.64    54.3 1608.02    67.2 1607.07
   182.8 1605.04   468.6 1604.07   526.4 1603.17   550.2 1601.78   628.6 1600.82
   658.91599.716   672.7 1599.81   682.9 1598.74     6971598.894   710.1 1598.97
   727.2 1600.83   737.3 1600.31   747.5 1601.01   750.9 1602.24   753.9 1604.18
   764.4 1613.77   767.9 1615.79   771.3 1616.51   791.7    1616   801.9 1622.03
   831.4 1627.43   865.7 1632.31   897.7 1635.49   917.5 1638.57   948.3 1641.18
#Mann= 5 ,-1 , 0
       0    .035       0   658.9    .045       0     697    .035       0
     730     .06       0  828.13    .035       0
#XS Ineff= 2 , 0
          525.25 1607.12
Permanent Ineff=
       F       F
Bank Sta=658.9,697
XS Rating Curve= 0 ,0
Exp/Cntr=0.3,0.1

Type RM Length L Ch R = 1 ,19430   ,430.1,430.6,427.8
XS GIS Cut Line= 3
     2046872.506      188859.195     2047690.214      188528.466
     2047935.006      188671.695
#Sta/Elev= 30
       0 1619.75    25.8 1615.89    64.5 1608.24   107.4 1605.19   457.4 1600.93
   510.9 1601.89   549.6 1600.66   581.1 1601.06   595.6 1600.04   601.21597.007
   606.2 1595.84   626.31596.761   645.1 1599.03   698.2 1599.66   730.1 1599.02
   758.4 1595.67   772.5 1596.47   779.6 1600.72   790.3 1602.63   800.9 1606.66
   825.5 1607.19   843.3  1601.6   857.5 1601.61   891.7 1603.96   920.3 1604.22
   946.9 1607.27  1030.5 1612.36  1077.6 1622.24  1133.1 1642.68  1165.7 1652.73
#Mann= 9 ,-1 , 0
       0    .035       0   601.2    .045       0   626.3    .035       0
     730     .04       0     810     .06       0  922.06    .035       0
 1002.06      .1       0 1032.06    .035       0 1152.06      .1       0
#XS Ineff= 2 , 0
          509.09 1606.42  809.95         1615.83
Permanent Ineff=
       F       F
Bank Sta=601.2,626.3
XS Rating Curve= 0 ,0
Exp/Cntr=0.3,0.1

Type RM Length L Ch R = 1 ,19000   ,344.7,341.2,345.1
XS GIS Cut Line= 3
     2047153.756      189195.133     2047778.756      188924.299
     2047950.631      188929.508
#Sta/Elev= 30
       0 1619.18    18.2 1613.99    70.6 1605.61      95 1607.15   112.9 1605.85
   165.4 1606.61   173.7 1605.54   190.3 1600.93   205.8  1599.4   302.6 1598.84
   341.7 1600.08   377.5 1596.31   456.1 1597.41   474.81593.878   477.6 1593.73
     501 1593.86   513.3 1594.28   524.1 1598.23   556.3 1599.34   563.4 1600.84
   583.5 1609.54     600 1613.36   644.3 1618.52   667.1  1618.5     682  1624.6
   694.5 1631.99   717.5 1639.19     770 1650.48   842.2 1661.93   853.1 1664.51
#Mann= 7 ,-1 , 0
       0    .035       0     190     .06       0     300    .035       0
   474.8    .045       0     501    .035       0     540     .04       0
     620      .1       0
Bank Sta=474.8,501
XS Rating Curve= 0 ,0
Exp/Cntr=0.5,0.3

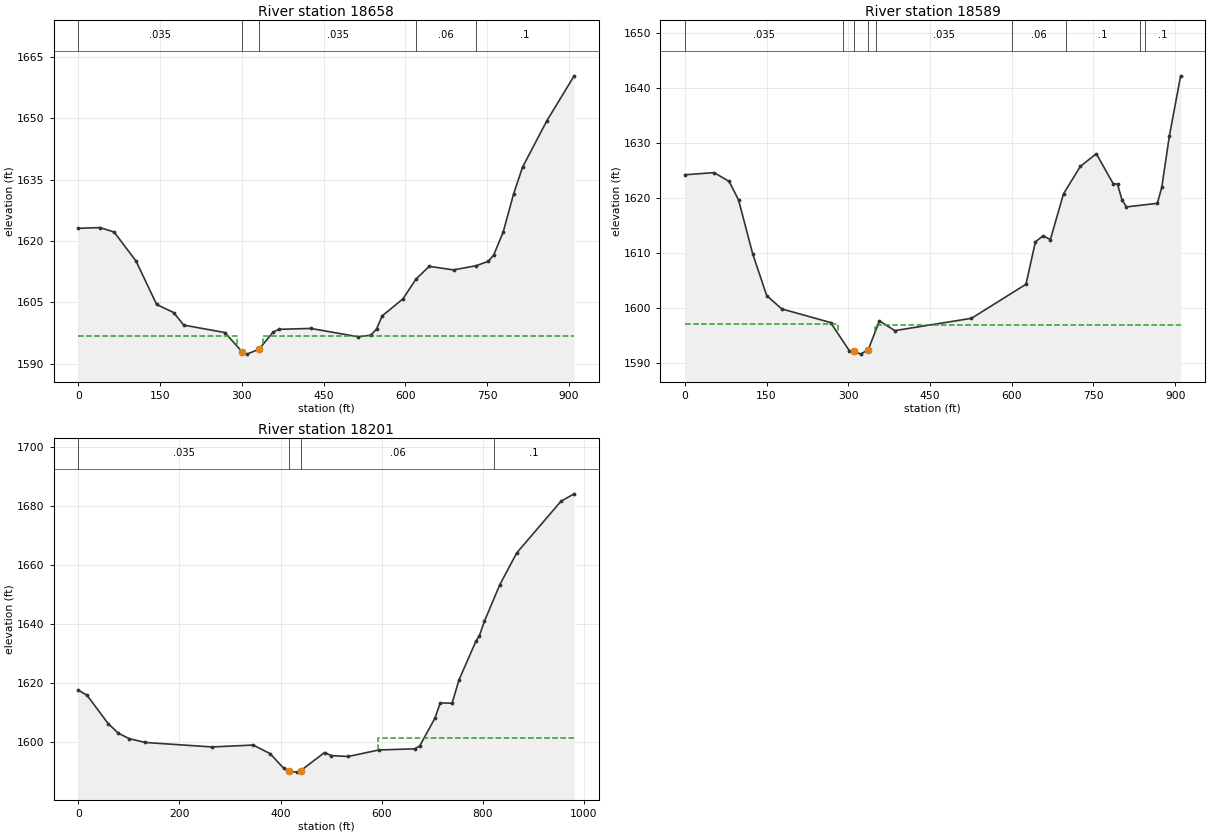
Type RM Length L Ch R = 1 ,18658   ,70.3,69.3,69.6
XS GIS Cut Line= 3
     2047231.881      189413.883     2047950.631      189182.112
     2048041.777      189057.112
#Sta/Elev= 30
       0 1623.11    39.5 1623.29    65.6 1622.21     106 1615.09   143.7  1604.5
     175 1602.53   193.3 1599.47   268.9 1597.64   300.8  1592.9   309.4 1592.37
   331.61593.575   357.7 1597.79     368 1598.43   426.6 1598.65   513.9  1596.6
   536.9 1597.01   547.3 1598.51   557.6 1601.72   595.5 1605.85   619.7 1610.71
   643.8 1613.82   688.6 1612.95     730 1613.97   752.5 1615.06   762.3  1616.6
   779.7 1622.21   798.8 1631.53   815.1 1638.03   859.7 1649.37   909.9 1660.37
#Mann= 5 ,-1 , 0
       0    .035       0   300.8    .045       0   331.6    .035       0
     620     .06       0     730      .1       0
#XS Ineff= 2 , 0
          291.36 1596.83  338.95         1596.69
Permanent Ineff=
       F       F
Bank Sta=300.8,331.6
XS Rating Curve= 0 ,0
Exp/Cntr=0.5,0.3

Type RM Length L Ch R = 1 ,18589   ,386.4,388.2,389.4
XS GIS Cut Line= 3
     2047255.319      189478.987     2047974.069      189247.216
     2048065.214      189122.216
#Sta/Elev= 30
       0 1624.23    53.8 1624.62    81.4 1623.02    98.7 1619.63   124.7  1609.8
   150.3 1602.24   177.9 1599.81   267.5 1597.33     302  1592.2   310.61592.109
   322.7 1591.58   336.71592.403   357.2 1597.63   385.4 1595.86   526.1  1598.1
   626.1  1604.3   643.4 1612.01   657.1  1613.1   670.9 1612.44     695 1620.77
     726 1625.77   755.2 1628.06     786 1622.63   794.1 1622.52   802.3 1619.67
   810.4 1618.38   867.2 1619.03   875.3 1621.94   889.3 1631.32   909.9 1642.24
#Mann= 9 ,-1 , 0
       0    .035       0     290     .06       0   310.6    .045       0
   336.7     .06       0     350    .035       0     600     .06       0
     700      .1       0  835.19     .12       0  845.19      .1       0
#XS Ineff= 2 , 0
          281.89    1597  348.99         1596.95
Permanent Ineff=
       F       F
Bank Sta=310.6,336.7
XS Rating Curve= 0 ,0
Exp/Cntr=0.5,0.3

Type RM Length L Ch R = 1 ,18201   ,744.3,757.4,768.8
XS GIS Cut Line= 3
     2047242.298      189627.424     2047539.173      189775.862
     2048171.985      189632.633
#Sta/Elev= 30
       0 1617.63    17.4 1615.87    58.9 1606.31    79.2 1603.03   100.5 1601.19
   132.3 1599.88   264.4 1598.37   345.7 1599.01   379.3 1596.11   406.2 1591.11
   417.21590.054   432.9 1589.82     4401590.332     487 1596.48   500.4 1595.43
   534.1 1595.13   594.4 1597.34   665.2 1597.73   675.3 1598.72   705.6 1608.23
   715.7 1613.33   739.3 1613.18   752.7 1621.02   786.3 1634.22   793.1 1636.05
   803.1 1640.99   833.5 1653.36   867.1 1664.21   954.5 1681.72   980.7 1684.26
#Mann= 4 ,-1 , 0
       0    .035       0   417.2    .045       0     440     .06       0
  821.92      .1       0
#XS Ineff= 2 , 0
                          593.14         1601.34
Permanent Ineff=
       F       F
Bank Sta=417.2,440
XS Rating Curve= 0 ,0
Exp/Cntr=0.3,0.1