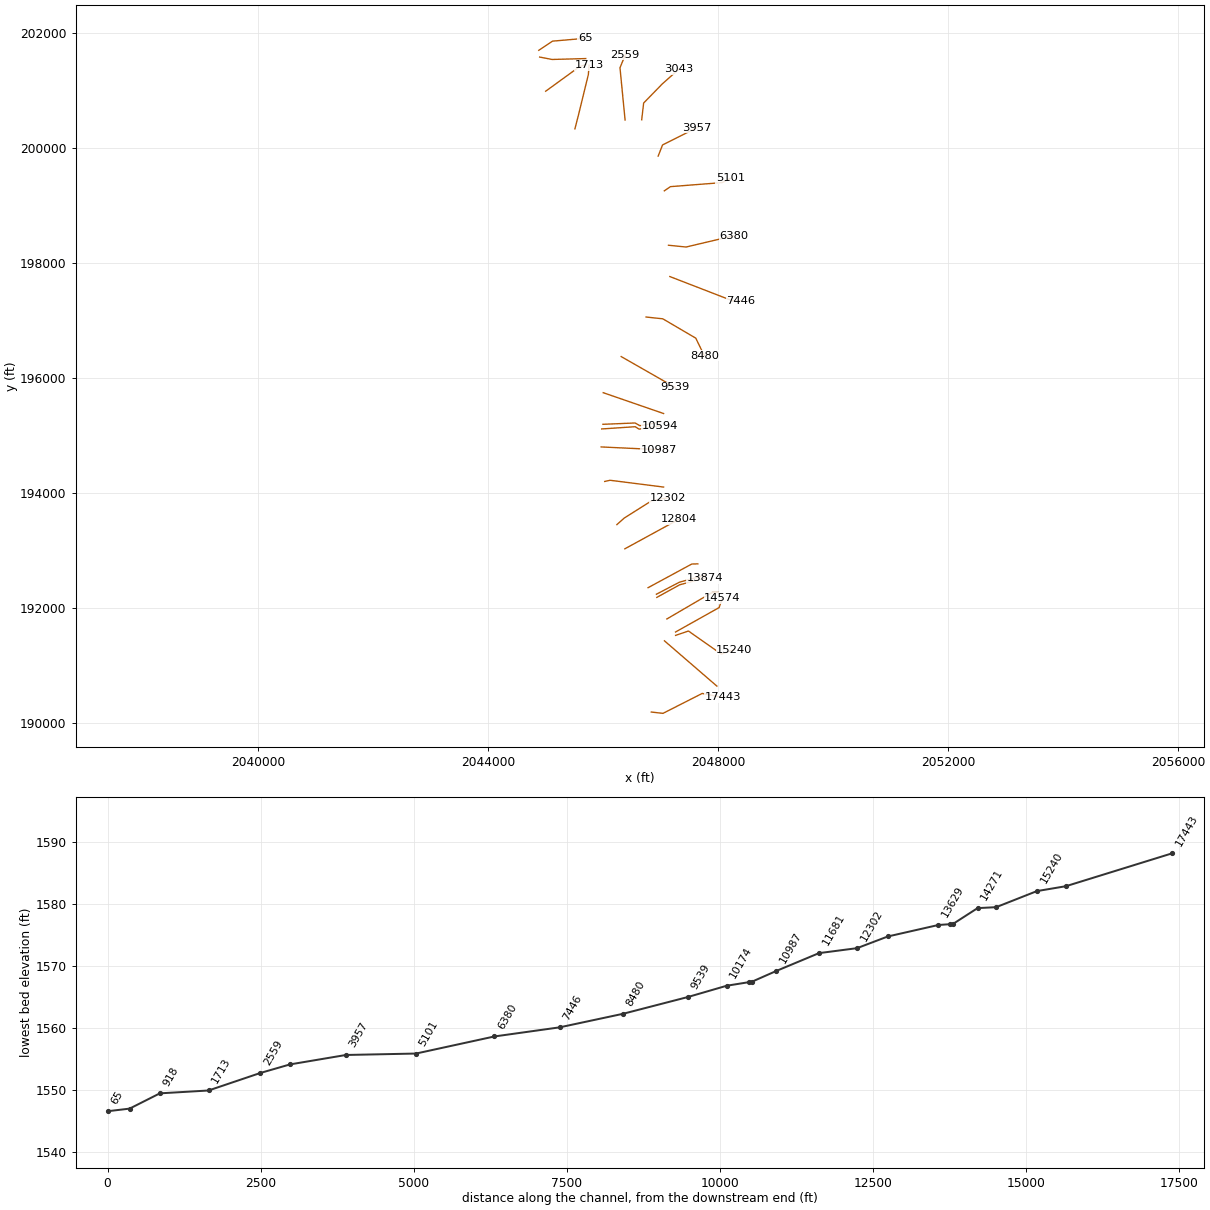
HEC-RAS study HNSCK.prj: HNSCK

--- HNSCK.g01 (geometry) --- (continued)

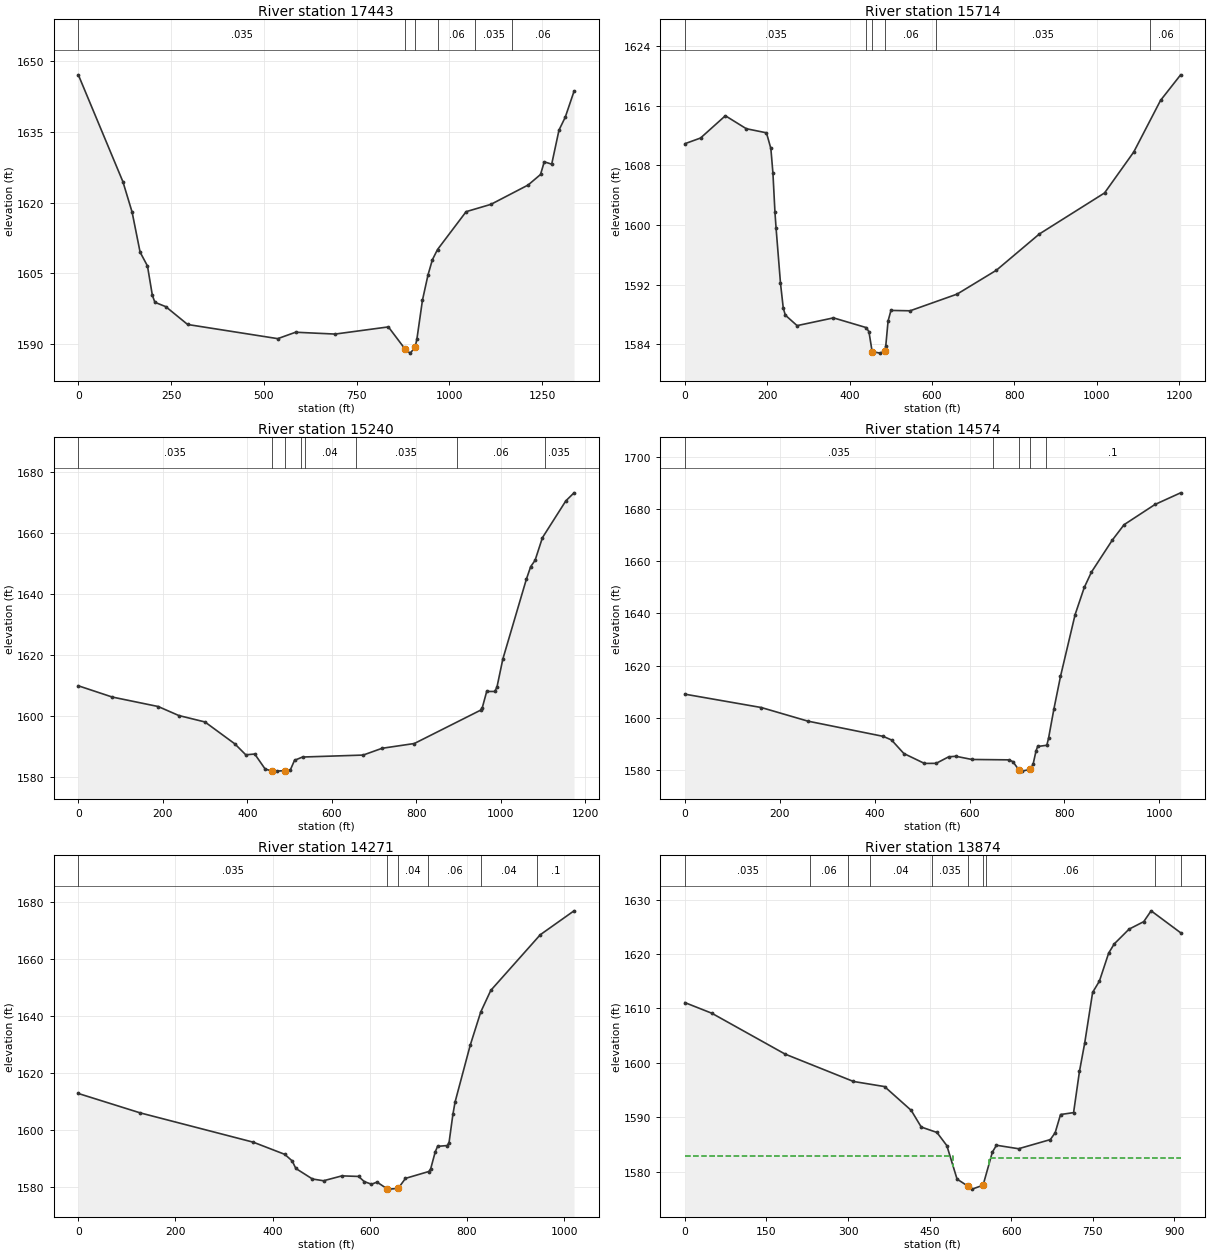
Type RM Length L Ch R = 1 ,17443   ,1737.9,1729.5,1686.2
XS GIS Cut Line= 4
     2046836.048      190195.133     2047039.173      190171.695
     2047721.464      190518.049     2048080.839      190447.737
#Sta/Elev= 30
       0  1647.1   120.2 1624.43   144.9    1618   166.5  1609.5   186.3 1606.58
   199.5 1600.36   206.3 1598.88   235.7 1597.95   294.6 1594.17   537.4 1591.17
   585.5 1592.53     692 1592.14   835.5 1593.66   881.41588.871   894.3  1588.1
   907.51589.305   912.5 1591.14   927.4 1599.35   942.2 1604.64     954 1607.88
   967.9 1610.06    1045 1618.09  1111.8 1619.64  1212.1 1623.74  1245.5 1625.97
  1255.6 1628.66  1275.6 1628.16  1295.3 1635.39  1312.1 1638.11  1335.8 1643.61
#Mann= 6 ,-1 , 0
       0    .035       0   881.4    .045       0   907.5    .035       0
  969.64     .06       0 1069.64    .035       0 1169.64     .06       0
Bank Sta=881.4,907.5
XS Rating Curve= 0 ,0
Exp/Cntr=0.3,0.1

Type RM Length L Ch R = 1 ,15714   ,471.8,474.4,475.1
XS GIS Cut Line= 2
     2047065.214      191432.112     2047976.673      190645.653
#Sta/Elev= 30
       0 1610.92    37.9 1611.68    98.2 1614.67   149.1 1612.93     198 1612.38
   208.7 1610.28   213.7    1607   218.7 1601.69   221.4 1599.57   232.1  1592.2
   238.8 1588.88   243.8 1587.92   272.4 1586.51   360.8 1587.55   440.1 1586.25
   446.9  1585.7   454.7 1583.02   474.2 1582.82   485.51583.124   487.7 1583.73
   493.4 1587.13   500.4 1588.55   546.9  1588.5   661.1 1590.74   756.4 1593.94
   860.9 1598.81  1019.1 1604.31  1090.1 1609.81  1155.1 1616.73  1203.9 1620.16
#Mann= 6 ,-1 , 0
       0    .035       0     440     .06       0   454.7    .045       0
   485.5     .06       0     610    .035       0    1130     .06       0
Bank Sta=454.7,485.5
XS Rating Curve= 0 ,0
Exp/Cntr=0.3,0.1

Type RM Length L Ch R = 1 ,15240   ,642.4,665.6,678.4
XS GIS Cut Line= 4
     2047258.682      191527.308     2047482.641      191602.829
     2048052.953      191201.788     2048279.516      191279.913
#Sta/Elev= 30
       0 1609.94    80.3 1606.26     189 1603.16   237.7 1600.22   299.7 1598.11
   370.4 1590.95   396.3 1587.37   417.5 1587.62   442.2 1582.71   458.31582.078
   470.3 1582.03   488.41582.199     502  1582.5   511.7 1585.57   530.6 1586.64
   674.1 1587.28   718.9  1589.5   795.2 1591.06     952 1601.96   956.1 1602.78
   966.5 1608.09   985.5 1608.08   990.8 1609.51  1004.7 1618.68  1060.2 1644.71
  1070.6 1648.91    1081 1650.97  1098.4 1658.38  1153.9 1670.44  1173.2 1673.05
#Mann= 8 ,-1 , 0
       0    .035       0   458.3    .045       0   488.4    .035       0
  526.35     .06       0  536.35     .04       0  656.35    .035       0
  896.35     .06       0 1103.55    .035       0
Bank Sta=458.3,488.4
XS Rating Curve= 0 ,0
Exp/Cntr=0.3,0.1

Type RM Length L Ch R = 1 ,14574   ,301.9,303.1,301
XS GIS Cut Line= 3
     2047257.923      191585.758     2048015.735      192010.237
     2048073.027      192176.903
#Sta/Elev= 30
       0    1609     161 1603.87     259 1598.65     418 1592.79   435.5  1591.4
   461.4 1586.21   504.8  1582.4   529.5 1582.43   555.9 1584.94   570.9 1585.15
   604.8 1583.92   683.2 1583.77   691.2 1583.09   704.71579.718   709.7 1579.44
   727.51580.071   733.8 1582.04   740.1 1587.26   743.4  1588.9   762.8 1589.38
   766.5 1592.16   777.7 1603.31   791.6 1615.83   822.4 1639.57   841.7 1649.99
   856.7 1655.86   900.6 1668.13   925.6  1674.1   990.8 1681.87  1044.8 1686.34
#Mann= 5 ,-1 , 0
       0    .035       0     650     .04       0   704.7    .045       0
   727.5     .06       0     760      .1       0
Bank Sta=704.7,727.5
XS Rating Curve= 0 ,0
Exp/Cntr=0.3,0.1

Type RM Length L Ch R = 1 ,14271   ,400.9,396.6,391.8
XS GIS Cut Line= 3
     2047106.881       191812.32     2047895.944      192273.258
     2048002.714      192273.258
#Sta/Elev= 30
       0 1612.89   127.3 1606.08   360.4 1595.77     425 1591.51   440.2 1589.22
   447.8 1586.56     482 1582.85   504.8 1582.23   542.8 1583.95     577 1583.75
   588.6 1581.95   603.6 1581.01     615 1581.76   635.41579.444     639 1579.29
   658.41579.521   673.6 1583.07   721.4 1585.47   725.4 1586.39   734.9 1592.42
   739.7 1594.32   759.4  1594.6   763.2 1595.54   771.2 1605.56   775.7 1609.92
   806.7 1629.75   828.5 1641.51   849.2 1649.11   951.1 1668.66  1020.6 1677.06
#Mann= 6 ,-1 , 0
       0    .035       0   635.4    .045       0   658.4     .04       0
     720     .06       0     830     .04       0  943.83      .1       0
Bank Sta=635.4,658.4
XS Rating Curve= 0 ,0
Exp/Cntr=0.5,0.3

Type RM Length L Ch R = 1 ,13874   ,52.7,57.9,51.5
XS GIS Cut Line= 3
     2046932.402       192187.322047330.04843601 192406.19173968
2047772.31035028192524.237248575
#Sta/Elev= 30
       0 1611.07    49.4 1609.12   184.3  1601.6   309.9 1596.57   367.1 1595.63
   416.2 1591.25   434.6 1588.19   463.5 1587.19   481.7 1584.77   500.5 1578.61
   519.7 1577.37     528 1576.77   548.31577.486   565.4 1583.57   572.9 1584.84
   613.6  1584.2     672 1585.88   680.9 1587.14   690.8 1590.49   714.8 1590.84
   725.6 1598.43   735.2 1603.61   749.8 1612.95   762.3 1615.03   779.3 1620.18
   789.5 1621.86   816.8 1624.58   843.8 1625.96   857.4 1627.95   911.6 1623.92
#Mann= 10 ,-1 , 0
       0    .035       0     230     .06       0     300    .035       0
     340     .04       0   453.9    .035       0   519.7    .045       0
   548.3     .04       0   553.9     .06       0   863.9     .04       0
  911.65      .1       0
#XS Ineff= 2 , 0
           493.9  1582.9  558.72         1582.48
Permanent Ineff=
       F       F
Bank Sta=519.7,548.3
XS Rating Curve= 0 ,0
Exp/Cntr=0.5,0.3

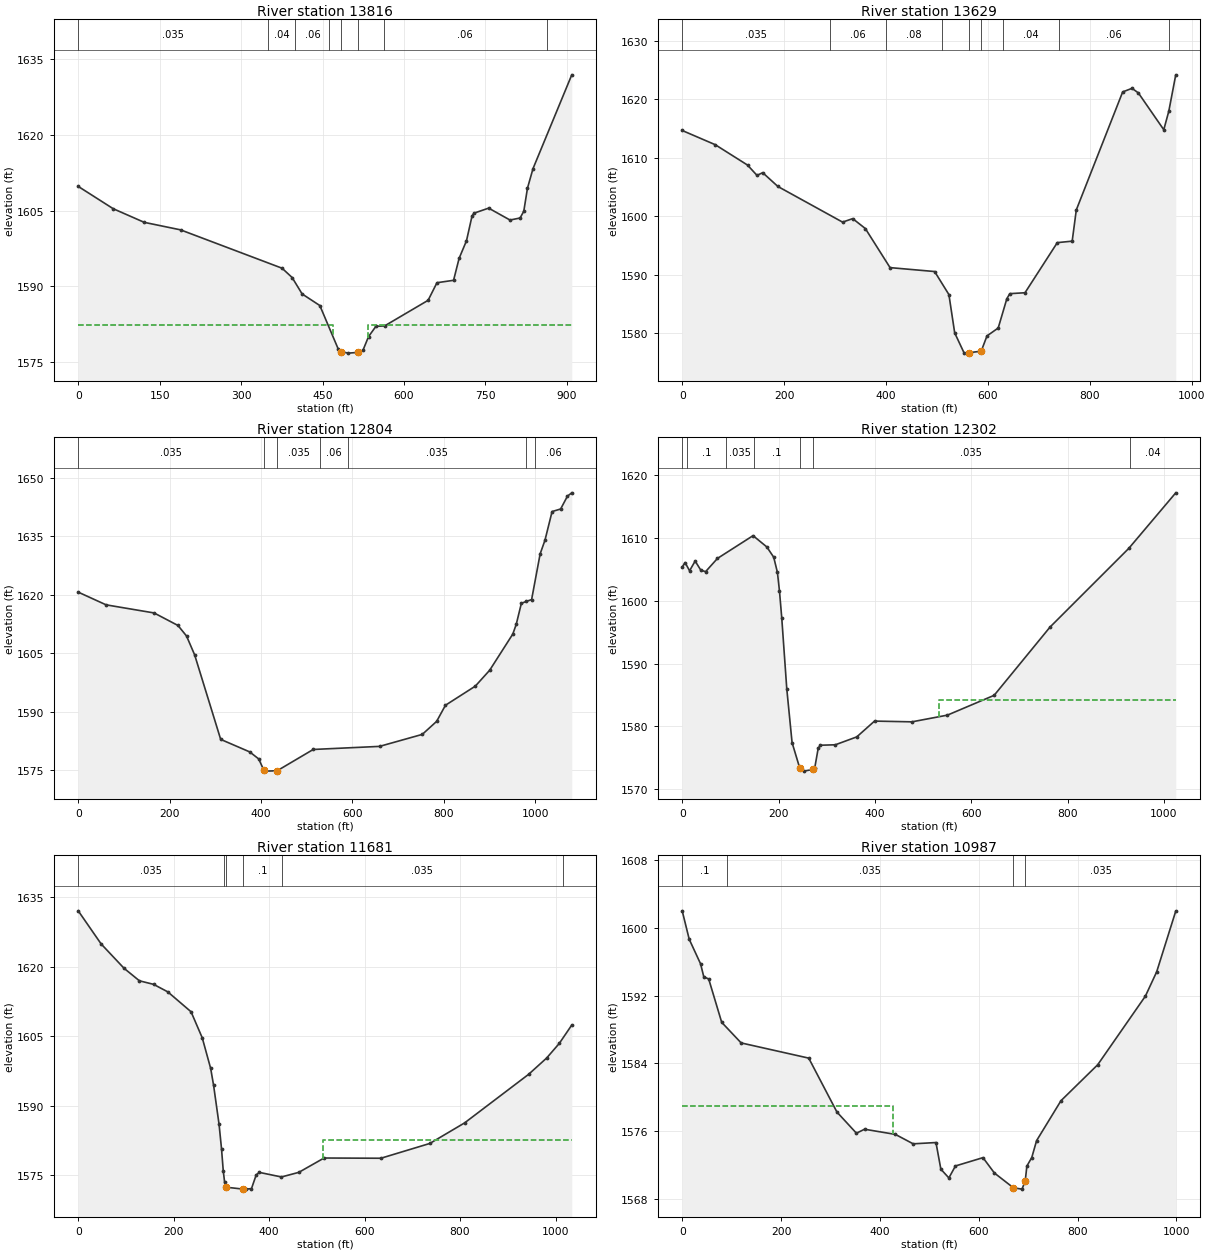
Type RM Length L Ch R = 1 ,13816   ,183.8,187.2,193.5
XS GIS Cut Line= 3
     2046924.589      192242.0082047325.77433648192451.541329244
     2047765.735      192572.737
#Sta/Elev= 30
       0 1609.78    64.5 1605.35   121.6 1602.65   188.5 1601.16   375.4 1593.55
     394  1591.7   412.4 1588.44     445 1586.14   478.9 1577.51   483.91577.003
   497.3  1576.7   515.71576.845   524.5 1577.29   534.7 1579.98   548.3 1582.02
   564.3  1582.1   644.4 1587.18   660.7 1590.67   691.3 1591.15   701.5 1595.51
   715.1    1599   725.3 1603.91   728.7 1604.46   755.9 1605.47   795.2 1603.11
   813.8 1603.51   820.6 1604.85   827.4 1609.43   837.6 1613.31     909 1631.92
#Mann= 8 ,-1 , 0
       0    .035       0     350     .04       0     400     .06       0
  462.61     .04       0   483.9    .045       0   515.7     .04       0
  562.61     .06       0  862.61      .1       0
#XS Ineff= 2 , 0
          468.42 1582.37  533.77         1582.27
Permanent Ineff=
       F       F
Bank Sta=483.9,515.7
XS Rating Curve= 0 ,0
Exp/Cntr=0.5,0.3

Type RM Length L Ch R = 1 ,13629   ,826.8,825,825.2
XS GIS Cut Line= 3
2046780.36240125192355.8999519232047540.77940125192767.358951923
2047644.94640125192769.962951923
#Sta/Elev= 30
       0 1614.69    64.8 1612.26   128.2 1608.77   146.9    1607     158 1607.47
   187.9  1605.1   314.8    1599   334.7  1599.6   359.5  1597.9     408 1591.21
   495.5 1590.54   523.5  1586.6   534.9 1580.03   553.5 1576.57   562.61576.636
   586.91576.904   598.3 1579.52   620.3 1580.87   637.2 1585.87     643 1586.75
   672.9 1586.91   736.3 1595.49   765.5 1595.74   773.6 1601.09   864.6 1621.29
     883 1621.91   895.4 1621.12   945.3 1614.82   955.2 1618.01   968.8 1624.22
#Mann= 9 ,-1 , 0
       0    .035       0     290     .06       0     400     .08       0
     510     .06       0   562.6    .045       0   586.9     .06       0
     630     .04       0     740     .06       0   954.6    .035       0
Bank Sta=562.6,586.9
XS Rating Curve= 0 ,0
Exp/Cntr=0.3,0.1

Type RM Length L Ch R = 1 ,12804   ,496.4,501.7,501.1
XS GIS Cut Line= 2
     2046376.738      193031.649     2047324.654       193549.01
#Sta/Elev= 30
       0 1620.66      61  1617.4     166 1615.32   218.3  1612.1     237  1609.4
   254.7 1604.57   311.7 1582.87   375.3 1579.65   394.9 1577.85   405.81575.038
   408.9 1574.72   435.21574.809   514.2 1580.28   659.3 1581.07   752.8 1584.15
   784.2 1587.49   803.5 1591.63   868.8 1596.53   900.3 1600.62   950.9 1609.91
   958.4  1612.4   969.6 1617.79     980 1618.26     992 1618.75  1010.7 1630.49
  1021.2 1633.97  1036.8 1641.34  1055.5    1642  1070.5 1645.31  1079.9 1646.15
#Mann= 7 ,-1 , 0
       0    .035       0   405.8    .045       0   435.2    .035       0
     530     .06       0     590    .035       0     980     .04       0
    1000     .06       0
Bank Sta=405.8,435.2
XS Rating Curve= 0 ,0
Exp/Cntr=0.3,0.1

Type RM Length L Ch R = 1 ,12302   ,636.7,621.5,609.8
XS GIS Cut Line= 4
     2046237.849      193451.788     2046366.321      193566.371
     2046845.488      193868.454     2047126.738      193920.538
#Sta/Elev= 30
       0 1605.38       6  1606.1    15.3 1604.79    26.9 1606.34    38.7 1604.88
    48.6 1604.65    73.2 1606.76   147.1 1610.39   175.7 1608.59     190 1606.95
   197.7 1604.53   201.9  1601.6   206.7 1597.25   217.1 1585.97   228.1 1577.39
   244.2 1573.28     252 1572.84   271.4  1573.1   275.2 1573.37   282.4 1576.51
   286.9 1576.97   317.9 1577.04   362.4  1578.3   399.3 1580.82   476.9  1580.7
   550.6 1581.77   647.6 1584.93   763.7 1595.82   927.2 1608.37  1024.6 1617.22
#Mann= 7 ,-1 , 0
       0    .035       0      10      .1       0      90    .035       0
     150      .1       0   244.2    .045       0   271.4    .035       0
  928.59     .04       0
#XS Ineff= 2 , 0
                          533.82         1584.23
Permanent Ineff=
       F       F
Bank Sta=244.2,271.4
XS Rating Curve= 0 ,0
Exp/Cntr=0.3,0.1

Type RM Length L Ch R = 1 ,11681   ,698.5,694.2,693.5
XS GIS Cut Line= 3
     2046026.043      194201.788     2046119.793      194222.621
     2047050.349      194104.565
#Sta/Elev= 30
       0 1632.06      48 1624.92      96 1619.67   128.2 1616.97     158  1616.2
   187.7 1614.58   236.4 1610.29   259.9 1604.66   277.5 1598.07   283.6 1594.45
   295.1 1586.01   300.2 1580.78   303.9 1575.96   306.8 1573.49   309.21572.464
   345.31572.046   350.8 1572.04     363 1572.15   372.9  1575.1   379.5 1575.65
   425.8 1574.66   462.2 1575.66   515.1 1578.75   634.2  1578.7   736.7 1581.89
   809.5 1586.32   943.7  1596.8   981.4 1600.31  1007.9 1603.46  1034.1 1607.43
#Mann= 6 ,-1 , 0
       0    .035       0  306.04      .1       0   309.2    .045       0
   345.3      .1       0  426.04    .035       0 1016.04     .04       0
#XS Ineff= 2 , 0
                          513.04         1582.57
Permanent Ineff=
       F       F
Bank Sta=309.2,345.3
XS Rating Curve= 0 ,0
Exp/Cntr=0.3,0.1

Type RM Length L Ch R = 1 ,10987   ,399.8,393,380.1
XS GIS Cut Line= 2
     2045963.652      194801.903     2046961.048      194755.028
#Sta/Elev= 30
       0 1601.98    14.2 1598.63    37.2 1595.73    43.7  1594.2    53.6 1593.95
    79.9 1588.84   119.3 1586.41     256 1584.62   313.1 1578.26   352.5 1575.77
   368.9 1576.24   431.3 1575.63   467.3 1574.52   513.4 1574.67   523.3 1571.53
   539.5  1570.5   552.8 1571.91   608.5 1572.89   631.6 1571.08   670.2 1569.33
   687.5 1569.18     694 1570.15   697.3  1571.9   707.2  1572.9     717  1574.9
   766.3  1579.6   840.6 1583.84   937.1 1591.93   959.9 1594.79   998.5 1601.95
#Mann= 4 ,-1 , 0
       0      .1       0      90    .035       0   670.2    .045       0
     694    .035       0
#XS Ineff= 2 , 0
          426.48    1579
Permanent Ineff=
       F       F
Bank Sta=670.2,694
XS Rating Curve= 0 ,0
Exp/Cntr=0.5,0.3

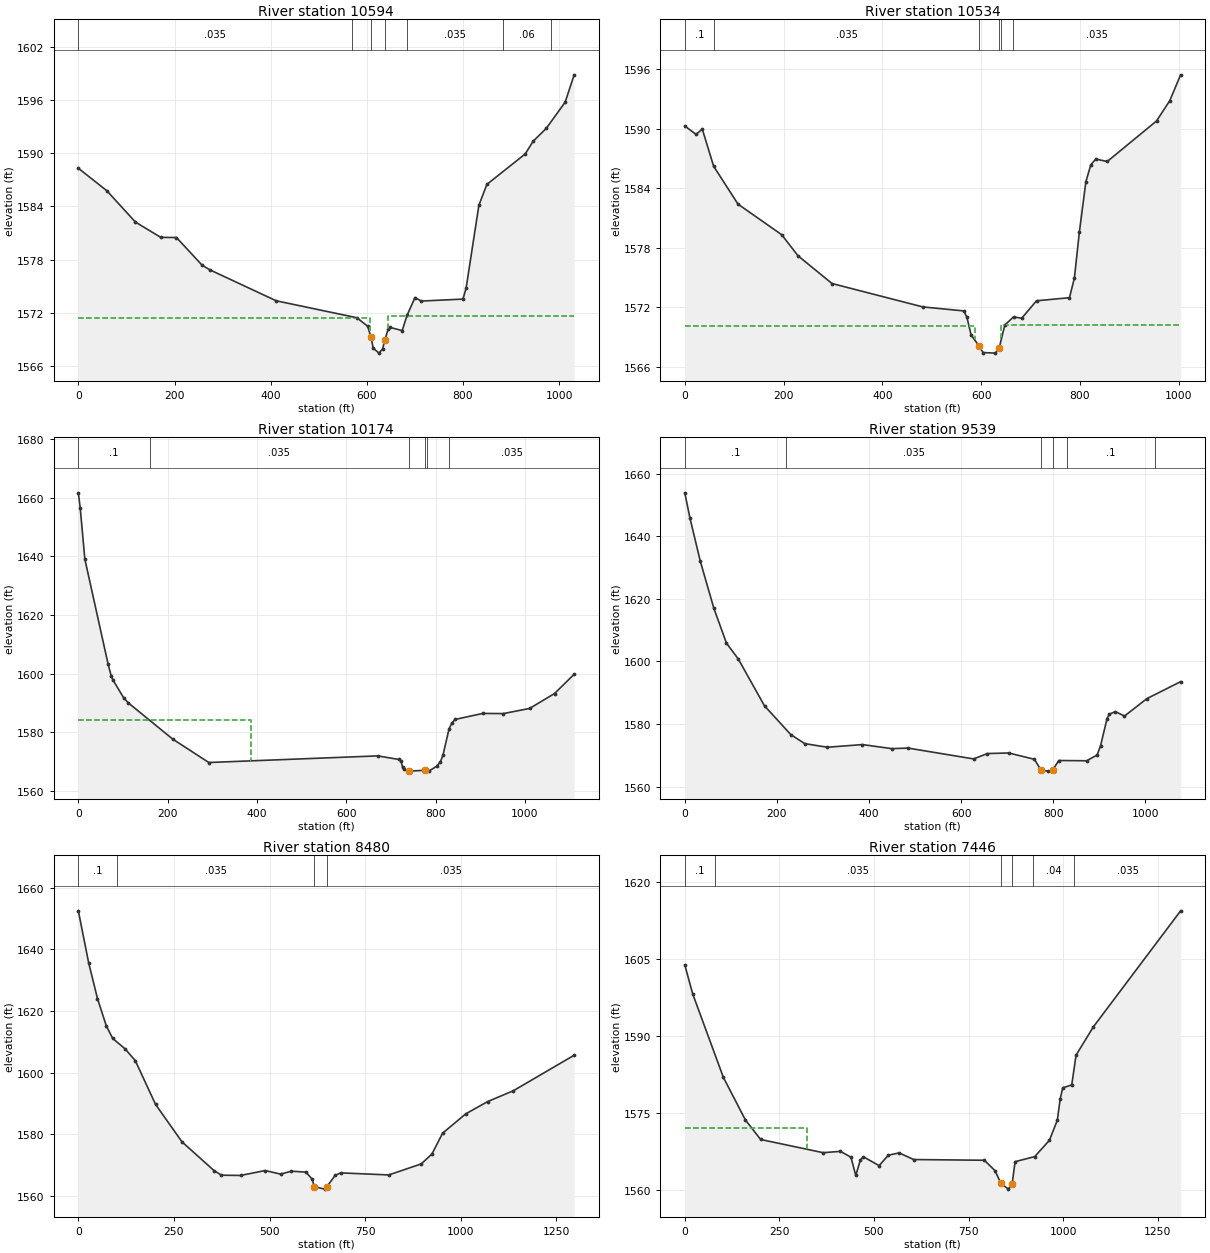
Type RM Length L Ch R = 1 ,10594   ,61.1,60.1,59.1
XS GIS Cut Line= 4
     2045974.069      195114.4032046556.12012596195153.508425484
 2046623.4406424195111.217331824     2046987.089      195169.091
#Sta/Elev= 30
       0 1588.31    59.2 1585.78   118.8 1582.24   171.4 1580.52   204.1  1580.5
   256.9 1577.41   273.4 1576.86   411.5 1573.37   579.2 1571.46   601.7  1570.5
   608.41569.294   613.3 1568.03   625.2 1567.47   632.7 1567.95   637.8    1569
   644.3 1570.18   648.2 1570.37   673.5 1570.01   683.5 1571.72   700.1 1573.73
   713.4 1573.34   799.8 1573.56   806.4 1574.79     833 1584.14   849.6 1586.49
   929.3 1589.92   945.9 1591.36   973.2 1592.81  1012.4 1595.76  1031.1 1598.84
#Mann= 7 ,-1 , 0
       0    .035       0     570     .04       0   608.4    .045       0
   637.8     .04       0  682.87    .035       0  882.87     .06       0
  982.87    .035       0
#XS Ineff= 2 , 0
          606.06 1571.43  644.85         1571.66
Permanent Ineff=
       F       F
Bank Sta=608.4,637.8
XS Rating Curve= 0 ,0
Exp/Cntr=0.5,0.3

Type RM Length L Ch R = 1 ,10534   ,350.8,359.4,364.4
XS GIS Cut Line= 4
     2045994.902      195195.1332046555.25704242 195218.23969129
2046637.24997911195170.7700963662046980.30432659195231.695245574
#Sta/Elev= 30
       0 1590.27    22.9 1589.42    35.4 1589.96    58.4 1586.21   107.7 1582.39
   196.3  1579.3   229.2 1577.18   298.1 1574.38     482 1572.02   564.6 1571.62
   571.1 1571.01   579.8 1569.18   595.8 1568.09   603.8 1567.42     629 1567.36
   636.6 1567.87     648  1570.2   665.6 1571.01   682.2 1570.88   712.2 1572.64
   778.9 1572.95   788.9 1574.93   798.9 1579.55   812.2 1584.66   822.2 1586.36
   832.2 1586.93   855.5 1586.69   955.3 1590.78   982.1 1592.83    1004 1595.43
#Mann= 6 ,-1 , 0
       0      .1       0      60    .035       0   595.8    .045       0
   636.6    .035       0  640.83     .04       0  665.57    .035       0
#XS Ineff= 2 , 0
          586.67 1570.11  641.21         1570.19
Permanent Ineff=
       F       F
Bank Sta=595.8,636.6
XS Rating Curve= 0 ,0
Exp/Cntr=0.5,0.3

Type RM Length L Ch R = 1 ,10174   ,632.9,635,622.6
XS GIS Cut Line= 2
      2046000.11      195744.612     2047049.589      195382.633
#Sta/Elev= 30
       0 1661.71     4.2 1656.59    14.6  1639.1    66.6 1603.31    73.6 1599.25
      77 1598.02   101.3 1591.85   111.8 1590.08   211.3 1577.72   292.1 1569.73
   670.5 1571.99   717.9 1570.76   722.6 1570.25     726 1568.07   728.2 1567.48
   739.9 1566.79   740.11566.793   776.11567.073     785 1566.84   802.4 1568.43
   810.8 1570.04   816.3 1572.13   830.1 1581.21   836.6 1583.31     844 1584.43
   905.6 1586.47   951.6 1586.41  1010.6 1588.18  1066.3 1593.26  1110.2 1599.84
#Mann= 6 ,-1 , 0
       0      .1       0     160    .035       0   740.1    .045       0
   776.1    .035       0     780      .1       0     830    .035       0
#XS Ineff= 2 , 0
          386.44 1584.28
Permanent Ineff=
       F       F
Bank Sta=740.1,776.1
XS Rating Curve= 0 ,0
Exp/Cntr=0.3,0.1

Type RM Length L Ch R = 1 ,9539    ,1057.3,1058.7,1049.9
XS GIS Cut Line= 2
      2046312.61      196372.216     2047247.506      195838.362
#Sta/Elev= 30
       0 1653.85    11.1 1645.84    33.8 1631.94    63.1 1616.97    90.5 1605.83
     116 1600.82   173.1 1585.81   230.3 1576.62   260.5 1573.75   309.6  1572.6
   385.7 1573.45   449.4 1572.15   484.9 1572.33     627 1568.87   657.1 1570.58
   703.3 1570.77   759.2 1568.74   773.3 1565.29   789.3 1564.97   798.4 1565.25
   812.1 1568.36   872.5 1568.28   895.2  1570.1   902.8  1573.1   916.8  1581.7
   921.7 1583.15   934.8 1583.98   954.7 1582.56  1003.4 1588.13  1076.6 1593.54
#Mann= 6 ,-1 , 0
       0      .1       0     220    .035       0   773.3    .045       0
   798.4    .035       0     830      .1       0    1020    .035       0
Bank Sta=773.3,798.4
XS Rating Curve= 0 ,0
Exp/Cntr=0.3,0.1

Type RM Length L Ch R = 1 ,8480    ,1026.1,1034,1029
XS GIS Cut Line= 4
     2046744.902      197059.716     2047036.569      197028.466
     2047609.485      196692.528     2047757.923      196387.841
#Sta/Elev= 30
       0 1652.53      27 1635.67    50.1 1624.06    73.2 1615.21    89.7 1611.17
   122.7 1607.71   149.1 1603.91   201.9 1589.75     271 1577.61   354.7 1568.29
   374.3 1566.79   424.3  1566.7   488.4  1568.3   528.9 1567.14   556.9 1568.09
   594.9 1567.79   611.3 1565.53   617.2 1563.04   644.3 1562.27     6501563.085
   671.6 1566.75   686.2 1567.54   811.7 1566.87   896.6 1570.45   924.6 1573.67
   952.4 1580.41  1012.9 1586.68  1070.3 1590.67  1137.3 1594.17  1296.4  1605.7
#Mann= 4 ,-1 , 0
       0      .1       0     100    .035       0   617.2    .045       0
     650    .035       0
Bank Sta=617.2,650
XS Rating Curve= 0 ,0
Exp/Cntr=0.3,0.1

Type RM Length L Ch R = 1 ,7446    ,1052.6,1066.3,1076.7
XS GIS Cut Line= 3
     2047158.964      197762.841      2048250.11      197340.966
     2048390.735      197340.966
#Sta/Elev= 30
       0 1603.89      21 1598.21   101.9 1581.93   160.2  1573.6   200.4 1569.79
   365.6 1567.21   411.3 1567.47   439.2 1566.32   451.9 1562.76   464.2 1565.81
   472.2 1566.41   513.5 1564.68   538.1 1566.72   566.7 1567.17   604.9 1565.87
   791.8 1565.73   819.7 1563.71   835.6 1561.22   855.2 1560.09   865.11561.089
     873 1565.45     925 1566.45   963.7 1569.63   984.6 1573.55   992.2 1577.71
   998.9 1579.88  1022.7 1580.44  1034.1 1586.26  1079.8 1591.79  1310.5 1614.46
#Mann= 6 ,-1 , 0
       0      .1       0      80    .035       0   835.6    .045       0
   865.1    .035       0     920     .04       0    1030    .035       0
#XS Ineff= 2 , 0
          323.46 1572.11
Permanent Ineff=
       F       F
Bank Sta=835.6,865.1
XS Rating Curve= 0 ,0
Exp/Cntr=0.3,0.1

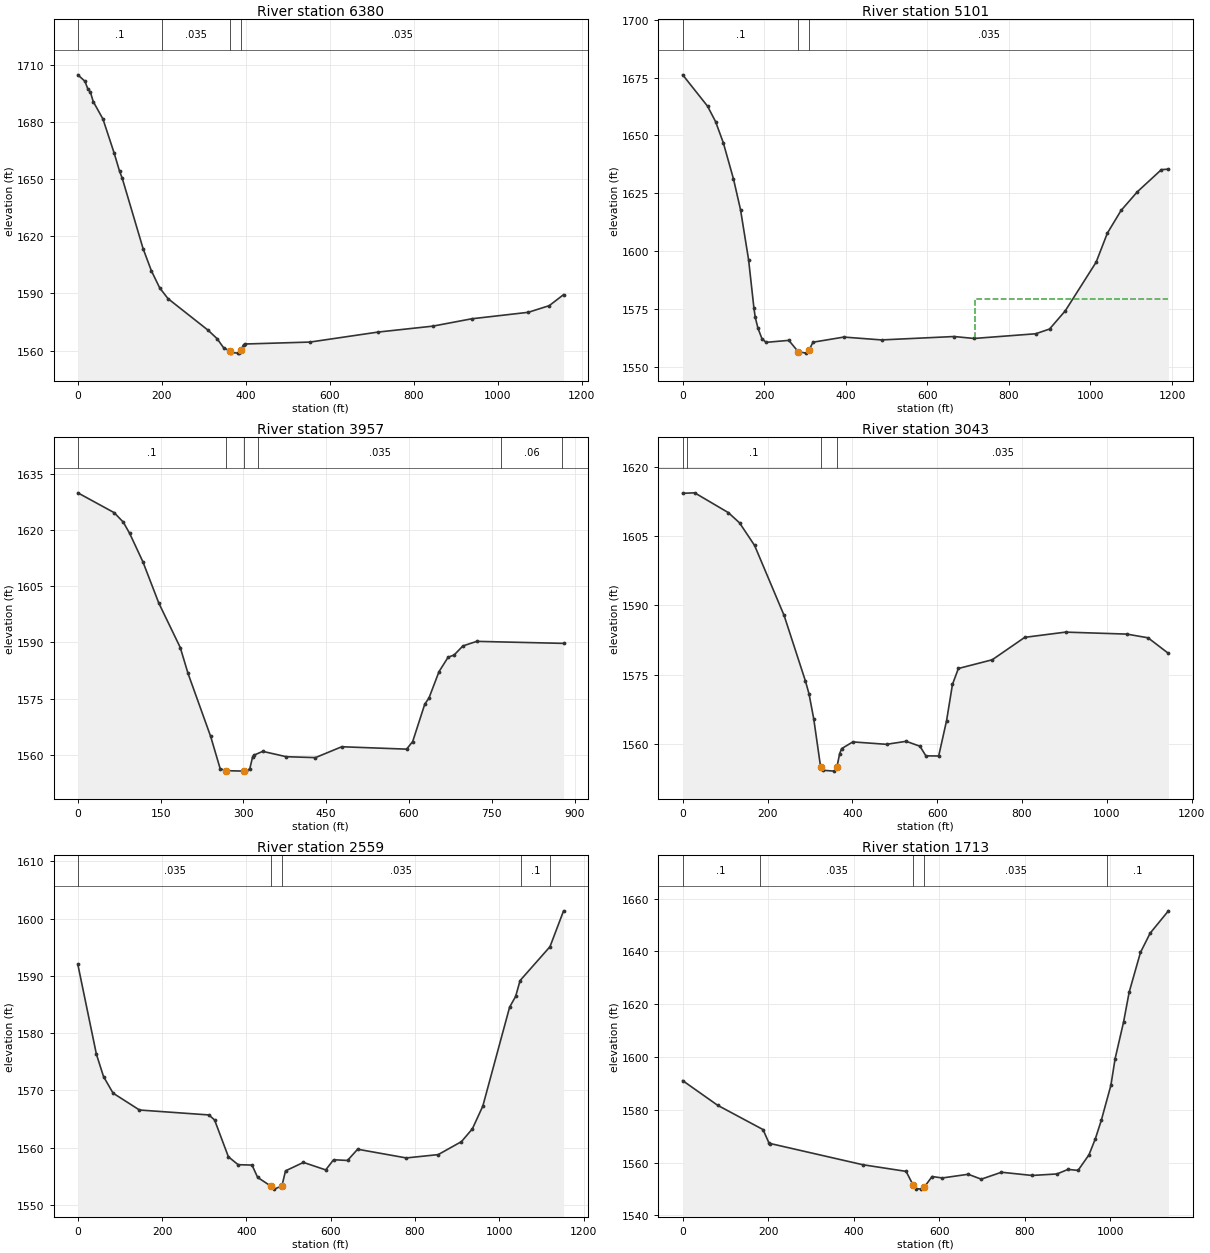
Type RM Length L Ch R = 1 ,6380    ,1272.1,1278.9,1269.5
XS GIS Cut Line= 3
     2047135.527      198307.112     2047440.214      198275.862
     2048268.339      198471.174
#Sta/Elev= 30
       0 1704.97    16.9 1701.59    23.5 1697.75    30.1 1695.77    36.7  1690.9
    59.8 1681.75    86.2 1664.06    99.4 1654.29   105.9 1650.51   155.4 1613.62
   175.2 1601.93     195 1592.93   214.8 1587.28   310.5 1570.63   331.8 1566.21
   347.6 1561.34   361.91559.832   365.6 1558.91   381.3 1558.62   384.6 1558.85
   388.11560.287   394.8 1563.03   398.8 1563.42   553.2 1564.44     715 1569.69
   845.6 1572.81   938.3 1576.68  1072.9 1580.08  1122.9 1583.58  1157.1 1589.38
#Mann= 4 ,-1 , 0
       0      .1       0     200    .035       0   361.9    .045       0
   388.1    .035       0
Bank Sta=361.9,388.1
XS Rating Curve= 0 ,0
Exp/Cntr=0.3,0.1

Type RM Length L Ch R = 1 ,5101    ,1123.6,1144.4,1143.2
XS GIS Cut Line= 4
      2047062.61      199252.424     2047169.381      199325.341
     2048067.819      199395.653     2048211.048       199468.57
#Sta/Elev= 30
       0  1676.2      61 1662.64    80.7 1655.95    99.5 1646.89   124.6 1631.16
   141.8 1617.92   161.6 1596.27   174.7 1575.38     178 1571.33   184.6 1566.63
   194.3 1562.16   204.3 1560.53   260.3 1561.39   283.31556.482   303.1 1555.87
   309.51557.019   319.5 1560.59   395.2 1562.81   487.6 1561.58   665.6 1563.05
   714.4 1562.21   865.5 1564.24   899.6 1566.28   938.2 1574.16  1013.9  1595.2
  1041.4 1607.74    1075 1617.55    1115 1625.64  1173.9  1635.2  1191.2 1635.41
#Mann= 3 ,-1 , 0
       0      .1       0   283.3    .045       0   309.5    .035       0
#XS Ineff= 2 , 0
                          715.93         1579.14
Permanent Ineff=
       F       F
Bank Sta=283.3,309.5
XS Rating Curve= 0 ,0
Exp/Cntr=0.3,0.1

Type RM Length L Ch R = 1 ,3957    ,903.5,913.6,919.3
XS GIS Cut Line= 3
     2046955.839      199856.591      2047031.36      200049.299
     2047632.923      200351.383
#Sta/Elev= 30
       0 1629.95    65.8 1624.66    82.4 1622.12      94 1619.09   117.9 1611.53
   146.8 1600.48   185.6 1588.64   199.7 1581.71   240.7 1564.89   257.9 1556.29
   269.11555.761   301.71555.644   305.6 1555.64   311.6  1556.3   316.7 1559.44
   318.9 1559.89     335 1560.92   377.6 1559.49   430.5 1559.25   478.2 1562.15
   595.7 1561.51   606.7 1563.54   628.7 1573.57   636.1 1575.12   654.4 1582.21
   670.9 1586.06   681.7 1586.64   697.7 1589.07   722.8 1590.29   880.1 1589.75
#Mann= 6 ,-1 , 0
       0      .1       0   269.1    .045       0   301.7      .1       0
  326.98    .035       0  766.98     .06       0  876.98    .035       0
Bank Sta=269.1,301.7
XS Rating Curve= 0 ,0
Exp/Cntr=0.3,0.1

Type RM Length L Ch R = 1 ,3043    ,461.4,484.7,498.2
XS GIS Cut Line= 4
     2046669.381      200486.799     2046703.235      200778.466
      2047031.36      201114.403     2047317.819      201367.008
#Sta/Elev= 30
       0 1614.22    28.3 1614.32   107.6 1610.04     134 1607.83   169.5 1602.94
   239.1 1587.79   289.3 1573.63   297.8 1570.84   308.9 1565.45   325.1 1555.05
   329.7 1554.31   357.6 1554.12   363.5 1554.98   370.1 1557.92   374.7 1558.99
   401.1 1560.44   480.5 1559.92   526.9 1560.57   559.4  1559.5   573.3 1557.42
   603.5  1557.4   622.1 1565.05     636 1572.89   649.9 1576.32   729.8 1578.21
   806.4 1583.06   902.7 1584.19  1047.2 1583.76    1097 1582.96  1145.1 1579.59
#Mann= 4 ,-1 , 0
       0    .035       0      10      .1       0   325.1    .045       0
   363.5    .035       0
Bank Sta=325.1,363.5
XS Rating Curve= 0 ,0
Exp/Cntr=0.3,0.1

Type RM Length L Ch R = 1 ,2559    ,847.3,845.9,837.9
XS GIS Cut Line= 3
     2046380.319      200484.195     2046291.777      201390.445
     2046382.923      201614.403
#Sta/Elev= 30
       0    1592    44.1  1576.3      61  1572.4    83.6 1569.51   146.3 1566.56
   311.1  1565.7   324.5 1564.81   357.2 1558.39   380.3 1557.01   413.3 1556.94
   426.6 1554.79   458.61553.237   466.5 1552.74   484.31553.329   492.7 1555.93
   535.2 1557.41     588  1556.1   606.8 1557.87   639.8 1557.75   663.8 1559.71
   779.2 1558.19     855 1558.77   910.1 1561.04   935.9 1563.26   960.7 1567.23
  1024.4 1584.54  1038.6  1586.4  1049.2 1589.18  1120.1 1595.09  1152.4 1601.36
#Mann= 5 ,-1 , 0
       0    .035       0   458.6    .045       0   484.3    .035       0
 1050.57      .1       0 1120.57    .035       0
Bank Sta=458.6,484.3
XS Rating Curve= 0 ,0
Exp/Cntr=0.3,0.1

Type RM Length L Ch R = 1 ,1713    ,800.6,794.7,777.9
XS GIS Cut Line= 4
     2045507.923      200329.681     2045570.423      200572.737
      2045741.43       201272.39      2045754.45      201436.452
#Sta/Elev= 30
       0 1591.04    81.9 1581.68   187.8  1572.5   201.4 1567.55   204.8  1567.2
   421.1 1559.17   522.4 1556.65   539.11551.359   546.1 1550.15   556.4 1549.92
   565.21550.769   583.2  1554.7   606.9 1554.15   667.7 1555.55   698.1 1553.69
   745.4 1556.32     817  1555.1   875.1 1555.67   901.1  1557.4   924.4 1557.01
     950 1562.93   964.9 1569.01   978.7 1575.93  1001.3  1589.3  1011.1 1599.36
  1030.9 1613.25    1044 1624.59  1070.4 1639.62    1093 1646.92  1135.8 1655.39
#Mann= 5 ,-1 , 0
       0      .1       0     180    .035       0   539.1    .045       0
   565.2    .035       0  991.21      .1       0
Bank Sta=539.1,565.2
XS Rating Curve= 0 ,0
Exp/Cntr=0.3,0.1

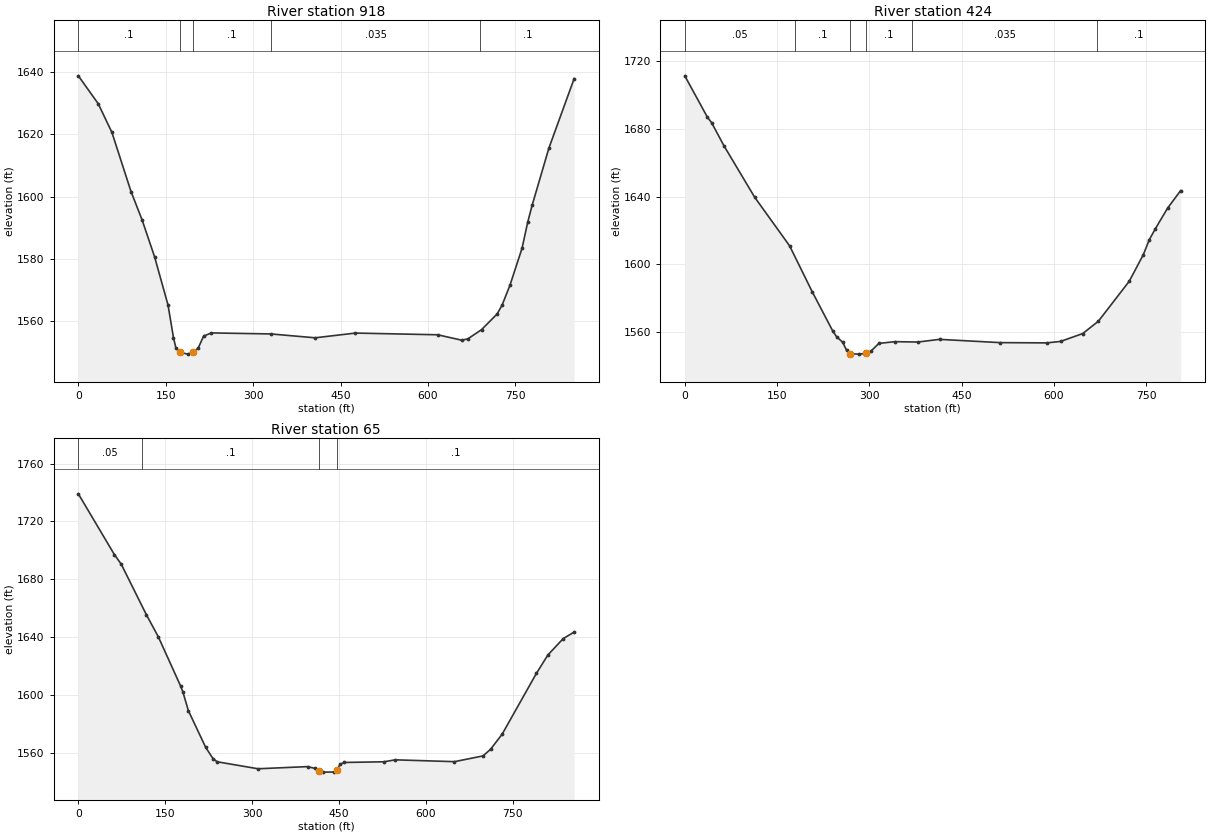
Type RM Length L Ch R = 1 ,918     ,497.1,494.1,478.9
XS GIS Cut Line= 3
     2044999.242      200983.327     2045587.784       201410.41
     2045704.971      201449.473
#Sta/Elev= 30
       0 1638.78    34.1 1629.84    57.6 1620.63    90.4 1601.64   109.2 1592.63
   130.8 1580.71   153.9 1565.21   163.2 1554.79   167.3 1551.52   173.61550.127
   187.5 1549.46   196.5 1550.02   205.5 1551.34   214.9 1555.23   228.1 1556.27
     330 1555.94   406.4  1554.7   475.4 1556.22   616.6 1555.67   657.8 1553.93
   668.3 1554.36   691.8 1557.32   718.6 1562.36   727.2 1565.25   740.6  1571.6
   761.3 1583.45   771.1 1591.88   778.6 1597.23   807.4  1615.6   850.7  1637.9
#Mann= 5 ,-1 , 0
       0      .1       0   173.6    .045       0   196.5      .1       0
     330    .035       0     690      .1       0
Bank Sta=173.6,196.5
XS Rating Curve= 0 ,0
Exp/Cntr=0.3,0.1

Type RM Length L Ch R = 1 ,424     ,353.1,359.1,359
XS GIS Cut Line= 3
     2044895.075      201577.077     2045111.221       201535.41
     2045697.159      201551.035
#Sta/Elev= 30
       0 1711.22    36.8 1686.78    43.5 1683.65    63.5 1670.06   113.7 1639.54
   170.5 1610.86   207.2 1583.81   240.9 1560.43   246.8 1557.32   256.7    1554
   263.2  1549.2   269.21547.218   282.9    1547   294.51547.417   302.6 1548.74
   315.7 1553.33     342 1554.36   379.2 1554.14   414.2 1555.72   512.7 1553.79
   588.3 1553.63   611.1  1554.5   647.2 1559.16   672.6 1566.44   722.7 1589.99
   745.7 1605.74   755.5 1614.63   765.4 1621.11   785.1 1633.16   806.3 1643.51
#Mann= 6 ,-1 , 0
       0     .05       0     180      .1       0   269.2    .045       0
   294.5      .1       0  370.13    .035       0  670.13      .1       0
Bank Sta=269.2,294.5
XS Rating Curve= 0 ,0
Exp/Cntr=0.3,0.1

Type RM Length L Ch R = 1 ,65      ,64.3,64.8,65.4
XS GIS Cut Line= 3
      2044879.45      201694.265     2045119.034      201853.987
     2045685.006      201902.598
#Sta/Elev= 30
       0 1739.11    62.3 1697.04      74 1690.49   117.4 1655.54     138 1640.28
   176.6 1606.11   180.6 1601.92     190 1589.08   219.9 1563.69   232.6 1555.86
   239.7 1553.74   310.2 1548.91   395.8 1550.39   408.1 1549.21   415.31547.102
   422.1 1546.58   441.9 1546.66   446.4 1548.17   451.8 1551.91   458.4 1553.26
   527.5 1553.74   547.3 1555.08   649.4 1553.82   698.7 1557.81   711.9  1562.5
   731.7 1572.85   790.9 1614.95   810.7 1627.65     837 1638.92     856 1643.49
#Mann= 4 ,-1 , 0
       0     .05       0     110      .1       0   415.3    .045       0
   446.4      .1       0
Bank Sta=415.3,446.4
XS Rating Curve= 0 ,0
Exp/Cntr=0.3,0.1
Stream Node=HNSCK           ,Main            , 0 , 0 ,Upstream end
Stream Node=HNSCK           ,Main            , 0 , 1 ,Downstream end
LCMann Table=0

Chan Stop Cuts=-1
Use User Specified Reach Order=0
Composite Channel Slope=5